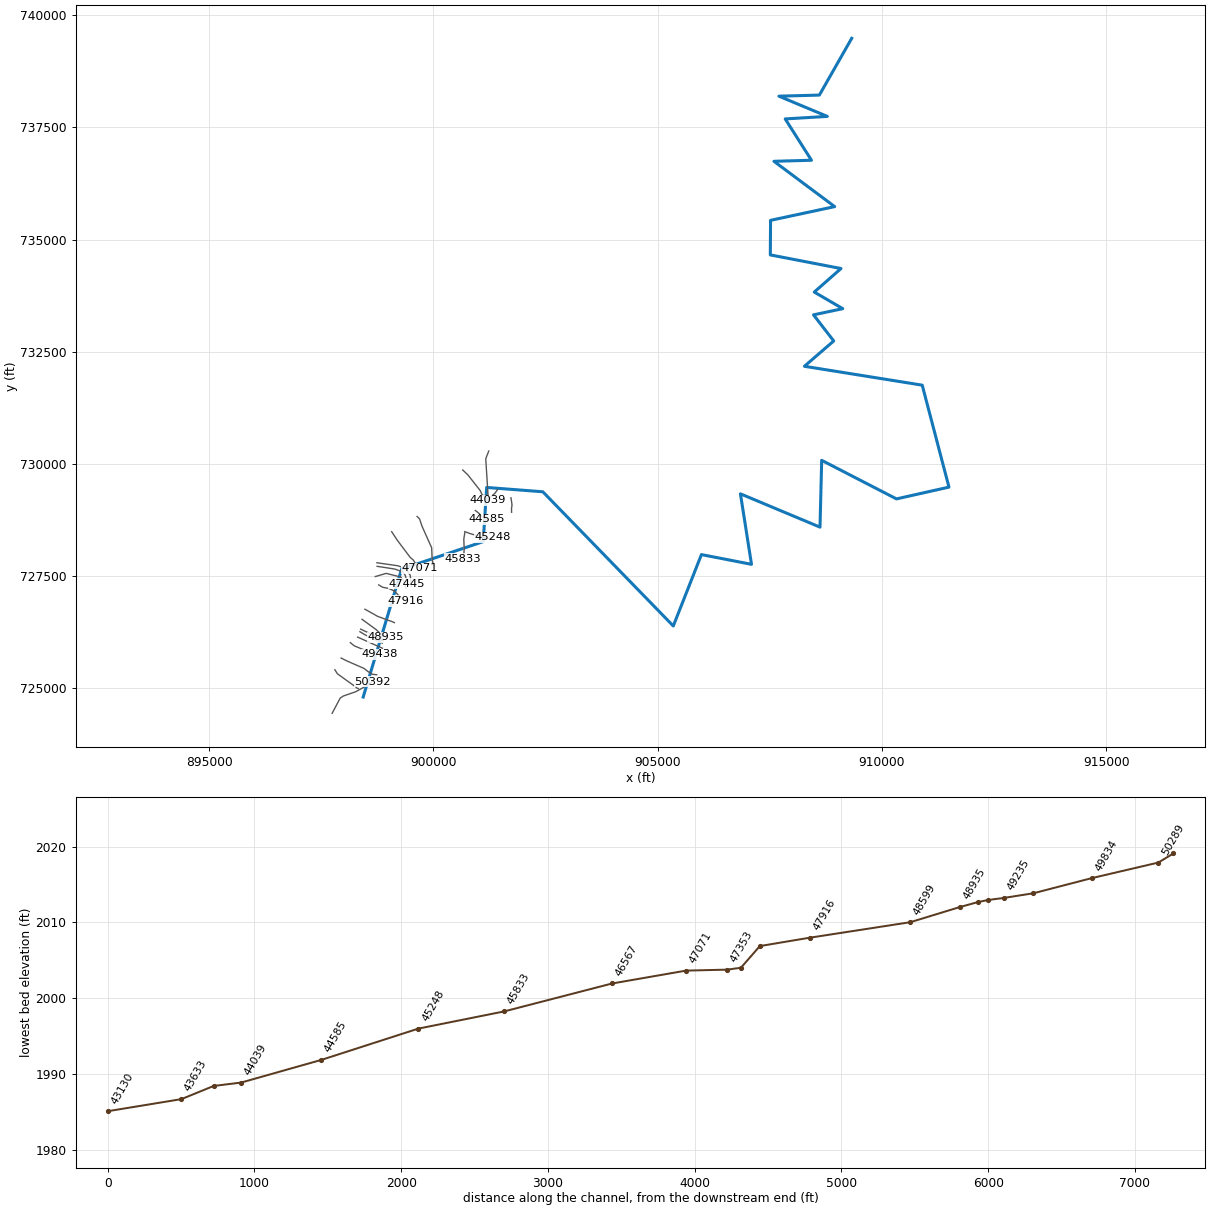
--- lds_turkey_crk.prj (project) ---

Proj Title=Turkey Creek Limited Detail Study
Current Plan=p01
Default Exp/Contr=0.3,0.1
English Units
Geom File=g01
Flow File=f01
Plan File=p01
Y Axis Title=Elevation
X Axis Title(PF)=Main Channel Distance
X Axis Title(XS)=Station
BEGIN DESCRIPTION:
Turkey Creek
END DESCRIPTION:
DSS Export Rating Curves= 0
DSS Export Rating Curve Sorted= 0
DSS Export Volume Flow Curves= 0
DXF OffsetX= 0
DXF OffsetY= 0
DXF ScaleX= 1
DXF ScaleY= 10

--- lds_turkey_crk.p01 (plan) ---

Plan Title=Floodway Run
Program Version=3.13
Short Identifier=Floodway
Geom File=g01
Flow File=f01
Subcritical Flow
K Sum by GR= 0
Std Step Tol= 0.01
Critical Tol= 0.01
Num of Std Step Trials= 20
Max Error Tol= 0.3
Flow Tol Ratio= 0.001
Split Flow NTrial= 30
Split Flow Tol= 0.02
Split Flow Ratio= 0.02
Log Output Level= 0
Friction Slope Method= 0
Unsteady Friction Slope Method= 2
Unsteady Bridges Friction Slope Method= 1
Parabolic Critical Depth
Global Vel Dist= 0 , 0 , 0
Global Log Level= 0
CheckData=True
Encroach Param=-1 ,10,10, 2
Encroach River=Turkey Creek
Encroach Reach=Reach-1
Encroach Node=50392
       1  4780.7 5021.88
Encroach Node=50289
       4      .7
Encroach Node=49834
       1  4609.6    5076
Encroach Node=49438
       1  4764.8  5023.5
Encroach Node=49235
       1    4800    5021
Encroach Node=49126
       4      .7
Encroach Node=49057
       1    4875    5042
Encroach Node=48935
       4      .7
Encroach Node=48599
       4      .7
Encroach Node=47916
       4      .7
Encroach Node=47574
       4      .7
Encroach Node=47445
       1  4807.1    5060
Encroach Node=47353
       1    4807 5033.05
Encroach Node=47071
       4      .7
Encroach Node=46567
       4      .7
Encroach Node=45833
       4      .7
Encroach Node=45248
       4      .7
Encroach Node=44585
       1  4972.3 5067.81
Encroach Node=44039
       4      .7
Encroach Node=43853
       1  4822.2    5173
Encroach Node=43633
       4      .7
Encroach Node=43130
       4      .7
Encroach Node=42659
       4      .7
Encroach Node=42201
       1  4974.1  5042.5
Encroach Node=41698
       4      .7
Encroach Node=41222
       4      .7
Encroach Node=40642
       4      .7
Encroach Node=40179
       4      .7
Encroach Node=39544
       4      .7
Encroach Node=39340
       1    4950    5113
Encroach Node=39259
       1  4974.6  5116.5
Encroach Node=39123
       4      .7
Encroach Node=38653
       4      .7
Encroach Node=37959
       4      .7
Encroach Node=37662
       4      .7
Encroach Node=37366
       1  4802.2 5029.79
Encroach Node=36690
       4      .7
Encroach Node=36234
       4      .7
Encroach Node=35652
       4      .7
Encroach Node=34982
       4      .7
Encroach Node=34438
       1  4885.7 5037.98
Encroach Node=33867
       4      .7
Encroach Node=33232
       4      .7
Encroach Node=32900
       4      .7
Encroach Node=32622
       4      .7
Encroach Node=32022
       4      .7
Encroach Node=31423
       4      .7
Encroach Node=30899
       4      .7
Encroach Node=30472
       4      .7
Encroach Node=29915
       4      .7
Encroach Node=29201
       4      .7
Encroach Node=28551
       4      .7
Encroach Node=27760
       4      .7
Encroach Node=27085
       4      .7
Encroach Node=26627
       1  4897.5 5023.86
Encroach Node=25980
       4      .7
Encroach Node=25484
       1 4943.37 5035.36
Encroach Node=24853
       4      .7
Encroach Node=24388
       1 4864.16 5023.79
Encroach Node=23741
       4      .7
Encroach Node=23318
       4      .7
Encroach Node=22899
       1 4969.66 5052.28
Encroach Node=22378
       4      .7
Encroach Node=22104
       4      .7
Encroach Node=22006
       4      .7
Encroach Node=21942
       4      .7
Encroach Node=21808
       4      .7
Encroach Node=21460
       4      .7
Encroach Node=21095
       1  4964.9  5025.1
Encroach Node=20526
       1  4969.4  5029.7
Encroach Node=19929
       4      .7
Encroach Node=19302
       1  4968.2  5028.5
Encroach Node=18901
       1 4974.69  5039.5
Encroach Node=18295
       1  4976.2  5068.3
Encroach Node=17830
       1    4915 5029.62
Encroach Node=17534
       1  4960.2  5028.2
Encroach Node=17153
       4      .7
Encroach Node=16835
       1  4978.4  5032.5
Encroach Node=16258
       4      .7
Encroach Node=15825
       1  4971.4  5032.6
Encroach Node=15355
       1  4971.4  5034.8
Encroach Node=14883
       1  4971.2  5031.7
Encroach Node=14297
       1    4973  5037.8
Encroach Node=13847
       1  4960.8  5024.8
Encroach Node=13210
       1  4968.6  5035.9
Encroach Node=12678
       1 4965.87  5034.5
Encroach Node=12398
       4      .7
Encroach Node=11868
       1  4966.8  5028.1
Encroach Node=11456
       4      .7
Encroach Node=11082
       1  4973.3  5036.5
Encroach Node=10636
       4      .7
Encroach Node=10143
       1  4975.5  5054.4
Encroach Node=9664
       1  4963.8  5030.3
Encroach Node=9155
       4      .7
Encroach Node=8402
       1  4955.8  5036.8
Encroach Node=7828
       1  4973.3  5035.9
Encroach Node=7351
       1    4968  5029.3
Encroach Node=6758
       4      .7
Encroach Node=6235
       1  4969.5  5033.3
Encroach Node=5718
       1  4971.1    5041
Encroach Node=5282
       1  4966.3  5023.8
Encroach Node=4803
       1    4960  5036.6
Encroach Node=4400
       4      .7
Encroach Node=3859
       1  4976.2  5033.3
Encroach Node=3272
       1  4972.5    5045
Encroach Node=2847
       1    4964    5033
Encroach Node=2391
       1  4965.3  5027.4
Encroach Node=1899
       1  4957.7  5028.7
Encroach Node=1432
       1  4965.8    5060
Encroach Node=905
       1  4957.5  5035.4
Encroach Node=578
       1  4974.3  5038.2
Encroach Node=32
       1  4952.2 5038.34
BEGIN DESCRIPTION:
Floodway Run
END DESCRIPTION:
Computation Interval=1HOUR
Output Interval=1HOUR
Run HTab= 0
Run UNet= 0
Run PostProcess= 0
UNET Theta= 1
UNET Theta Warmup= 1
UNET ZTol= 0.02
UNET ZSATol= 0.05
UNET MxIter= 20
UNET MaxInSteps= 0
UNET DtIC= 0
UNET DtMin= 0
UNET MaxCRTS= 20
UNET WFStab= 2
UNET SFStab= 1
UNET WFX= 1
UNET SFX= 1
UNET DSS MLevel= 4
UNET DZMax Abort= 100
UNET Convert EG Bridges=-1
UNET Use Existing IB Tables=-1
UNET Froude Reduction=False
UNET Froude Limit= 1
UNET Froude Power= 10
Instantaneous Interval=1HOUR
Write IC File= 0
Echo Input=False
Echo Output=False
Write Detailed= 0
Detailed Automatic Start=False, 10

--- lds_turkey_crk.f01 (steady flow) ---

Flow Title=Floodway
Program Version=3.13
Number of Profiles= 2
Profile Names=100-year,100-FW
River Rch & RM=Turkey Creek,Reach-1         ,50392
    3320    3320
River Rch & RM=Turkey Creek,Reach-1         ,50289
    5820    5820
River Rch & RM=Turkey Creek,Reach-1         ,45833
    5850    5850
River Rch & RM=Turkey Creek,Reach-1         ,39123
    5870    5870
River Rch & RM=Turkey Creek,Reach-1         ,36690
    5870    5870
River Rch & RM=Turkey Creek,Reach-1         ,30472
    5880    5880
River Rch & RM=Turkey Creek,Reach-1         ,25980
    5890    5890
River Rch & RM=Turkey Creek,Reach-1         ,21808
    5960    5960
River Rch & RM=Turkey Creek,Reach-1         ,16835
    6170    6170
River Rch & RM=Turkey Creek,Reach-1         ,13210
    6270    6270
River Rch & RM=Turkey Creek,Reach-1         ,6758
    6300    6300
Boundary for River Rch & Prof#=Turkey Creek,Reach-1         , 1
Up Type= 0
Dn Type= 3
Dn Slope=0.007
Boundary for River Rch & Prof#=Turkey Creek,Reach-1         , 2
Up Type= 0
Dn Type= 3
Dn Slope=0.007
DSS Import GetInterval= 0
DSS Import GetPeak= 0
DSS Import FillOption= 0

--- lds_turkey_crk.g01 (geometry) ---

Geom Title=Existing Conditions
Program Version=3.13

River Reach=Turkey Creek    ,Reach-1
Reach XY= 30
       898433.19       724796.95       899290.83       727650.42
        901110.5       728263.15       901186.83       729470.77
       902439.11       729374.55       905348.77       726381.84
       905976.37       727973.86       907092.69       727756.84
       906846.16       729328.89       908620.47       728585.84
       908657.92       730076.08       910325.89       729215.63
       911496.33       729478.59       910900.12       731752.25
       908272.91       732172.97       908925.97       732737.71
       908475.87       733320.31       909127.89       733458.08
        908492.7       733828.25       909088.98       734353.02
       907512.57       734656.95       907517.82        735427.8
       908948.06       735733.82       907593.54       736744.45
       908430.65       736767.59        907844.8       737689.44
         908784.       737745.61       907703.97       738196.76
       908606.27       738220.95       909327.32       739486.51

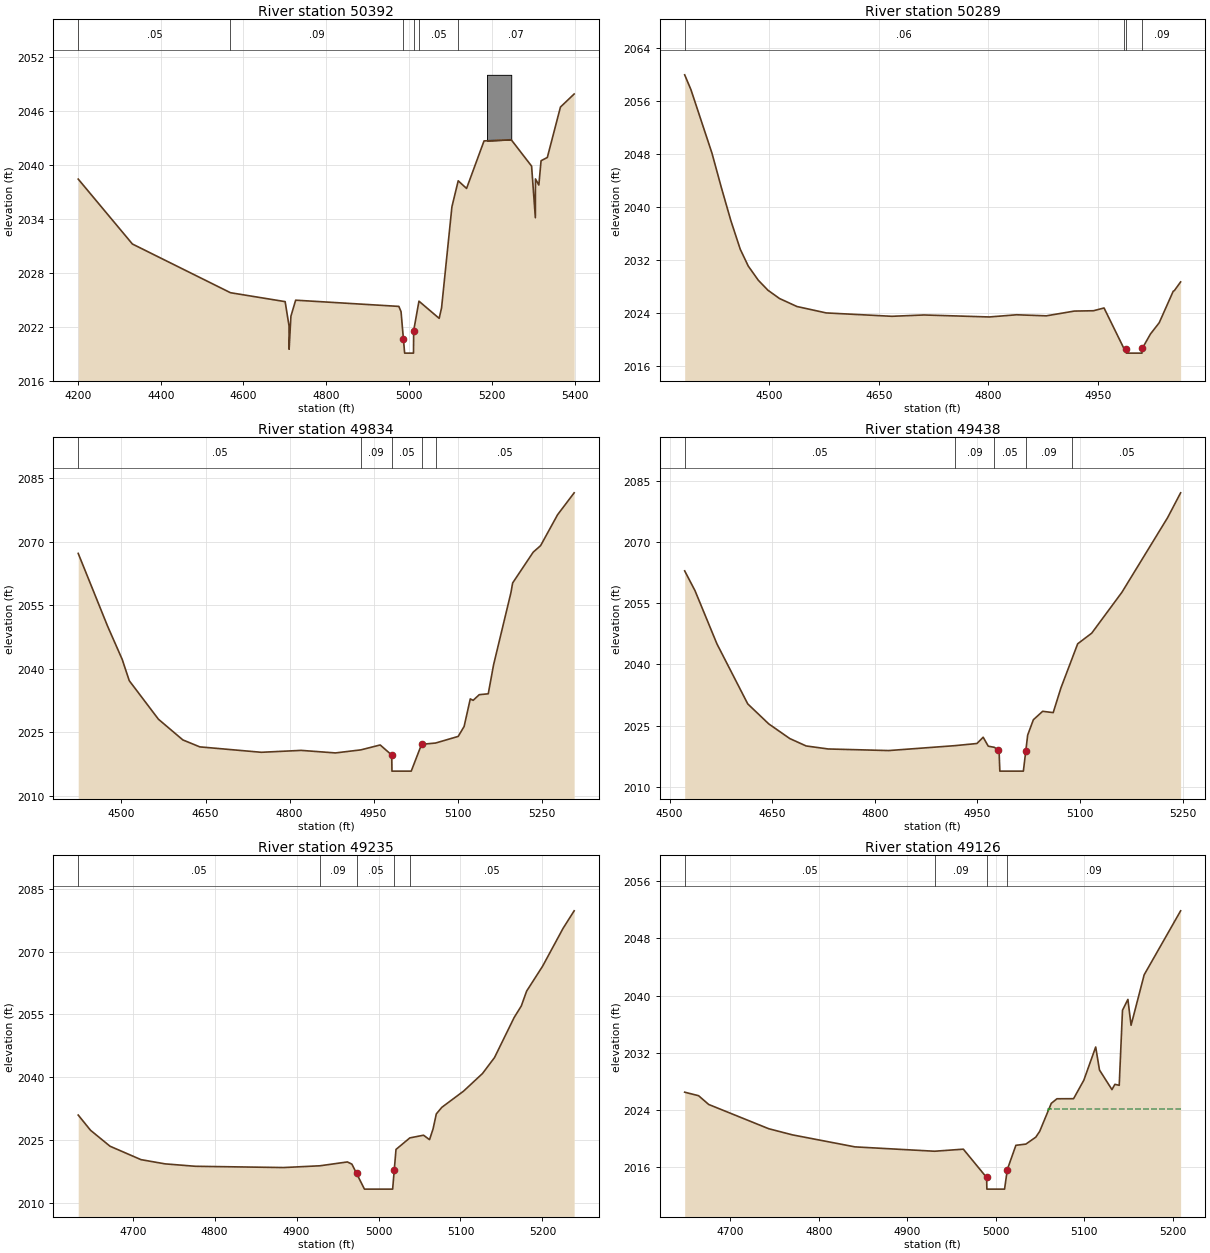
Type RM Length L Ch R = 1 ,50392   ,103,103,103
BEGIN DESCRIPTION:
tie to south turkey
END DESCRIPTION:
XS GIS Cut Line= 6
       897740.42       724432.84       897920.48       724773.54
       897992.78       724820.98       898268.18       724915.96
       898454.19       725019.05       898638.76       725142.85
#Sta/Elev= 30
  4200.7 2038.42  4331.6 2031.21  4568.5  2025.8  4700.6 2024.81    4710 2022.12
  4710.2 2019.52  4714.6  2023.2    4726 2024.97  4975.3 2024.28  4980.6  2023.7
 4986.36 2020.64  4989.3 2019.09  5010.7 2019.09  5011.1 2021.58  5023.9 2024.86
  5072.7 2022.95  5078.5 2024.12  5103.5 2035.34  5118.7 2038.23  5138.9 2037.38
  5181.1 2042.66  5246.8 2042.79    5296 2039.86  5305.1 2034.13  5305.3 2038.44
  5313.5 2037.76  5318.9 2040.46    5334 2040.82  5365.7 2046.42  5398.8 2047.87
#Mann= 6 ,-1 , 0
  4200.7     .05       0  4568.5     .09       0 4986.36     .05       0
  5011.1     .09       0  5023.9     .05       0  5118.7     .07       0
#Block Obstruct= 1 ,-1
  5188.2  5246.8    2050
Bank Sta=4986.36,5011.1
Exp/Cntr=0.3,0.1

Type RM Length L Ch R = 1 ,50289   ,455,455,455
BEGIN DESCRIPTION:
Turkey_Crk_XS107
END DESCRIPTION:
XS GIS Cut Line= 6
       897801.95       725405.77       897857.44       725316.59
       898231.98       725047.08       898265.67       725029.24
        898283.5       725003.48  898322.8100453   724984.810693
#Sta/Elev= 30
  4384.2 2059.97  4392.8 2057.72  4421.5 2048.15  4434.4 2042.94  4447.3 2037.98
  4460.3  2033.6  4471.3 2031.05    4485 2028.91  4498.3 2027.39  4514.1 2026.14
    4538 2024.93  4578.1 2023.96    4668 2023.45    4712 2023.65  4801.6 2023.35
  4838.9 2023.68  4879.7 2023.52    4918 2024.24  4944.2 2024.29  4958.7 2024.71
  4985.6 2018.66  4988.7 2018.49  4989.3 2017.88  5010.7 2017.88  5011.1 2018.59
  5022.2 2020.76  5034.3 2022.48  5053.5 2027.25    5055 2027.33  5063.6 2028.65
#Mann= 4 ,-1 , 0
  4384.2     .06       0  4985.6     .09       0  4988.7     .05       0
  5011.1     .09       0
Bank Sta=4988.7,5011.1
Exp/Cntr=0.3,0.1

Type RM Length L Ch R = 1 ,49834   ,396,396,396
BEGIN DESCRIPTION:
Turkey_Crk_XS106
END DESCRIPTION:
XS GIS Cut Line= 6
       897940.67       725667.35       898065.52       725603.94
       898451.95       725435.49       898539.14       725366.13
       898638.23        725304.7       898733.35       725294.79
#Sta/Elev= 30
  4422.8 2067.26  4475.1 2050.11  4501.4 2042.19  4513.9 2037.19    4566 2028.08
  4609.6 2023.19  4639.8 2021.55  4749.6 2020.27  4820.9 2020.72  4881.9 2020.12
  4927.3 2020.84  4961.8    2022  4982.4 2019.62  4982.8 2015.82  5017.2 2015.82
  5035.7 2022.15  5060.7 2022.46    5101 2024.02  5111.6 2026.37  5122.6 2032.88
  5127.7 2032.54  5138.6 2033.88  5154.7 2034.09  5164.2 2040.95  5195.1 2057.95
  5198.2 2060.27  5234.9 2067.55  5248.1 2069.09  5278.4 2076.39    5308 2081.57
#Mann= 5 ,-1 , 0
  4422.8     .05       0  4927.3     .09       0  4982.4     .05       0
  5035.7     .09       0  5060.7     .05       0
Bank Sta=4982.4,5035.7
Exp/Cntr=0.3,0.1

Type RM Length L Ch R = 1 ,49438   ,203,203,203
BEGIN DESCRIPTION:
Turkey_Crk_XS105
END DESCRIPTION:
XS GIS Cut Line= 6
       898146.77       726010.19       898233.96       725938.85
       898497.53       725829.85       898602.56       725780.31
       898677.86       725752.57       898808.66       725750.59
#Sta/Elev= 30
    4522 2062.91  4537.1 2058.06  4569.1 2045.04  4614.2 2030.31  4644.9 2025.41
  4675.7 2021.81  4699.6    2020  4731.8 2019.26  4820.3 2018.87  4916.9 2020.07
  4949.3  2020.6  4958.4 2022.14  4965.9 2019.94  4974.9 2019.66  4979.4 2019.12
  4981.7 2018.59  4982.8 2013.83  5017.2 2013.83  5020.82018.875  5023.5 2022.66
  5031.8 2026.42  5045.4 2028.49  5060.8 2028.17  5072.1 2034.22  5088.5 2041.46
  5096.6 2045.04  5117.1 2047.64  5161.3 2057.67  5228.1 2075.96  5247.1 2082.04
#Mann= 5 ,-1 , 0
    4522     .05       0  4916.9     .09       0  4974.9     .05       0
  5020.8     .09       0  5088.5     .05       0
Bank Sta=4979.4,5020.8
Exp/Cntr=0.3,0.1

Type RM Length L Ch R = 1 ,49235   ,109,109,109
BEGIN DESCRIPTION:
turkey crk z2
END DESCRIPTION:
XS GIS Cut Line= 2
       898310.18       726133.59       898862.16       725885.45
#Sta/Elev= 30
  4633.5 2030.92  4648.5 2027.29  4672.3 2023.47  4710.1 2020.26  4739.5 2019.25
  4776.6 2018.67  4884.2 2018.37  4928.5 2018.79    4962 2019.71  4967.5 2019.18
  4973.12016.995  4982.8 2013.21  5017.2 2013.21  5019.2 2017.84  5021.3  2022.7
  5038.2 2025.46  5054.9  2026.1  5062.2 2025.04  5066.5 2027.58  5070.5 2031.19
  5077.2 2032.76  5103.8 2036.65  5126.8 2040.84  5141.5 2044.66  5165.5 2054.25
  5174.2    2057  5180.7 2060.55  5200.2 2066.51  5225.2 2075.57  5238.7 2079.75
#Mann= 5 ,-1 , 0
  4633.5     .05       0  4928.5     .09       0  4973.1     .05       0
  5019.2     .09       0  5038.2     .05       0
Bank Sta=4973.1,5019.2
Exp/Cntr=0.5,0.3

Type RM Length L Ch R = 1 ,49126   ,69,69,69
BEGIN DESCRIPTION:
Turkey_Crk_XS104
END DESCRIPTION:
XS GIS Cut Line= 5
       898360.79       726253.94       898471.77       726186.56
       898632.28       726107.29       898784.88       726033.97
       898860.18       726000.28
#Sta/Elev= 30
  4648.4 2026.49  4664.1    2026  4675.6 2024.77  4743.4 2021.38  4770.2 2020.52
  4840.9 2018.84  4930.9 2018.23  4963.4 2018.52  4989.7 2014.56    4990 2012.93
    5010 2012.93  5013.1 2015.67  5022.8 2019.06  5034.1 2019.23  5045.3  2020.2
  5049.7 2021.01  5062.8 2024.93  5069.2 2025.57    5088 2025.58  5099.6 2028.17
    5113 2032.81  5117.3 2029.59  5131.4 2026.85  5134.7 2027.59  5139.6 2027.45
  5143.3 2037.95  5149.4 2039.47    5153 2035.85  5167.8 2042.91    5209 2051.86
#Mann= 4 ,-1 , 0
  4648.4     .05       0  4930.9     .09       0  4989.7     .05       0
  5013.1     .09       0
#XS Ineff= 2 , 0
       0    4941 2015.37    5059       0  2024.1
Permanent Ineff=
       F       F
Bank Sta=4989.7,5013.1
Exp/Cntr=0.5,0.3

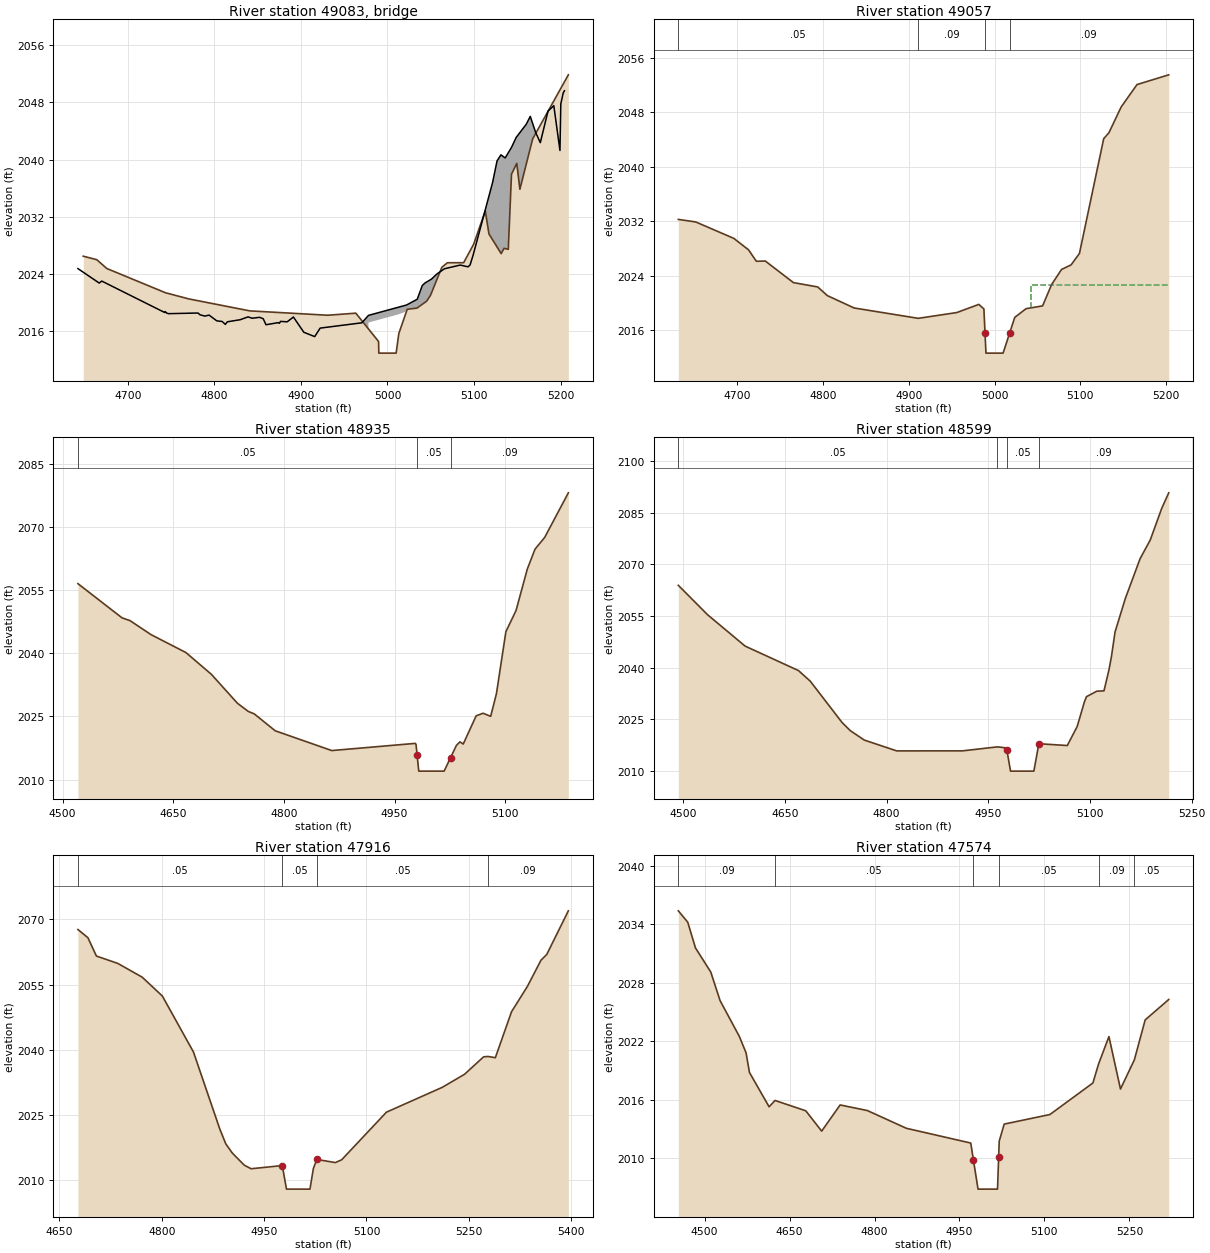
Type RM Length L Ch R = 3 ,49083   ,,,
BEGIN DESCRIPTION:
Turkey_Crk_XS103
Structure ID: Driveway off Turkey Crk Rd
Approximate Survey Structure
END DESCRIPTION:
Bridge Culvert--1,0,-1,-1, 0
Deck Dist Width WeirC Skew NumUp NumDn MinLoCord MaxHiCord MaxSubmerge Is_Ogee
37,12,3,0, 60, 60, , , , 0, 1,1,,
  4642.3  4666.9  4669.8  4742.6  4743.2  4744.9  4747.2    4781  4783.4  4789.1
  4793.8  4802.8  4808.9  4812.7  4814.8  4829.7  4838.9  4843.6  4852.2  4856.4
  4859.6  4873.4  4875.1  4876.4  4884.1  4891.3  4903.3  4915.9  4922.2  4970.4
    4978    4978    5022    5022  5034.4  5040.2  5043.5  5050.7    5057  5065.8
  5084.1    5093  5095.4  5098.9  5121.4  5126.6  5131.1    5136  5143.3  5148.7
  5160.3    5165  5171.3  5176.6  5185.5  5192.2  5199.3  5200.3  5203.1  5204.5
 2024.75 2022.73 2023.01 2018.61 2018.73 2018.53 2018.45 2018.54 2018.29 2018.11
 2018.25 2017.44 2017.36 2016.95 2017.31  2017.6    2018 2017.81 2017.94 2017.74
  2016.9 2017.19 2017.11 2017.37 2017.31 2017.98 2015.85 2015.24 2016.43 2017.17
 2018.21 2018.21 2019.66 2019.66 2020.47 2022.39 2022.76 2023.27 2023.99 2024.73
 2025.25    2025 2025.25 2026.61 2036.78 2039.82 2040.67 2040.23 2041.71  2043.1
 2044.94 2046.05 2043.77 2042.37 2046.79 2047.54 2041.28  2047.8 2049.35 2049.63
    1984    1984    1984    1984    1984    1984    1984    1984    1984    1984
    1984    1984    1984    1984    1984    1984    1984    1984    1984    1984
    1984    1984    1984    1984    1984    1984    1984    1984    1984    1984
    1984 2017.21 2018.66    1984    1984    1984    1984    1984    1984    1984
    1984    1984    1984    1984    1984    1984    1984    1984    1984    1984
    1984    1984    1984    1984    1984    1984    1984    1984    1984    1984
  4642.3  4666.9  4669.8  4742.6  4743.2  4747.2    4781  4783.4  4789.1  4793.8
  4802.8  4808.9  4812.7  4814.8  4829.7  4838.9  4843.6  4852.2  4856.4  4859.6
  4873.4  4875.1  4876.4  4884.1  4891.3  4903.3  4915.9  4922.2    4926  4948.6
  4951.9  4963.9  4970.4    4978    4978    5022    5022  5034.4  5040.2  5065.8
  5084.1    5093  5095.4  5098.9  5121.4  5126.6  5131.1    5136  5143.3  5148.7
  5160.3    5165  5171.3  5176.6  5185.5  5192.2  5199.3  5200.3  5203.1  5204.5
 2024.75 2022.73 2023.01 2018.61 2018.73 2018.45 2018.54 2018.29 2018.11 2018.25
 2017.44 2017.36 2016.95 2017.31  2017.6    2018 2017.81 2017.94 2017.74  2016.9
 2017.19 2017.11 2017.37 2017.31 2017.98 2015.85 2015.24 2016.43  2016.5  2014.8
    2015 2017.12 2017.17 2018.21 2018.21 2019.66 2019.66 2020.47 2022.39 2024.73
 2025.25    2025 2025.25 2026.61 2036.78 2039.82 2040.67 2040.23 2041.71  2043.1
 2044.94 2046.05 2043.77 2042.37 2046.79 2047.54 2041.28  2047.8 2049.35 2049.63
    1984    1984    1984    1984    1984    1984    1984    1984    1984    1984
    1984    1984    1984    1984    1984    1984    1984    1984    1984    1984
    1984    1984    1984    1984    1984    1984    1984    1984    1984    1984
    1984    1984    1984    1984 2017.21 2018.66    1984    1984    1984    1984
    1984    1984    1984    1984    1984    1984    1984    1984    1984    1984
    1984    1984    1984    1984    1984    1984    1984    1984    1984    1984
Abutment Skew #Up #Dn= , 2 , 2
    4978  4980.5
    2012 2016.06
    4978  4980.5
    2012 2019.75
Abutment Skew #Up #Dn= , 2 , 2
  5019.5    5022
 2017.96    2012
  5019.5    5022
 2014.84    2012
BR Coef= 1 , 1 , 0 ,1.25, 0 ,,,0.8,0,2,0,
WSPro=,,,, 1 ,,,, 0 ,,,, 0 ,,,,-1 ,-1 ,-1 , 0 , 0 , 0 , 0 , 0
BC Design=,, 0 ,, 0 ,,,,,,
BC HTab HWMax=2051.86

Type RM Length L Ch R = 1 ,49057   ,122,122,122
BEGIN DESCRIPTION:
Turkey_Crk_XS102
END DESCRIPTION:
XS GIS Cut Line= 4
       898376.64       726311.41       898592.65       726210.34
       898735.33       726131.07       898881.98       726043.88
#Sta/Elev= 30
    4631 2032.29  4651.3 2031.92  4695.7 2029.51  4712.9 2027.83  4722.1 2026.14
  4732.5 2026.18  4765.3 2023.01  4793.7 2022.37  4804.9  2021.1  4836.2 2019.28
    4911 2017.76    4956 2018.61  4981.7 2019.81  4987.6 2019.14  4988.92015.625
    4990 2012.65    5010 2012.65  5017.52015.545  5023.6  2017.9  5036.8 2019.18
  5056.1 2019.59  5066.6 2022.72  5078.2 2024.94  5089.4 2025.62  5099.1 2027.29
  5127.4 2044.15  5133.5 2045.02  5147.8 2048.81  5166.3  2052.1  5203.3 2053.53
#Mann= 4 ,-1 , 0
    4631     .05       0    4911     .09       0  4988.9     .05       0
  5017.5     .09       0
#XS Ineff= 2 , 0
       0    4958 2016.08    5042       0 2022.59
Permanent Ineff=
       F       F
Bank Sta=4988.9,5017.5
Exp/Cntr=0.5,0.3

Type RM Length L Ch R = 1 ,48935   ,336,336,336
BEGIN DESCRIPTION:
turkey crk z3
END DESCRIPTION:
XS GIS Cut Line= 4
       898408.09       726530.27       898728.81       726295.63
       898811.52       726214.61       898939.81       726133.59
#Sta/Elev= 30
  4520.7 2056.58  4580.5 2048.45  4591.3 2047.79    4620 2044.44  4667.1  2040.2
  4701.7 2035.01  4736.9 2028.15  4751.7 2026.19  4759.8 2025.61  4788.1  2021.6
  4864.8 2016.89  4978.2  2018.6  4979.1 2018.33  4980.52015.935  4982.8    2012
  5017.2    2012  5025.92015.199  5033.9 2018.14  5038.7 2018.96  5043.1 2018.44
  5060.6 2025.15    5070 2025.77  5080.3 2025.03  5088.1 2030.41  5100.9 2045.15
  5114.7  2050.2  5129.9 2060.02  5140.4 2064.78  5153.5 2067.57  5185.6 2078.18
#Mann= 3 ,-1 , 0
  4520.7     .05       0  4980.5     .05       0  5025.9     .09       0
Bank Sta=4980.5,5025.9
Exp/Cntr=0.3,0.1

Type RM Length L Ch R = 1 ,48599   ,683,683,683
BEGIN DESCRIPTION:
Turkey_Crk_XS101
END DESCRIPTION:
XS GIS Cut Line= 6
       898471.77       726755.31       898590.67       726689.92
       898751.19       726598.76       898983.05       726511.56
       899068.26       726483.82       899127.71       726456.07
#Sta/Elev= 30
  4492.9 2063.93    4536  2055.4  4591.4 2046.29  4670.1 2039.19  4687.5 2036.11
  4734.4 2024.11  4746.7 2021.72  4767.2 2019.02    4815 2015.88  4911.8 2015.89
  4963.5 2017.05  4973.9 2016.81  4977.4 2016.16  4982.8 2010.01  5017.2 2010.01
  5024.6 2017.96  5066.5 2017.44  5081.1 2022.96  5091.8 2030.15  5094.8 2031.62
    5110  2033.2  5120.6 2033.31    5128 2039.43  5131.8 2043.49  5136.9 2050.37
  5152.2 2060.17  5173.9 2071.67  5188.9 2077.11  5205.7 2086.24  5216.1 2090.77
#Mann= 4 ,-1 , 0
  4492.9     .05       0  4963.5     .09       0  4977.4     .05       0
  5024.6     .09       0
Bank Sta=4977.4,5024.6
Exp/Cntr=0.3,0.1

Type RM Length L Ch R = 1 ,47916   ,342,342,342
BEGIN DESCRIPTION:
Turkey_Crk_XS100
END DESCRIPTION:
XS GIS Cut Line= 6
       898778.93        727298.3       898868.11       727244.79
       899002.86       727219.03       899133.66       727159.58
       899214.91        727070.4       899381.37       726939.61
#Sta/Elev= 30
  4677.1 2067.68  4691.7  2065.8  4704.2 2061.58  4735.6 2059.88  4771.3 2056.72
  4800.8 2052.39  4846.4 2039.52    4885 2021.81  4893.8 2018.39  4903.3 2016.28
  4920.9 2013.48  4930.9 2012.66  4976.6 2013.39  4982.8 2007.97  5017.2 2007.97
  5022.2 2012.74  5027.3 2014.79  5054.4 2014.08  5063.6 2014.71  5129.3 2025.67
  5211.2 2031.39  5243.7 2034.38  5271.7  2038.4  5278.2 2038.48  5288.9  2038.2
  5312.6 2048.76  5335.9  2054.6  5355.8 2060.62  5364.3 2061.96  5395.9 2071.98
#Mann= 4 ,-1 , 0
  4677.1     .05       0  4976.6     .05       0  5027.3     .05       0
  5278.2     .09       0
Bank Sta=4976.6,5027.3
Exp/Cntr=0.3,0.1

Type RM Length L Ch R = 1 ,47574   ,129,129,129
BEGIN DESCRIPTION:
turkey crk z4
END DESCRIPTION:
XS GIS Cut Line= 5
       898703.49         727484.       898946.56       727554.89
       899270.66       727473.87        899336.5       727387.78
       899388.82       727225.73
#Sta/Elev= 30
  4453.6 2035.36  4470.2  2034.2  4483.9 2031.56  4510.9 2029.09  4527.3 2026.17
  4561.4 2022.49  4573.2 2020.82  4579.2 2018.81  4613.9 2015.29  4624.3 2015.94
  4678.7 2014.88  4706.7  2012.8  4739.3 2015.48  4787.2 2014.91  4856.3 2013.09
  4969.9 2011.58 4974.582009.868  4982.8 2006.86  5017.2 2006.86  5019.2 2010.14
  5020.2 2011.78    5029 2013.52  5109.7  2014.5  5185.6 2017.73  5195.7 2019.69
  5213.9 2022.48  5234.3 2017.11  5258.8  2020.1  5277.9 2024.19  5319.5 2026.28
#Mann= 6 ,-1 , 0
  4453.6     .09       0  4624.3     .05       0 4974.58     .05       0
  5019.2     .05       0  5195.7     .09       0  5258.8     .05       0
Bank Sta=4974.58,5019.2
Exp/Cntr=0.5,0.3

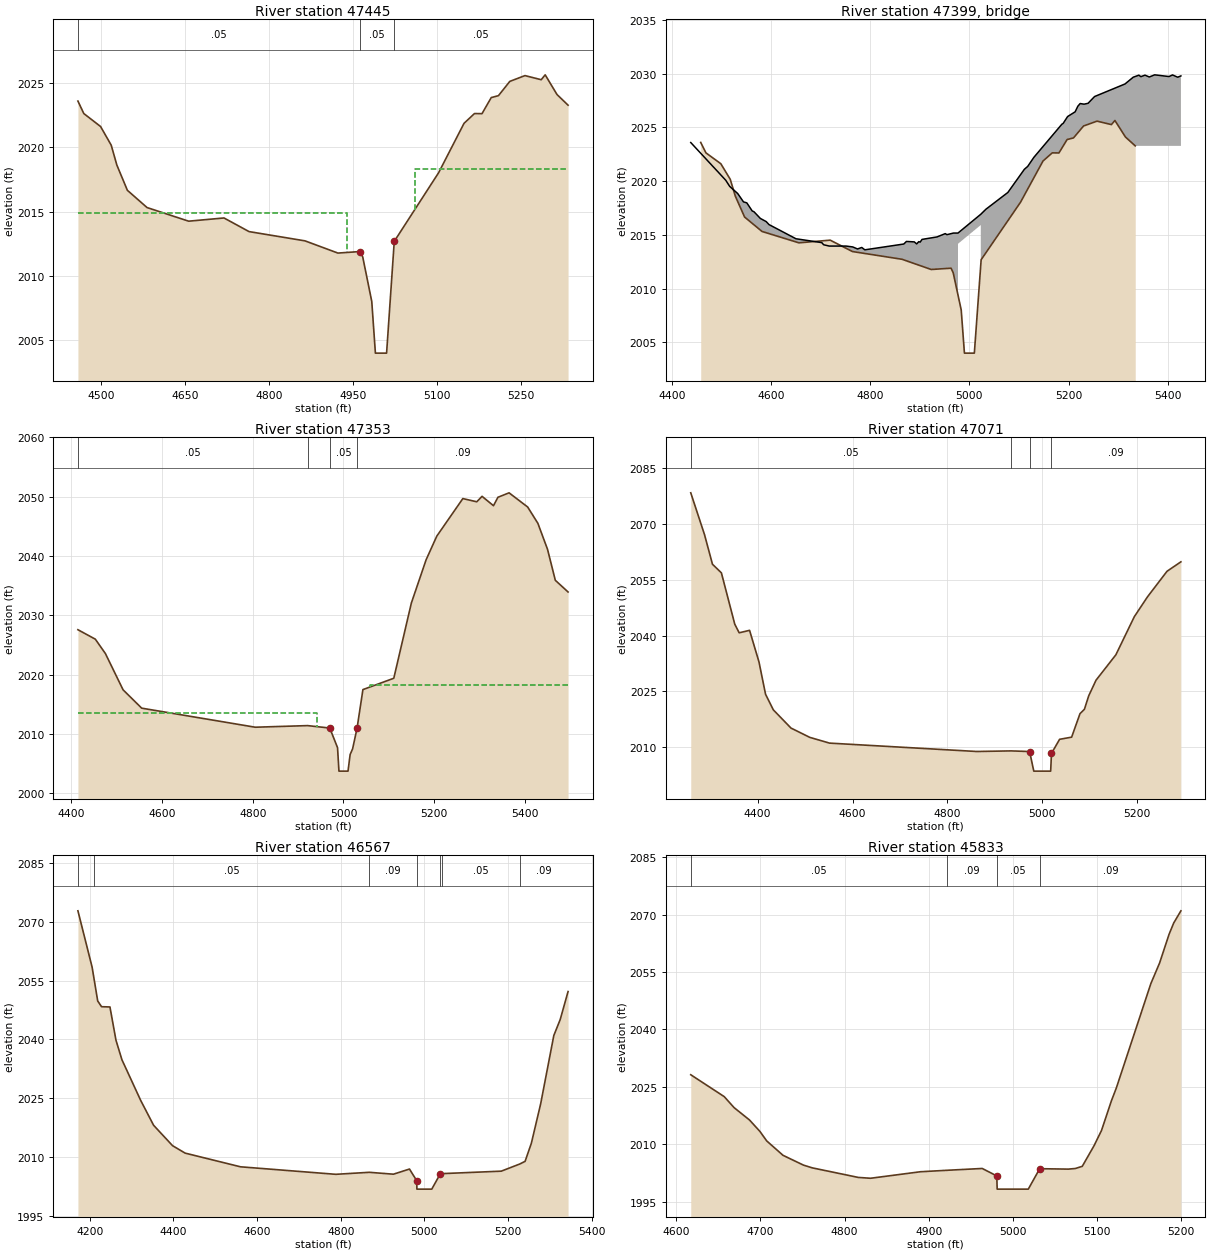
Type RM Length L Ch R = 1 ,47445   ,92,92,92
BEGIN DESCRIPTION:
Turkey_Crk_XS99
END DESCRIPTION:
XS GIS Cut Line= 6
       898743.26       727712.48        899139.6       727651.04
       899325.88       727583.67       899373.44       727506.38
       899395.24       727411.26       899409.11       727324.06
#Sta/Elev= 30
  4458.4  2023.6  4468.9 2022.63  4498.9 2021.62  4517.9 2020.17    4528 2018.62
  4546.8 2016.66  4581.9 2015.32  4656.3 2014.26  4719.4 2014.51  4764.2 2013.45
  4864.2 2012.73    4923 2011.78  4963.1  2011.9  4967.4 2011.47  4983.5 2008.02
    4990    2004    5010    2004  5023.7 2012.69    5103 2018.03  5148.4 2021.87
  5167.1 2022.63  5180.5 2022.62    5197 2023.87  5209.9 2024.02  5230.2 2025.13
  5257.3 2025.58  5286.3 2025.26  5293.4 2025.64  5314.5 2024.11  5334.3 2023.28
#Mann= 3 ,-1 , 0
  4458.4     .05       0  4963.1     .05       0  5023.7     .05       0
#XS Ineff= 2 , 0
       0    4940 2014.91    5060       0 2018.33
Permanent Ineff=
       F       F
Bank Sta=4963.1,5023.7
Exp/Cntr=0.5,0.3

Type RM Length L Ch R = 3 ,47399   ,,,
BEGIN DESCRIPTION:
Turkey_Crk_XS98
Structure ID: Turkey Creek Rd SR1608
Approximate Survey Structure
END DESCRIPTION:
Bridge Culvert--1,0,-1,-1, 0
Deck Dist Width WeirC Skew NumUp NumDn MinLoCord MaxHiCord MaxSubmerge Is_Ogee
37,18,3,0, 60, 60, , , , 0, 1,1,,
  4438.3  4508.7  4516.8  4532.9  4544.6  4551.3  4562.1  4565.8  4578.6  4590.3
    4596  4650.4  4702.4  4706.2  4717.5  4751.5  4764.8  4774.5    4783  4789.2
  4867.7  4873.1  4888.9  4893.7  4897.9  4900.8  4904.5  4934.7  4951.4  4954.6
  4967.9    4977    4977    5023    5023  5033.1  5077.6  5110.8  5117.5  5130.1
  5186.5    5189    5198  5213.2  5218.6  5223.3  5231.1  5239.2  5252.3  5313.7
  5330.3  5341.7  5345.6    5354  5362.7  5373.5  5402.4  5409.5  5419.9  5426.4
 2023.59 2020.09 2019.51 2018.85 2018.07 2017.98 2017.23 2017.15 2016.53 2016.24
 2015.96 2014.64 2014.28 2014.08 2013.96 2013.96 2013.88 2013.69 2013.83 2013.61
 2014.15 2014.39 2014.35 2014.16 2014.37 2014.33 2014.58 2014.81 2015.12 2015.02
 2015.17 2015.17 2015.17 2016.92 2016.92 2017.38 2018.95  2021.1 2021.37 2022.22
  2025.3 2025.37 2026.01 2026.45 2026.97 2027.22 2027.16 2027.24 2027.87 2029.04
 2029.67 2029.86 2029.72 2029.86 2029.69 2029.89 2029.73 2029.88 2029.67 2029.79
    1982    1982    1982    1982    1982    1982    1982    1982    1982    1982
    1982    1982    1982    1982    1982    1982    1982    1982    1982    1982
    1982    1982    1982    1982    1982    1982    1982    1982    1982    1982
    1982    1982 2014.17 2015.92    1982    1982    1982    1982    1982    1982
    1982    1982    1982    1982    1982    1982    1982    1982    1982    1982
    1982    1982    1982    1982    1982    1982    1982    1982    1982    1982
  4438.3  4508.7  4516.8  4532.9  4544.6  4551.3  4562.1  4565.8  4578.6  4590.3
    4596  4650.4  4702.4  4706.2  4717.5  4751.5  4764.8  4774.5    4783  4789.2
  4867.7  4873.1  4888.9  4893.7  4897.9  4900.8  4904.5  4934.7  4951.4  4954.6
  4967.9    4977    4977    5023    5023  5033.1  5077.6  5110.8  5117.5  5130.1
  5186.5    5189    5198  5213.2  5218.6  5223.3  5231.1  5239.2  5252.3  5313.7
  5330.3  5341.7  5345.6    5354  5362.7  5373.5  5402.4  5409.5  5419.9  5426.4
 2023.59 2020.09 2019.51 2018.85 2018.07 2017.98 2017.23 2017.15 2016.53 2016.24
 2015.96 2014.64 2014.28 2014.08 2013.96 2013.96 2013.88 2013.69 2013.83 2013.61
 2014.15 2014.39 2014.35 2014.16 2014.37 2014.33 2014.58 2014.81 2015.12 2015.02
 2015.17 2015.17 2015.17 2016.92 2016.92 2017.38 2018.95  2021.1 2021.37 2022.22
  2025.3 2025.37 2026.01 2026.45 2026.97 2027.22 2027.16 2027.24 2027.87 2029.04
 2029.67 2029.86 2029.72 2029.86 2029.69 2029.89 2029.73 2029.88 2029.67 2029.79
    1982    1982    1982    1982    1982    1982    1982    1982    1982    1982
    1982    1982    1982    1982    1982    1982    1982    1982    1982    1982
    1982    1982    1982    1982    1982    1982    1982    1982    1982    1982
    1982    1982 2014.17 2015.92    1982    1982    1982    1982    1982    1982
    1982    1982    1982    1982    1982    1982    1982    1982    1982    1982
    1982    1982    1982    1982    1982    1982    1982    1982    1982    1982
BR Coef= 1 , 1 , 0 ,1.25, 0 ,,,0.8,0,2,0,
WSPro=,,,, 1 ,,,, 0 ,,,, 0 ,,,,-1 ,-1 ,-1 , 0 , 0 , 0 , 0 , 0
BC Design=,, 0 ,, 0 ,,,,,,
BC HTab HWMax=2025.64

Type RM Length L Ch R = 1 ,47353   ,282,282,282
BEGIN DESCRIPTION:
Turkey_Crk_XS97
END DESCRIPTION:
XS GIS Cut Line= 6
        898739.3       727791.75       899208.96       727724.37
       899321.92       727682.75       899426.95       727597.54
       899482.44       727512.32       899510.18       727266.59
#Sta/Elev= 30
    4415 2027.58  4453.3 2025.99  4475.5 2023.57  4514.5 2017.45  4555.5 2014.36
  4805.6 2011.15    4921 2011.42  4969.8 2011.01  4986.9  2007.7    4990 2003.75
    5010 2003.75  5014.6 2006.54  5020.1 2007.51  5029.9 2010.99  5042.8 2017.49
  5110.8  2019.4  5149.5 2032.08    5182 2039.37  5205.5 2043.35  5262.9 2049.68
  5293.6 2049.14  5305.2 2050.06  5330.4 2048.48  5340.2  2049.9  5364.7 2050.65
  5405.7 2048.26  5428.2 2045.51  5449.5 2041.12  5466.6 2035.91  5494.7 2033.94
#Mann= 4 ,-1 , 0
    4415     .05       0    4921     .09       0  4969.8     .05       0
  5029.9     .09       0
#XS Ineff= 2 , 0
       0    4941  2013.6    5059       0 2018.29
Permanent Ineff=
       F       F
Bank Sta=4969.8,5029.9
Exp/Cntr=0.5,0.3

Type RM Length L Ch R = 1 ,47071   ,504,504,504
BEGIN DESCRIPTION:
Turkey_Crk_XS96
END DESCRIPTION:
XS GIS Cut Line= 6
       899068.26       728485.34       899193.11        728295.1
       899480.45       727912.63       899553.78       727849.21
       899591.43       727787.78       899698.44       727670.86
#Sta/Elev= 30
  4258.9 2078.32  4287.9  2067.1  4304.7 2059.15  4323.5 2056.84  4351.7 2043.06
    4361 2040.75  4382.9 2041.41  4402.7 2032.96  4416.6 2024.26    4433 2020.07
  4470.2 2015.18  4509.9 2012.68  4551.5 2011.14  4861.8 2008.89  4934.1 2009.05
  4973.4 2008.88  4982.2 2003.62  5017.8 2003.62  5019.5 2008.37  5036.6 2012.16
    5062 2012.74  5079.6 2019.04  5088.9 2020.21    5098 2023.83  5113.4 2028.02
  5155.3 2034.85  5194.2 2045.08  5221.7 2050.36  5263.1 2057.26  5292.4  2059.8
#Mann= 4 ,-1 , 0
  4258.9     .05       0  4934.1     .09       0  4973.4     .05       0
  5019.5     .09       0
Bank Sta=4973.4,5019.5
Exp/Cntr=0.3,0.1

Type RM Length L Ch R = 1 ,46567   ,734,734,734
BEGIN DESCRIPTION:
Turkey_Crk_XS95
END DESCRIPTION:
XS GIS Cut Line= 6
       899635.03       728824.22       899690.52       728768.73
       899747.99       728600.28       899960.03       728126.65
       899971.92       727857.14        899995.7       727732.29
#Sta/Elev= 30
  4171.5 2072.74  4205.4 2058.43  4209.9 2055.54  4218.8 2049.81    4228 2048.34
  4248.1 2048.28  4262.5 2039.82  4276.7 2034.86  4321.7 2024.48  4352.5 2018.17
  4397.9 2012.97    4428 2011.08  4560.4  2007.6  4788.3 2005.69  4868.5  2006.2
  4926.1 2005.72  4964.5 2007.03    4982 2004.04  4982.2 2001.92  5017.8 2001.92
  5038.4 2005.86  5041.5 2005.86    5184 2006.49  5228.2 2008.31    5241 2008.99
    5256  2013.6  5278.2  2023.6  5309.7 2041.01  5324.9 2045.05  5343.8  2052.2
#Mann= 7 ,-1 , 0
  4171.5     .09       0  4209.9     .05       0  4868.5     .09       0
    4982     .05       0  5038.4     .09       0  5041.5     .05       0
  5228.2     .09       0
Bank Sta=4982,5038.4
Exp/Cntr=0.3,0.1

Type RM Length L Ch R = 1 ,45833   ,585,585,585
BEGIN DESCRIPTION:
Turkey_Crk_XS94
END DESCRIPTION:
XS GIS Cut Line= 6
       900699.21       728458.59       900677.01       728317.49
       900684.94       728108.22       900680.18       727997.25
       900661.16       727925.91       900650.06       727881.52
#Sta/Elev= 30
  4617.1 2028.14  4656.9 2022.42  4668.6 2019.55    4687 2016.31  4699.4 2013.31
  4707.4 2010.85  4726.8 2007.08  4751.1 2004.52  4761.6  2003.8  4816.3  2001.3
  4830.9 2001.08  4890.1 2002.78  4921.5 2003.16  4963.7 2003.64    4981  2001.7
  4981.5 1998.24  5018.5 1998.24  5032.1 2003.58  5066.1 2003.47  5074.4 2003.63
  5082.7  2004.2  5096.8 2009.63  5105.6 2013.59  5117.4 2021.35  5123.2 2024.68
  5164.3 2051.99  5174.6 2057.32  5185.9 2064.84  5191.4 2067.79    5200 2070.99
#Mann= 4 ,-1 , 0
  4617.1     .05       0  4921.5     .09       0    4981     .05       0
  5032.1     .09       0
Bank Sta=4981,5032.1
Exp/Cntr=0.3,0.1

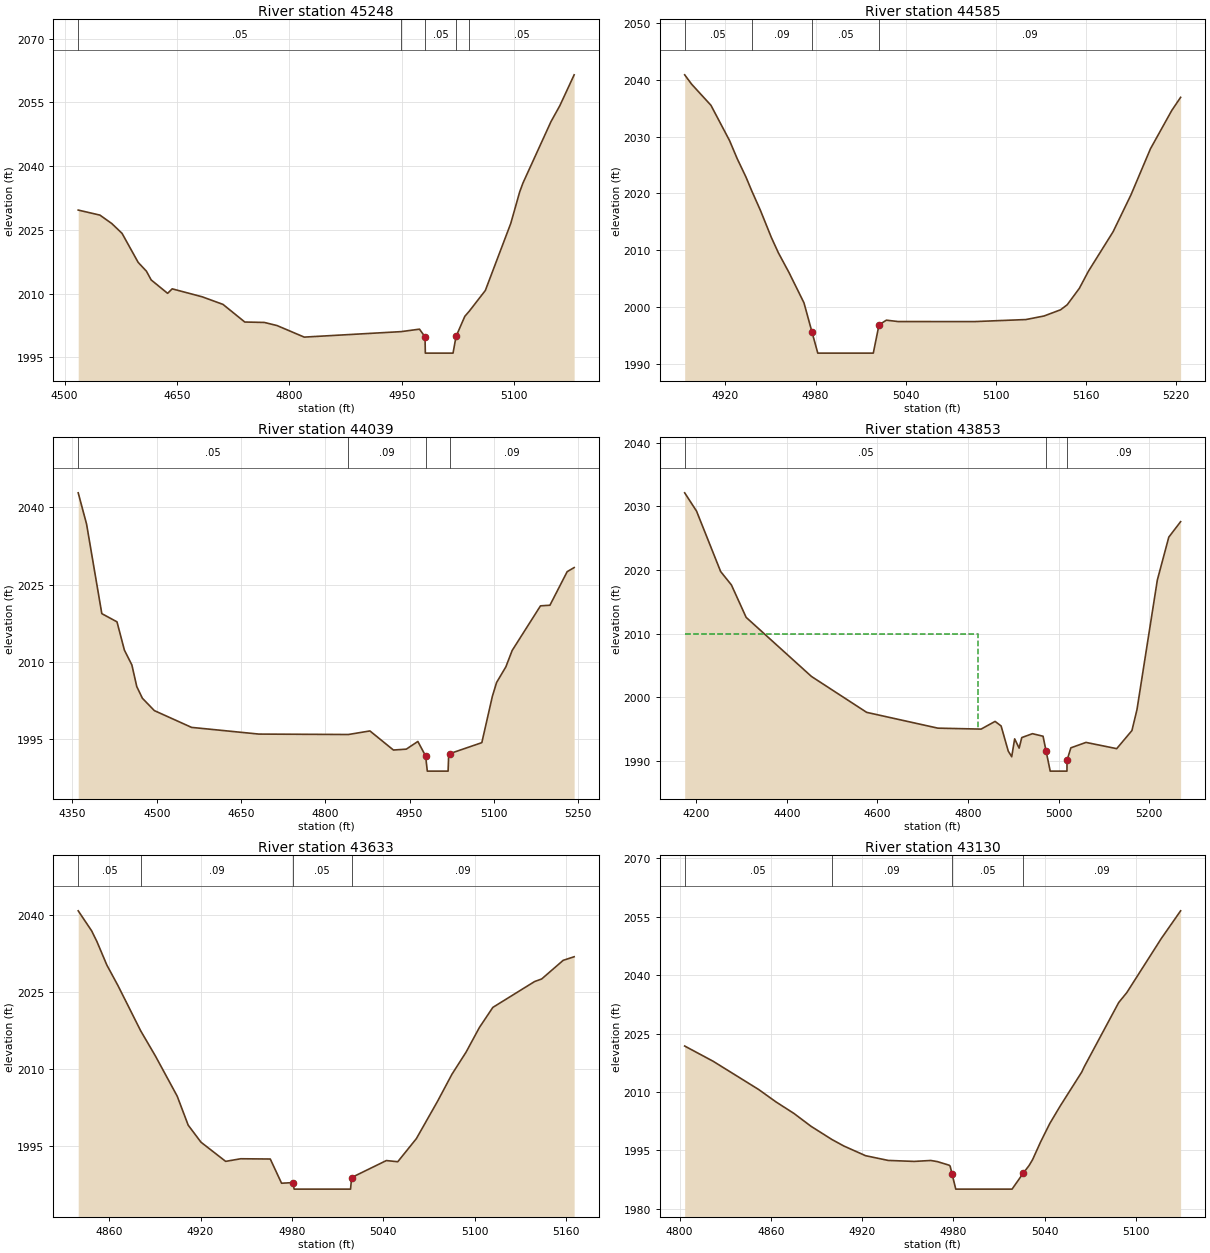
Type RM Length L Ch R = 1 ,45248   ,663,663,663
BEGIN DESCRIPTION:
Turkey_Crk_XS93
END DESCRIPTION:
XS GIS Cut Line= 6
       900697.62       728485.54       900830.79       728437.98
       901128.84       728350.79       901173.23       728334.93
       901260.43         728327.       901327.01       728361.88
#Sta/Elev= 30
  4518.3 2029.64  4547.3 2028.45  4563.1 2026.47  4576.8 2024.16  4598.3 2017.33
  4609.3 2015.26  4615.7 2013.19  4637.6 2010.04  4643.7  2011.1  4683.7 2009.23
  4711.5 2007.44  4740.6 2003.29  4766.7 2003.19  4783.6 2002.46  4819.9 1999.74
  4949.2 2001.03  4973.7 2001.61  4981.1  1999.8  4981.5 1995.97  5018.5 1995.97
  5022.5 1999.89  5034.2 2004.63  5040.1 2005.83  5061.6 2010.72  5095.5 2026.49
  5107.4  2033.9  5111.8 2036.01  5149.2 2050.46    5161 2054.21  5180.1 2061.47
#Mann= 5 ,-1 , 0
  4518.3     .05       0  4949.2     .09       0  4981.1     .05       0
  5022.5     .09       0  5040.1     .05       0
Bank Sta=4981.1,5022.5
Exp/Cntr=0.3,0.1

Type RM Length L Ch R = 1 ,44585   ,546,546,546
BEGIN DESCRIPTION:
Turkey_Crk_XS92
END DESCRIPTION:
XS GIS Cut Line= 5
       900933.84        728956.4       900995.67       728910.42
       901047.99       728859.69       901120.91       728794.69
       901195.43       728758.22
#Sta/Elev= 30
  4892.8  2040.9  4897.4 2039.26  4910.3 2035.53  4922.7 2029.31  4927.8 2026.12
  4933.6  2022.9  4937.6 2020.38  4943.3 2016.99  4950.6  2012.2  4955.3 2009.49
  4962.3 2006.05  4972.3  2000.7  4977.6 1995.59  4981.5 1991.83  5018.5 1991.83
  5022.3 1996.81  5027.2 1997.64    5035  1997.4  5085.9 1997.39  5120.2 1997.75
  5132.3 1998.38  5143.3 1999.47  5147.7 2000.35  5155.8 2003.25  5161.9 2006.29
  5178.3 2013.23  5190.2 2019.73  5203.2 2027.86  5217.4 2034.62  5223.3 2036.93
#Mann= 4 ,-1 , 0
  4892.8     .05       0  4937.6     .09       0  4977.6     .05       0
  5022.3     .09       0
Bank Sta=4977.6,5022.3
Exp/Cntr=0.3,0.1

Type RM Length L Ch R = 1 ,44039   ,186,186,186
BEGIN DESCRIPTION:
Turkey_Crk_XS91
END DESCRIPTION:
XS GIS Cut Line= 6
       900653.23       729860.05       900765.79       729753.83
       901044.82       729398.71       901082.86       729311.52
       901141.52       729276.64       901212.86       729189.44
#Sta/Elev= 30
  4360.3 2042.79  4375.2 2036.72  4402.3 2019.37  4429.3 2017.78  4442.5  2012.3
  4455.8 2009.42  4464.5 2005.23  4474.5 2002.97  4495.8 2000.57    4562 1997.32
  4681.8 1996.02  4841.1 1995.94  4879.4 1996.63  4921.2 1992.93  4944.1  1993.1
  4964.7 1994.59  4978.5 1991.77  4981.5 1988.84  5018.5 1988.84  5019.6 1992.18
  5021.8 1992.24  5078.5 1994.36  5097.3 2003.36  5104.8 2006.03  5121.3 2009.06
  5132.5 2012.23  5182.9 2020.88  5199.7    2021  5230.4 2027.51  5242.8  2028.3
#Mann= 4 ,-1 , 0
  4360.3     .05       0  4841.1     .09       0  4978.5     .05       0
  5021.8     .09       0
Bank Sta=4978.5,5021.8
Exp/Cntr=0.3,0.1

Type RM Length L Ch R = 1 ,43853   ,220,220,220
BEGIN DESCRIPTION:
turkey crk z5
END DESCRIPTION:
XS GIS Cut Line= 3
       901233.82       730283.57        901166.3       730111.39
        901223.7       729203.24
#Sta/Elev= 30
  4174.5 2032.11  4200.7 2029.24  4253.9 2019.75  4277.7 2017.64  4310.2 2012.55
  4454.4 2003.27  4576.3 1997.63  4733.5 1995.15  4828.9    1995  4859.8 1996.21
  4873.1 1995.49  4888.9 1991.54  4896.5 1990.66    4903 1993.47  4912.9 1992.01
  4918.7 1993.67  4942.3 1994.28  4965.7 1993.88  4972.21991.626  4981.5  1988.4
  5018.5  1988.4  5018.6 1990.09  5027.1 1992.06  5060.5 1992.91  5128.3 1991.93
  5161.9 1994.77    5173 1998.04    5218 2018.41  5243.3 2025.15  5269.4 2027.58
#Mann= 3 ,-1 , 0
  4174.5     .05       0  4972.2     .05       0  5018.6     .09       0
#XS Ineff= 2 , 0
       0  4822.2    2010               0
Permanent Ineff=
       F       F
Bank Sta=4972.2,5018.6
Exp/Cntr=0.3,0.1

Type RM Length L Ch R = 1 ,43633   ,503,503,503
BEGIN DESCRIPTION:
Turkey_Crk_XS90
END DESCRIPTION:
XS GIS Cut Line= 5
       901426.89       729420.91       901368.23       729336.88
       901287.38       729271.88       901254.08       729200.54
       901239.82       729162.49
#Sta/Elev= 30
  4839.7 2040.91  4848.5 2037.02    4852 2034.91  4858.5 2030.34  4865.9 2026.28
  4880.7 2017.53  4890.5 2012.55  4904.7 2004.78  4911.9 1999.13  4920.3 1995.81
  4936.5 1992.07  4946.4 1992.58  4965.8 1992.53  4973.2 1987.81  4980.5 1987.93
  4981.5 1986.66  5018.5 1986.66  5019.2 1988.92    5042 1992.23  5049.5    1992
  5061.7  1996.5  5075.7 2003.83  5085.1 2009.07  5094.3 2013.34  5103.1 2018.17
  5111.9 2022.08  5139.3 2027.12    5144 2027.63  5158.1 2031.26  5165.3 2031.96
#Mann= 4 ,-1 , 0
  4839.7     .05       0  4880.7     .09       0  4980.5     .05       0
  5019.2     .09       0
Bank Sta=4980.5,5019.2
Exp/Cntr=0.3,0.1

Type RM Length L Ch R = 1 ,43130   ,471,471,471
BEGIN DESCRIPTION:
Turkey_Crk_XS89
END DESCRIPTION:
XS GIS Cut Line= 6
       901728.11       729241.76       901747.13       729122.86
       901751.89       729068.96       901743.96       729027.74
       901740.79       728983.35       901742.38       728918.35
#Sta/Elev= 30
  4803.3 2021.82    4822 2017.91  4851.9 2010.66  4863.3 2007.47  4875.1 2004.51
  4886.4 2001.19    4900 1997.83  4907.9 1996.14  4922.2 1993.65  4937.1 1992.43
  4954.2 1992.18  4965.1 1992.42  4969.4 1992.13  4977.2  1991.2  4977.8 1990.97
  4979.11988.893  4981.5 1985.06  5018.5 1985.06  5025.8 1989.13  5029.7 1991.13
    5032 1992.64  5037.1 1997.05  5043.2 2001.85  5050.1 2006.38  5064.3 2015.13
    5066 2016.53  5088.6 2032.99  5093.9 2035.53  5116.6 2049.44  5129.3 2056.55
#Mann= 4 ,-1 , 0
  4803.3     .05       0    4900     .09       0  4979.1     .05       0
  5025.8     .09       0
Bank Sta=4979.1,5025.8
Exp/Cntr=0.3,0.1