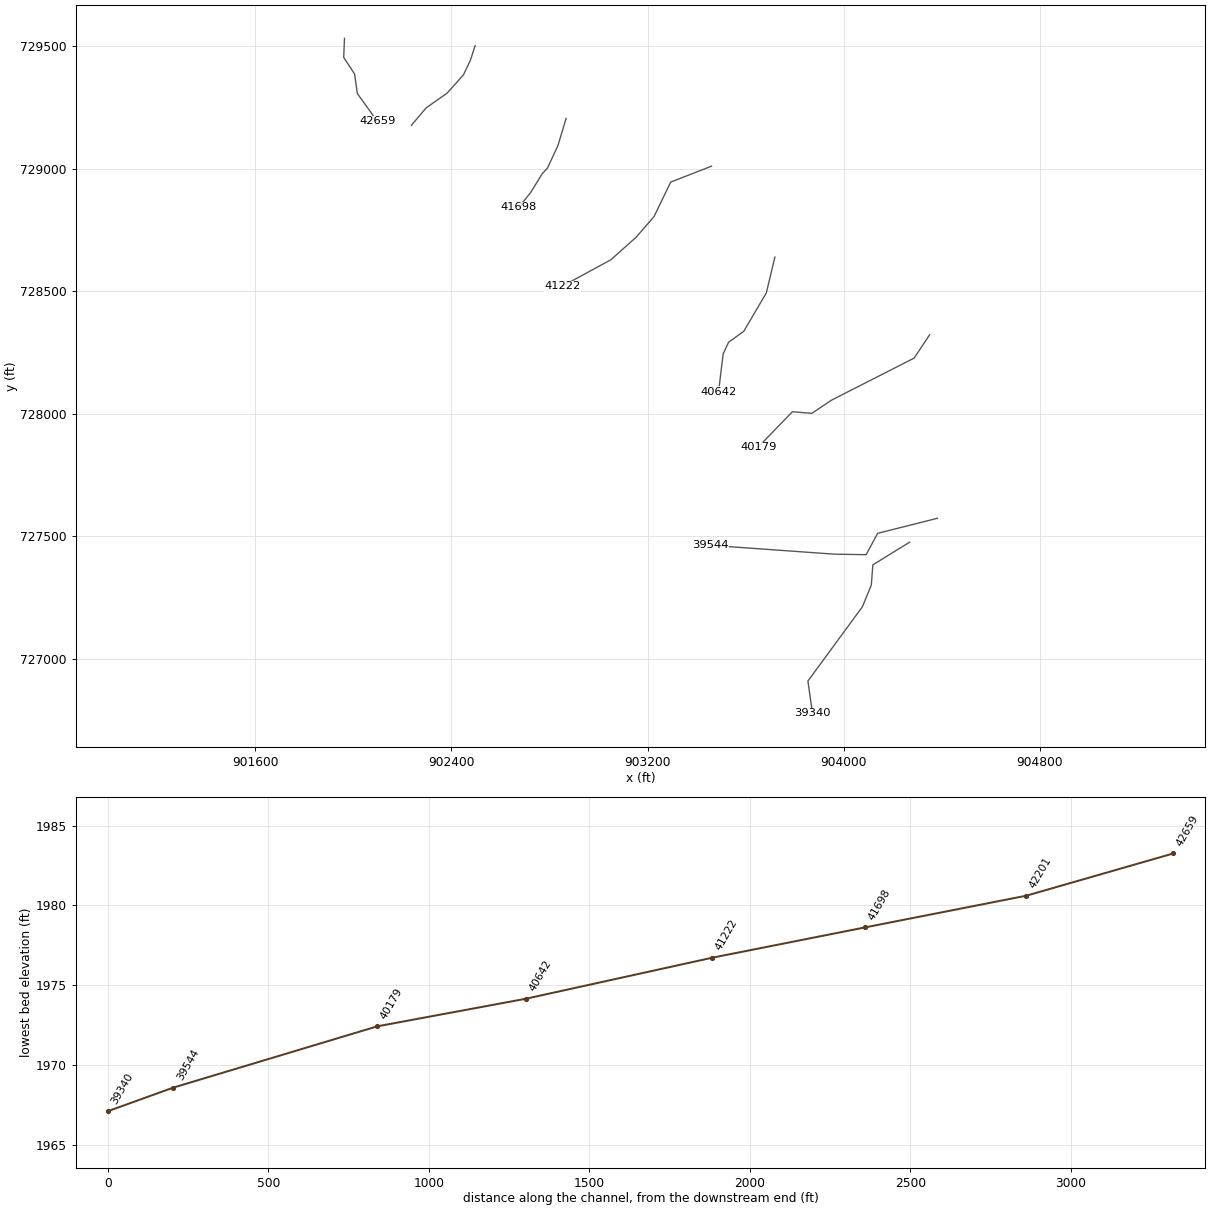
HEC-RAS study lds_turkey_crk.prj: Turkey Creek Limited Detail Study

--- lds_turkey_crk.g01 (geometry) --- (continued)

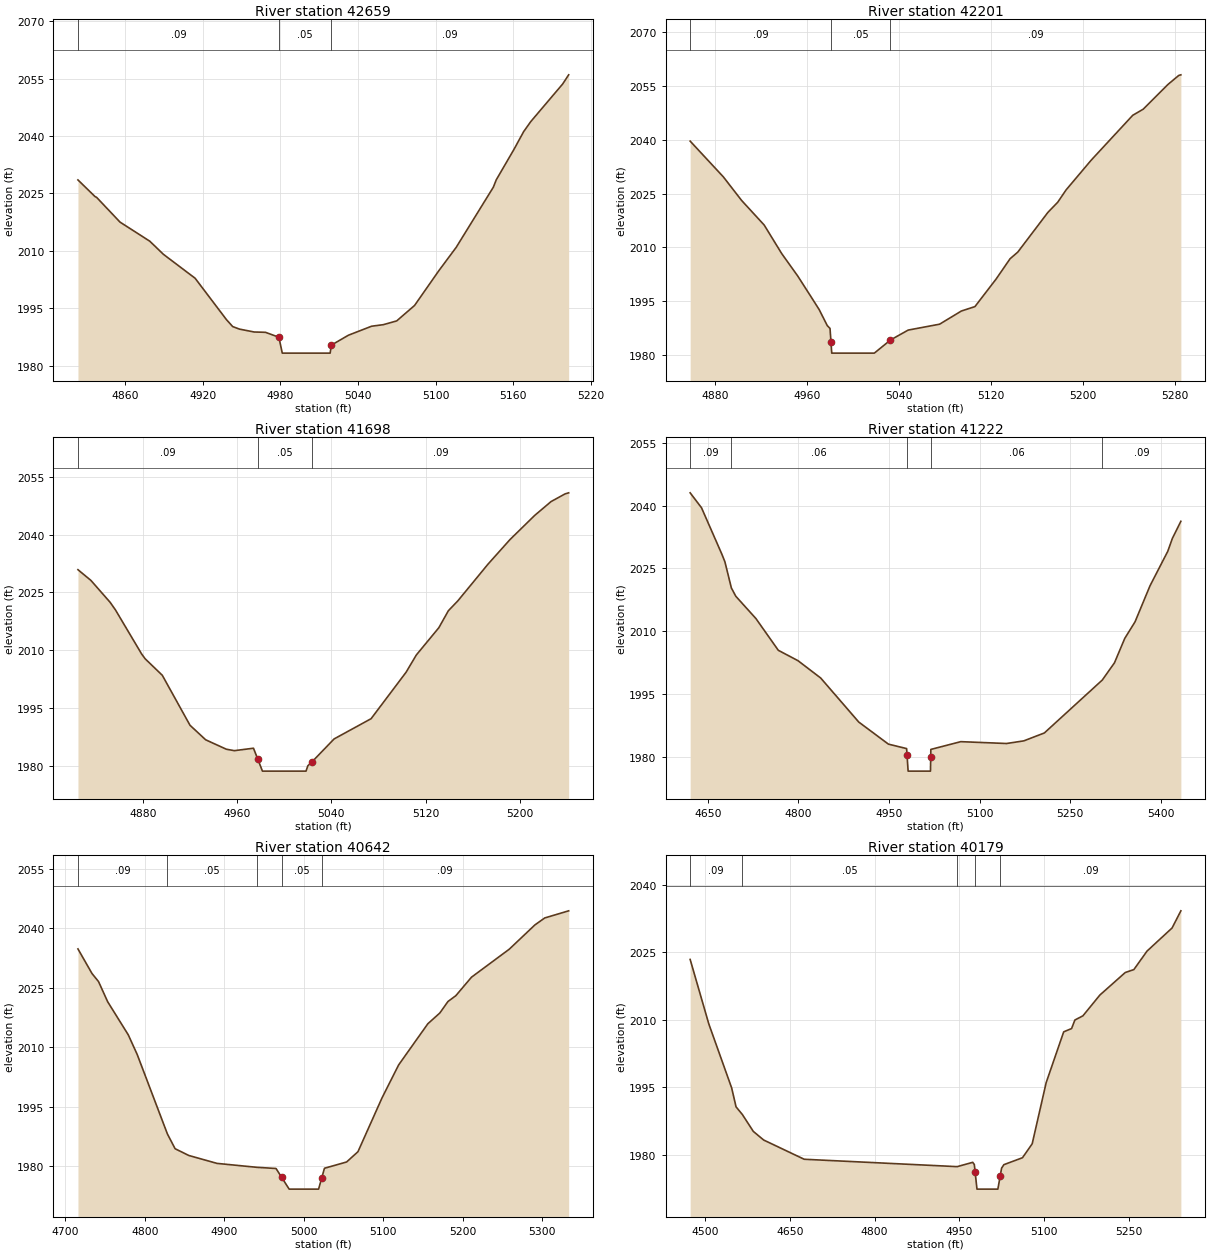
Type RM Length L Ch R = 1 ,42659   ,458,458,458
BEGIN DESCRIPTION:
Turkey_Crk_XS88
END DESCRIPTION:
XS GIS Cut Line= 6
       901964.33       729531.88       901961.16        729454.2
       902005.55       729386.03       902016.65       729306.76
       902065.79       729238.59        902097.5       729192.61
#Sta/Elev= 30
  4823.7 2028.51  4836.9 2024.16  4838.1 2023.96  4856.2 2017.49  4879.2  2012.5
  4889.7 2009.08  4914.2 2002.82  4938.4 1992.01  4943.2  1990.2  4948.5 1989.53
  4959.8 1988.78  4968.5  1988.7  4978.9 1987.41  4981.5 1983.26  5018.5 1983.26
  5019.4 1985.35  5032.6 1987.94  5050.5 1990.29  5059.5 1990.69  5069.9 1991.68
  5083.7 1995.72  5102.4 2004.78  5115.8 2010.88  5144.5  2026.6  5146.8 2028.55
  5160.4 2036.46  5167.9 2041.11  5173.4 2043.74  5198.1 2053.59  5202.7 2055.97
#Mann= 3 ,-1 , 0
  4823.7     .09       0  4978.9     .05       0  5019.4     .09       0
Bank Sta=4978.9,5019.4
Exp/Cntr=0.3,0.1

Type RM Length L Ch R = 1 ,42201   ,503,503,503
BEGIN DESCRIPTION:
Turkey_Crk_XS87
END DESCRIPTION:
XS GIS Cut Line= 6
       902497.01       729501.76       902477.99        729443.1
       902449.45       729382.86       902382.86       729308.35
       902297.25        729248.1       902237.01       729176.76
#Sta/Elev= 30
  4858.5 2039.57  4887.3 2029.64  4903.2 2023.07  4922.8 2016.24  4938.1 2008.26
  4951.9 2002.08  4963.9 1996.09  4970.6 1992.71  4977.6 1988.27    4980 1987.47
  4980.81983.812  4981.5 1980.61  5018.5 1980.61  5032.5 1984.26  5047.9 1987.02
  5075.2 1988.66  5094.1 1992.32  5105.9 1993.55  5124.3 2001.22  5136.4 2006.85
  5143.1  2008.7  5169.3 2019.76  5177.8 2022.57  5185.1 2026.01  5206.9 2034.28
    5243 2046.76    5252 2048.44  5273.6 2055.34    5283 2057.85  5284.8 2058.01
#Mann= 3 ,-1 , 0
  4858.5     .09       0  4980.8     .05       0  5032.5     .09       0
Bank Sta=4980.8,5032.5
Exp/Cntr=0.3,0.1

Type RM Length L Ch R = 1 ,41698   ,476,476,476
BEGIN DESCRIPTION:
Turkey_Crk_XS86
END DESCRIPTION:
XS GIS Cut Line= 6
       902867.99        729205.3       902834.69       729094.32
       902791.89       729002.37       902771.28       728980.18
       902722.13       728900.91       902674.57       728842.25
#Sta/Elev= 30
  4824.9 2030.88  4835.9  2028.1  4852.2 2022.42  4856.7 2020.46  4878.9 2009.04
  4881.9 2007.78  4896.5 2003.48    4920 1990.52  4933.3 1986.75  4950.8 1984.31
  4957.6 1983.93  4973.9 1984.56  4977.61981.668  4981.5 1978.62  5018.5 1978.62
    5020    1980  5023.7 1981.07  5042.3 1986.97  5073.7 1992.22  5103.4 2004.27
  5112.1 2008.75  5131.2 2015.82  5139.3 2020.23  5147.3 2022.78  5172.9  2032.3
  5191.5 2038.66  5212.5 2044.94  5226.5 2048.56  5238.4 2050.55  5241.4 2050.82
#Mann= 3 ,-1 , 0
  4824.9     .09       0  4977.6     .05       0  5023.7     .09       0
Bank Sta=4977.6,5023.7
Exp/Cntr=0.3,0.1

Type RM Length L Ch R = 1 ,41222   ,580,580,580
BEGIN DESCRIPTION:
Turkey_Crk_XS85
END DESCRIPTION:
XS GIS Cut Line= 6
       903460.91        729010.3       903294.45        728945.3
       903226.28        728804.2       903153.35       728720.18
        903050.3       728628.22       902852.13       728520.42
#Sta/Elev= 30
  4620.7 2043.02  4639.5 2039.46  4673.2  2028.4  4678.2  2026.6  4688.9 2020.37
  4696.2 2018.39  4729.6 2013.06  4766.6 2005.51  4799.2 2003.03  4836.8  1998.9
  4899.8 1988.41  4948.9 1983.15    4979 1982.09  4979.71980.586  4981.5 1976.72
  5018.5 1976.72  5018.91980.165  5019.1 1981.89  5068.7 1983.74  5144.5  1983.3
    5173 1983.93    5207 1985.81  5302.9 1998.42  5323.1 2002.53  5340.1 2008.34
  5357.1 2012.28  5381.9 2020.87  5411.3 2029.09  5418.9 2032.16    5433 2036.24
#Mann= 5 ,-1 , 0
  4620.7     .09       0  4688.9     .06       0  4979.7     .05       0
  5018.9     .06       0  5302.9     .09       0
Bank Sta=4979.7,5018.9
Exp/Cntr=0.3,0.1

Type RM Length L Ch R = 1 ,40642   ,463,463,463
BEGIN DESCRIPTION:
Turkey_Crk_XS84
END DESCRIPTION:
XS GIS Cut Line= 6
       903719.33       728639.32       903684.45       728493.47
        903592.5       728336.52       903530.67       728292.13
       903508.48       728244.57       903489.45        728089.2
#Sta/Elev= 30
  4715.9 2034.81  4733.6 2028.59  4741.8 2026.56  4753.3 2021.46  4779.2 2013.11
  4790.4 2008.16  4828.4 1988.08  4838.1 1984.35  4855.4 1982.64  4890.8 1980.65
  4941.3 1979.65    4965 1979.36  4971.91977.181  4981.5 1974.15  5018.5 1974.15
  5022.51976.999  5025.9 1979.42  5053.7    1981    5068 1983.59  5098.3  1997.2
  5119.2 2005.52  5155.9 2015.91    5171 2018.63  5181.2 2021.53  5191.1    2023
  5210.8 2027.67  5258.3 2034.74  5290.5 2040.86  5302.9 2042.63    5333 2044.43
#Mann= 5 ,-1 , 0
  4715.9     .09       0  4828.4     .05       0  4941.3     .09       0
  4971.9     .05       0  5022.5     .09       0
Bank Sta=4971.9,5022.5
Exp/Cntr=0.3,0.1

Type RM Length L Ch R = 1 ,40179   ,635,635,635
BEGIN DESCRIPTION:
Turkey_Crk_XS83
END DESCRIPTION:
XS GIS Cut Line= 6
        904350.3       728322.25       904286.89       728227.13
       903950.79       728055.91       903869.94         728002.
       903790.67       728008.35       903651.16       727864.08
#Sta/Elev= 30
  4473.4  2023.4  4506.4  2009.1  4546.9 1994.89  4554.7 1990.68    4566 1988.96
  4585.3 1985.23  4603.6 1983.32  4675.4 1979.05  4946.4 1977.41    4974 1978.37
  4976.8 1977.87  4978.21976.246  4981.5 1972.42  5018.5 1972.42  5022.51975.244
  5025.1 1977.08  5029.2 1977.85  5062.1 1979.39  5079.3 1982.48  5104.1 1996.07
  5135.1 2007.33  5149.1 2008.06  5154.9 2009.95  5169.2 2010.89  5199.3 2015.51
  5244.2  2020.5  5259.4 2021.15  5282.8 2025.26  5327.1 2030.38  5342.7 2034.19
#Mann= 5 ,-1 , 0
  4473.4     .09       0    4566     .05       0  4946.4     .09       0
  4978.2     .05       0  5022.5     .09       0
Bank Sta=4978.2,5022.5
Exp/Cntr=0.3,0.1

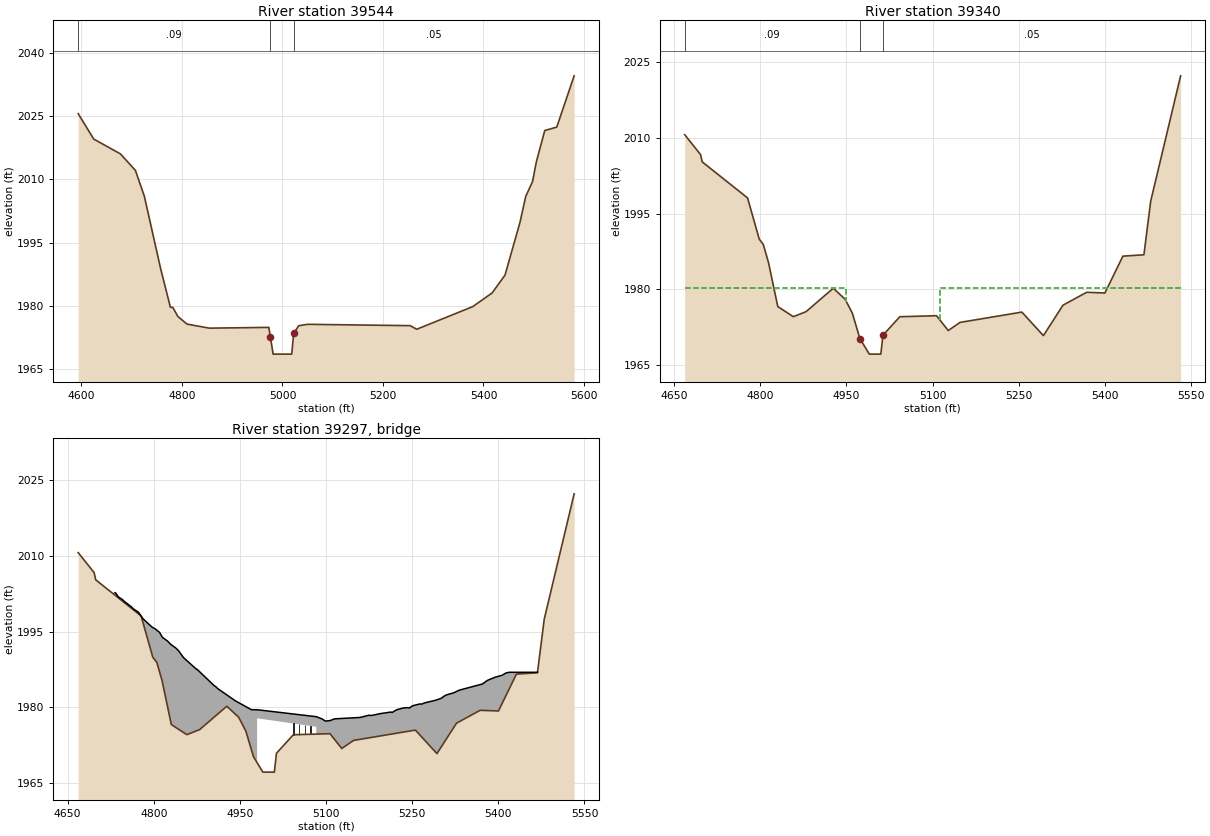
Type RM Length L Ch R = 1 ,39544   ,204,204,204
BEGIN DESCRIPTION:
Turkey_Crk_XS82
END DESCRIPTION:
XS GIS Cut Line= 5
       904382.36       727573.75       904138.17       727512.17
       904091.45        727425.1       903961.92       727427.23
       903456.54       727463.33
#Sta/Elev= 30
  4593.6 2025.59  4624.5 2019.57  4677.6 2016.06  4707.4 2012.15  4725.2 2006.03
  4757.4 1988.97    4777 1979.71  4781.8 1979.67  4791.9 1977.51  4810.1  1975.7
  4854.5 1974.74    4973 1974.92  4975.91972.757  4981.5 1968.58  5018.5 1968.58
  5022.4 1973.53  5032.5 1975.32  5050.1 1975.65  5254.3 1975.33  5267.1 1974.47
  5378.8 1979.85  5417.3 1983.09  5442.9 1987.31  5472.7 1999.81  5484.2    2006
  5497.7 2009.49  5505.1 2014.09    5522  2021.6  5545.9 2022.41  5580.5 2034.57
#Mann= 3 ,-1 , 0
  4593.6     .09       0  4975.9    .045       0  5022.4     .05       0
Bank Sta=4975.9,5022.4
Exp/Cntr=0.5,0.3

Type RM Length L Ch R = 1 ,39340   ,81,81,81
BEGIN DESCRIPTION:
Turkey_Crk_XS81
END DESCRIPTION:
XS GIS Cut Line= 6
        904268.6       727476.08       904118.84       727383.71
        904112.5       727301.27       904076.04       727212.49
       903854.02       726909.54       903872.59       726777.65
#Sta/Elev= 30
  4668.5 2010.65  4696.2 2006.69    4699 2005.25    4778 1998.09  4798.3 1989.92
  4805.4 1988.86  4814.6 1985.21  4830.6 1976.54  4857.7 1974.53  4879.9 1975.53
  4927.2 1980.17  4947.8    1978  4960.5 1975.21  4973.6 1970.18    4990  1967.1
    5010  1967.1  5013.7 1970.85  5043.1 1974.52    5107 1974.72  5127.4 1971.78
  5147.9 1973.39  5255.6 1975.44  5293.1 1970.77  5327.2 1976.81  5368.4 1979.37
  5400.2 1979.23  5431.5 1986.54  5468.1 1986.81  5479.9 1997.44    5532 2022.32
#Mann= 3 ,-1 , 0
  4668.5     .09       0  4973.6    .045       0  5013.7     .05       0
#XS Ineff= 2 , 0
       0    4950  1980.2    5113       0  1980.2
Permanent Ineff=
       F       F
Bank Sta=4973.6,5013.7
Exp/Cntr=0.5,0.3

Type RM Length L Ch R = 3 ,39297   ,,,
BEGIN DESCRIPTION:
Turkey_Crk_XS80
Structure ID: Bear Creek Rd SR 1607
Approximate Survey Structure
END DESCRIPTION:
Bridge Culvert--1,0,-1,-1, 0
Deck Dist Width WeirC Skew NumUp NumDn MinLoCord MaxHiCord MaxSubmerge Is_Ogee
31,24,3,0, 60, 60, , , , 0, 1,1,,
  4732.3  4734.1  4738.3  4745.2  4749.2  4760.1  4764.7  4773.5    4781  4797.1
  4802.7  4810.1  4815.1  4823.9  4829.3  4837.8  4842.8  4851.9  4874.5  4875.6
  4905.2  4908.2  4911.4  4942.1  4970.2    4980    4980    5083    5083  5093.1
  5098.7  5107.2  5114.8  5159.3  5174.3  5179.1  5194.5    5213  5215.3  5222.4
    5233  5240.2  5245.2  5250.5  5262.3  5267.9  5270.1  5290.3  5300.7  5304.8
    5310  5322.4  5331.8    5372  5381.1  5394.2  5406.3    5414  5419.3  5468.1
  2002.7 2002.59 2001.87 2001.36 2000.93 1999.99 1999.48 1998.81 1997.56 1995.87
 1995.51 1994.83 1993.85 1993.12 1992.48 1991.78 1991.25 1989.82  1987.5 1987.49
 1984.26 1984.04 1983.67 1981.25 1979.48 1979.48 1979.48  1978.1  1978.1 1977.66
 1977.23 1977.33 1977.67 1977.95 1978.38 1978.34 1978.71 1979.02 1978.95 1979.45
 1979.79  1979.9 1979.83 1980.26  1980.6 1980.63 1980.79 1981.35 1981.75 1982.12
 1982.44 1982.84 1983.36 1984.58 1985.31 1985.92 1986.31 1986.81 1986.91 1986.91
  1937.5  1937.5  1937.5  1937.5  1937.5  1937.5  1937.5  1937.5  1937.5  1937.5
  1937.5  1937.5  1937.5  1937.5  1937.5  1937.5  1937.5  1937.5  1937.5  1937.5
  1937.5  1937.5  1937.5  1937.5  1937.5  1937.5 1977.78  1976.1  1937.5  1937.5
  1937.5  1937.5  1937.5  1937.5  1937.5  1937.5  1937.5  1937.5  1937.5  1937.5
  1937.5  1937.5  1937.5  1937.5  1937.5  1937.5  1937.5  1937.5  1937.5  1937.5
  1937.5  1937.5  1937.5  1937.5  1937.5  1937.5  1937.5  1937.5  1937.5  1937.5
  4732.3  4734.1  4738.3  4745.2  4749.2  4760.1  4764.7  4773.5    4781  4797.1
  4802.7  4810.1  4815.1  4823.9  4829.3  4837.8  4842.8  4851.9  4874.5  4875.6
  4905.2  4908.2  4911.4  4942.1  4970.2    4980    4980    5083    5083  5093.1
  5098.7  5107.2  5114.8  5159.3  5174.3  5179.1  5194.5    5213  5215.3  5222.4
    5233  5240.2  5245.2  5250.5  5262.3  5267.9  5270.1  5290.3  5300.7  5304.8
    5310  5322.4  5331.8    5372  5381.1  5389.3  5394.2  5406.3    5414  5419.3
  2002.7 2002.59 2001.87 2001.36 2000.93 1999.99 1999.48 1998.81 1997.56 1995.87
 1995.51 1994.83 1993.85 1993.12 1992.48 1991.78 1991.25 1989.82  1987.5 1987.49
 1984.26 1984.04 1983.67 1981.25 1979.48 1979.48 1979.48  1978.1  1978.1 1977.66
 1977.23 1977.33 1977.67 1977.95 1978.38 1978.34 1978.71 1979.02 1978.95 1979.45
 1979.79  1979.9 1979.83 1980.26  1980.6 1980.63 1980.79 1981.35 1981.75 1982.12
 1982.44 1982.84 1983.36 1984.58 1985.31 1985.63 1985.92 1986.31 1986.81 1986.91
  1937.5  1937.5  1937.5  1937.5  1937.5  1937.5  1937.5  1937.5  1937.5  1937.5
  1937.5  1937.5  1937.5  1937.5  1937.5  1937.5  1937.5  1937.5  1937.5  1937.5
  1937.5  1937.5  1937.5  1937.5  1937.5  1937.5 1977.78  1976.1  1937.5  1937.5
  1937.5  1937.5  1937.5  1937.5  1937.5  1937.5  1937.5  1937.5  1937.5  1937.5
  1937.5  1937.5  1937.5  1937.5  1937.5  1937.5  1937.5  1937.5  1937.5  1937.5
  1937.5  1937.5  1937.5  1937.5  1937.5  1937.5  1937.5  1937.5  1937.5  1937.5
Pier Skew, UpSta & Num, DnSta & Num=  ,5043, 2 ,5043, 2 , 0 , 0 , 0 ,,
       1       1
    1974  1977.5
       1       1
    1974  1977.5
Pier Skew, UpSta & Num, DnSta & Num=  ,5053, 2 ,5053, 2 , 0 , 0 , 0 ,,
       1       1
    1974  1977.5
       1       1
    1974  1977.5
Pier Skew, UpSta & Num, DnSta & Num=  ,5063, 2 ,5063, 2 , 0 , 0 , 0 ,,
       1       1
    1974  1977.5
       1       1
    1974  1977.5
Pier Skew, UpSta & Num, DnSta & Num=  ,5073, 2 ,5073, 2 , 0 , 0 , 0 ,,
       1       1
    1974  1977.5
       1       1
    1974  1977.5
BR Coef= 1 , 1 , 0 ,1.25, 0 ,,,0.8,0,2,0,
WSPro=,,,, 1 ,,,, 0 ,,,, 0 ,,,,-1 ,-1 ,-1 , 0 , 0 , 0 , 0 , 0
BC Design=,, 0 ,, 0 ,,,,,,
BC HTab HWMax=1980.74