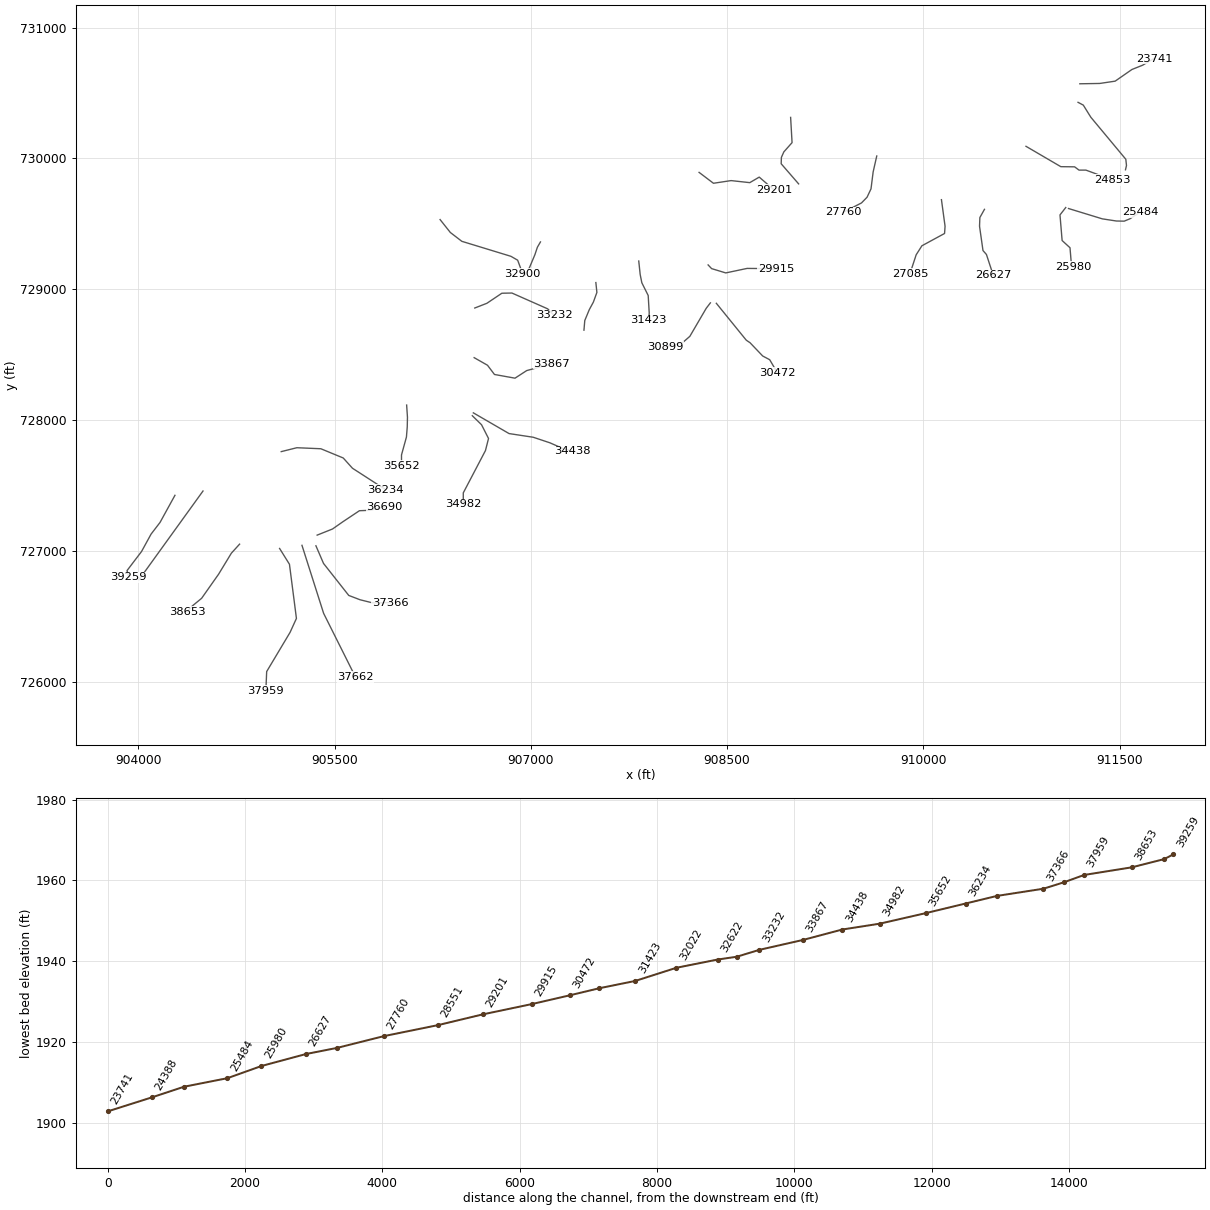
HEC-RAS study lds_turkey_crk.prj: Turkey Creek Limited Detail Study

--- lds_turkey_crk.g01 (geometry) --- (continued)

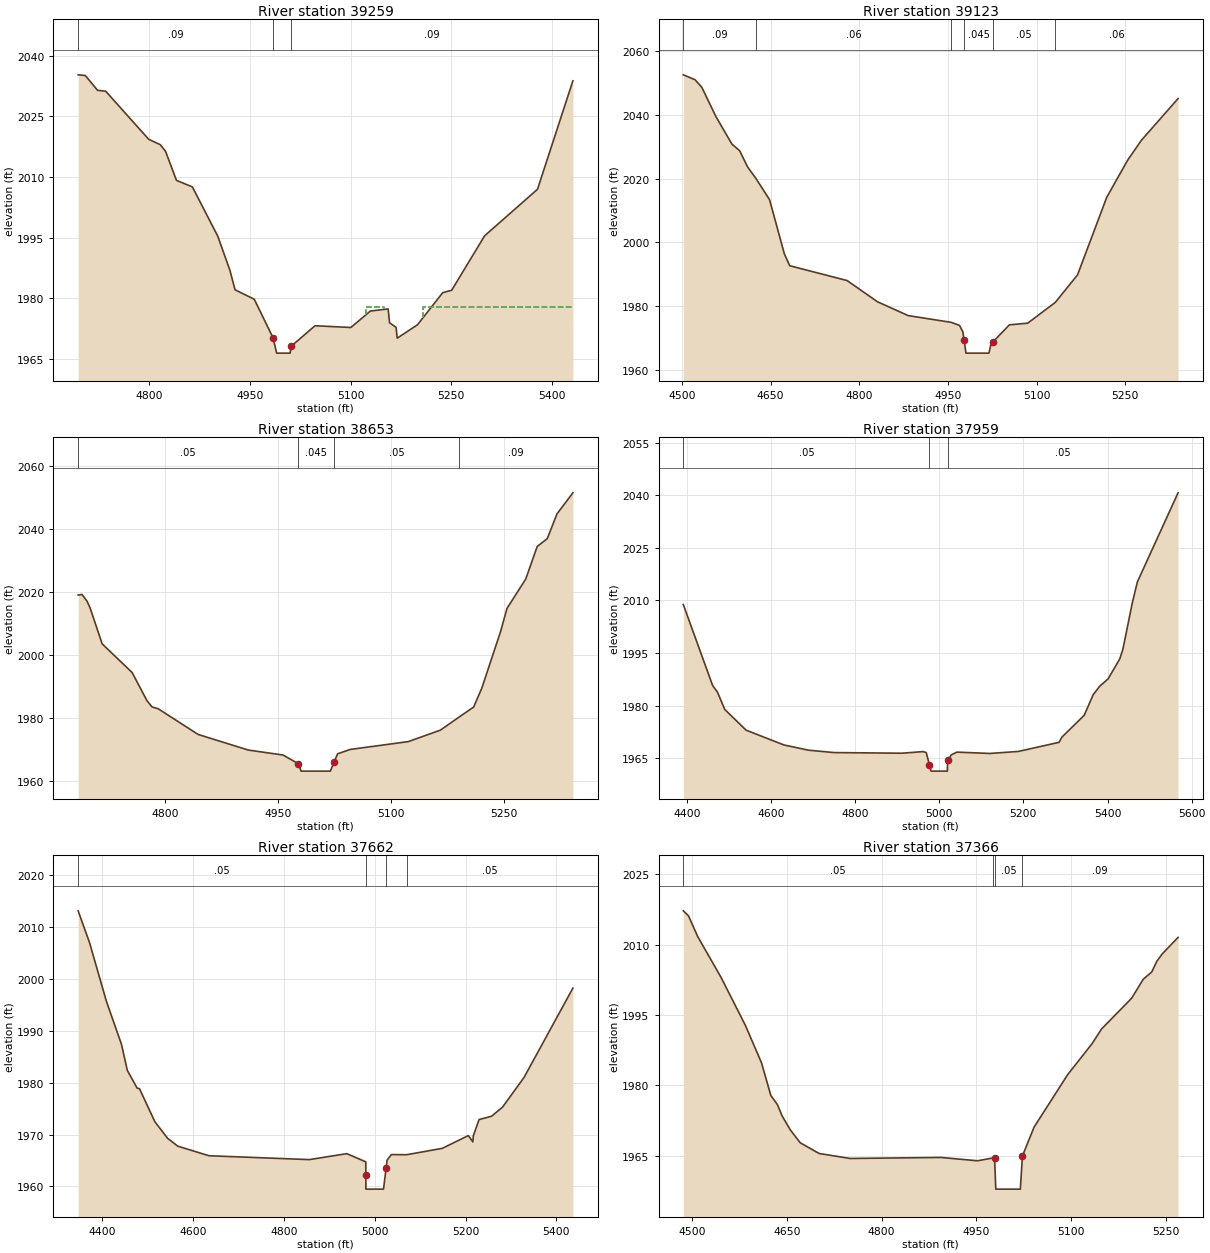
Type RM Length L Ch R = 1 ,39259   ,136,136,136
BEGIN DESCRIPTION:
Turkey_Crk_XS79
END DESCRIPTION:
XS GIS Cut Line= 6
       904280.55       727424.93        904166.4       727217.25
       904098.23       727128.47        904025.3        726995.3
       903914.33       726849.44       903927.95       726798.58
#Sta/Elev= 30
  4694.4 2035.25    4705 2035.09  4723.3 2031.42  4735.4  2031.2  4799.4 2019.32
  4816.7 2017.97  4824.5 2016.35  4840.8 2009.15  4864.5 2007.53  4902.3 1995.35
  4920.4  1986.9    4928  1982.1  4956.7 1979.75  4984.6 1970.21    4990 1966.43
    5010 1966.43  5011.7 1968.14  5047.1  1973.2  5100.5 1972.77  5129.6 1976.84
    5156 1977.36  5158.1 1973.95  5167.8  1972.8  5169.5 1970.13  5199.6 1973.43
  5237.3 1981.38  5250.6 1981.98  5299.7 1995.45  5378.4 2006.95  5431.1 2033.77
#Mann= 3 ,-1 , 0
  4694.4     .09       0  4984.6    .045       0  5011.7     .09       0
#XS Ineff= 3 ,-1
  4694.4    4940  1978.5    5123    5150  1977.8  5207.9  5431.1  1977.8
Permanent Ineff=
       F       T       T
Bank Sta=4984.6,5011.7
Exp/Cntr=0.5,0.3

Type RM Length L Ch R = 1 ,39123   ,470,470,470
BEGIN DESCRIPTION:
turkey crk z6
END DESCRIPTION:
XS GIS Cut Line= 2
       904495.07       727457.83       904005.54       726779.25
#Sta/Elev= 30
  4502.5 2052.62  4522.3 2051.09  4533.8  2048.7  4557.7 2039.51  4584.7 2030.87
  4597.8  2028.8  4611.4 2023.64    4625 2020.19  4648.4 2013.41  4673.5 1996.36
  4682.5 1992.68  4779.5 1988.03  4831.1 1981.35  4882.9 1977.02  4955.8  1974.9
  4969.7 1973.94  4975.4  1971.9  4977.5 1969.21  4980.6 1965.24  5019.4 1965.24
  5022.9 1968.04  5026.4  1968.8    5054 1974.12  5085.1 1974.65  5131.7 1981.17
  5169.3 1989.81  5218.7 2014.18    5254  2025.8  5277.1 2032.02  5339.3 2045.16
#Mann= 6 ,-1 , 0
  4502.5     .09       0    4625     .06       0  4955.8     .05       0
  4977.5    .045       0  5026.4     .05       0  5131.7     .06       0
Bank Sta=4977.5,5026.4
Exp/Cntr=0.3,0.1

Type RM Length L Ch R = 1 ,38653   ,694,694,694
BEGIN DESCRIPTION:
Turkey_Crk_XS77
END DESCRIPTION:
XS GIS Cut Line= 6
       904774.52       727051.58       904711.79       726982.57
       904614.55        726822.6       904484.38       726637.54
        904413.8       726579.51        904374.6        726535.6
#Sta/Elev= 30
  4684.5 2019.09  4689.6 2019.28  4696.3 2017.15  4700.3 2015.05  4716.4  2003.6
  4756.2  1994.5  4775.8 1985.59  4782.6  1983.6  4790.9 1982.99  4843.8 1974.85
  4910.4  1969.9  4956.7 1968.31  4976.8 1965.57  4980.6 1963.21  5019.4 1963.21
  5024.41966.164    5029 1968.71  5045.7 1970.09  5122.9 1972.58  5165.4 1976.21
  5190.3 1980.37  5209.6 1983.54  5220.6 1989.63  5245.5 2007.59  5253.9 2014.86
  5278.8 2024.17    5294  2034.5  5307.4 2037.01  5320.3 2044.87  5341.4 2051.54
#Mann= 4 ,-1 , 0
  4684.5     .05       0  4976.8    .045       0  5024.4     .05       0
  5190.3     .09       0
Bank Sta=4976.8,5024.4
Exp/Cntr=0.3,0.1

Type RM Length L Ch R = 1 ,37959   ,297,297,297
BEGIN DESCRIPTION:
Turkey_Crk_XS76
END DESCRIPTION:
XS GIS Cut Line= 6
       905080.34       727018.64       905155.62       726897.88
       905208.94       726483.85       905160.32        726377.2
       904981.54       726077.65       904975.26       725928.66
#Sta/Elev= 30
  4391.7 2008.83  4461.3 1985.77  4472.9 1983.85  4490.2 1978.92  4540.9 1973.01
  4630.7 1968.79  4689.3 1967.29  4750.2 1966.61    4911 1966.43  4962.2 1966.89
  4969.2  1966.6  4976.8 1963.08  4980.6 1961.32  5019.4 1961.32  5019.7 1964.36
  5029.1 1966.01  5042.3 1966.74  5120.7 1966.36  5188.4 1966.94  5284.8 1969.53
  5291.7 1971.02  5344.7 1977.26    5366 1983.11  5380.7 1985.42  5401.5 1987.65
    5429 1993.29  5436.4 1995.98  5459.2 2009.42  5471.1 2015.31  5567.7 2040.69
#Mann= 3 ,-1 , 0
  4391.7     .05       0  4976.8    .045       0  5019.7     .05       0
Bank Sta=4976.8,5019.7
Exp/Cntr=0.3,0.1

Type RM Length L Ch R = 1 ,37662   ,296,296,296
BEGIN DESCRIPTION:
turkey crk z7
END DESCRIPTION:
XS GIS Cut Line= 3
        905251.3       727042.58       905416.72       726522.67
        905659.8       726036.52
#Sta/Elev= 30
  4347.2 2013.14  4372.3    2007  4409.4  1995.7  4442.5 1987.43  4455.4 1982.39
  4477.1 1978.95  4482.2 1978.86  4516.1 1972.48  4544.4 1969.26  4566.6 1967.77
    4635 1965.93  4856.2 1965.18  4938.6 1966.33  4980.4 1964.75  4980.5 1962.12
  4980.6 1959.49  5019.4 1959.49  5025.11963.516  5027.3 1965.07  5036.7 1966.15
  5070.1 1966.12  5148.7 1967.35  5206.1 1969.81  5216.1 1968.59  5217.1 1969.77
  5229.7  1972.9  5257.2 1973.54  5281.3 1975.28  5328.8 1981.03  5436.3 1998.24
#Mann= 4 ,-1 , 0
  4347.2     .05       0  4980.5     .05       0  5025.1     .06       0
  5070.1     .05       0
Bank Sta=4980.5,5025.1
Exp/Cntr=0.3,0.1

Type RM Length L Ch R = 1 ,37366   ,676,676,676
BEGIN DESCRIPTION:
Turkey_Crk_XS75
END DESCRIPTION:
XS GIS Cut Line= 6
       905357.93       727039.03       905415.96       726904.16
       905608.86        726659.5       905695.12       726626.56
       905789.22       726603.04        905924.1       726604.61
#Sta/Elev= 30
  4486.2 2017.19  4494.4 2016.13  4508.8 2011.75  4545.7 2003.07  4584.4  1992.8
  4609.9 1984.82  4624.7 1977.86  4635.1 1975.92  4642.4 1973.55  4655.4 1970.55
  4671.2 1967.78  4701.2  1965.5  4750.3 1964.44  4893.9 1964.66  4951.5 1963.95
  4975.5 1964.53  4978.6 1964.46  4980.6 1957.91  5019.4 1957.91  5022.7 1964.96
  5041.1 1971.11  5094.4 1982.32  5132.7 1988.86  5147.9 1992.03  5195.4 1998.56
  5213.9 2002.63  5227.4 2004.18  5235.3 2006.44  5243.9 2008.01  5268.9 2011.53
#Mann= 4 ,-1 , 0
  4486.2     .05       0  4975.5     .09       0  4978.6     .05       0
  5022.7     .09       0
Bank Sta=4978.6,5022.7
Exp/Cntr=0.3,0.1

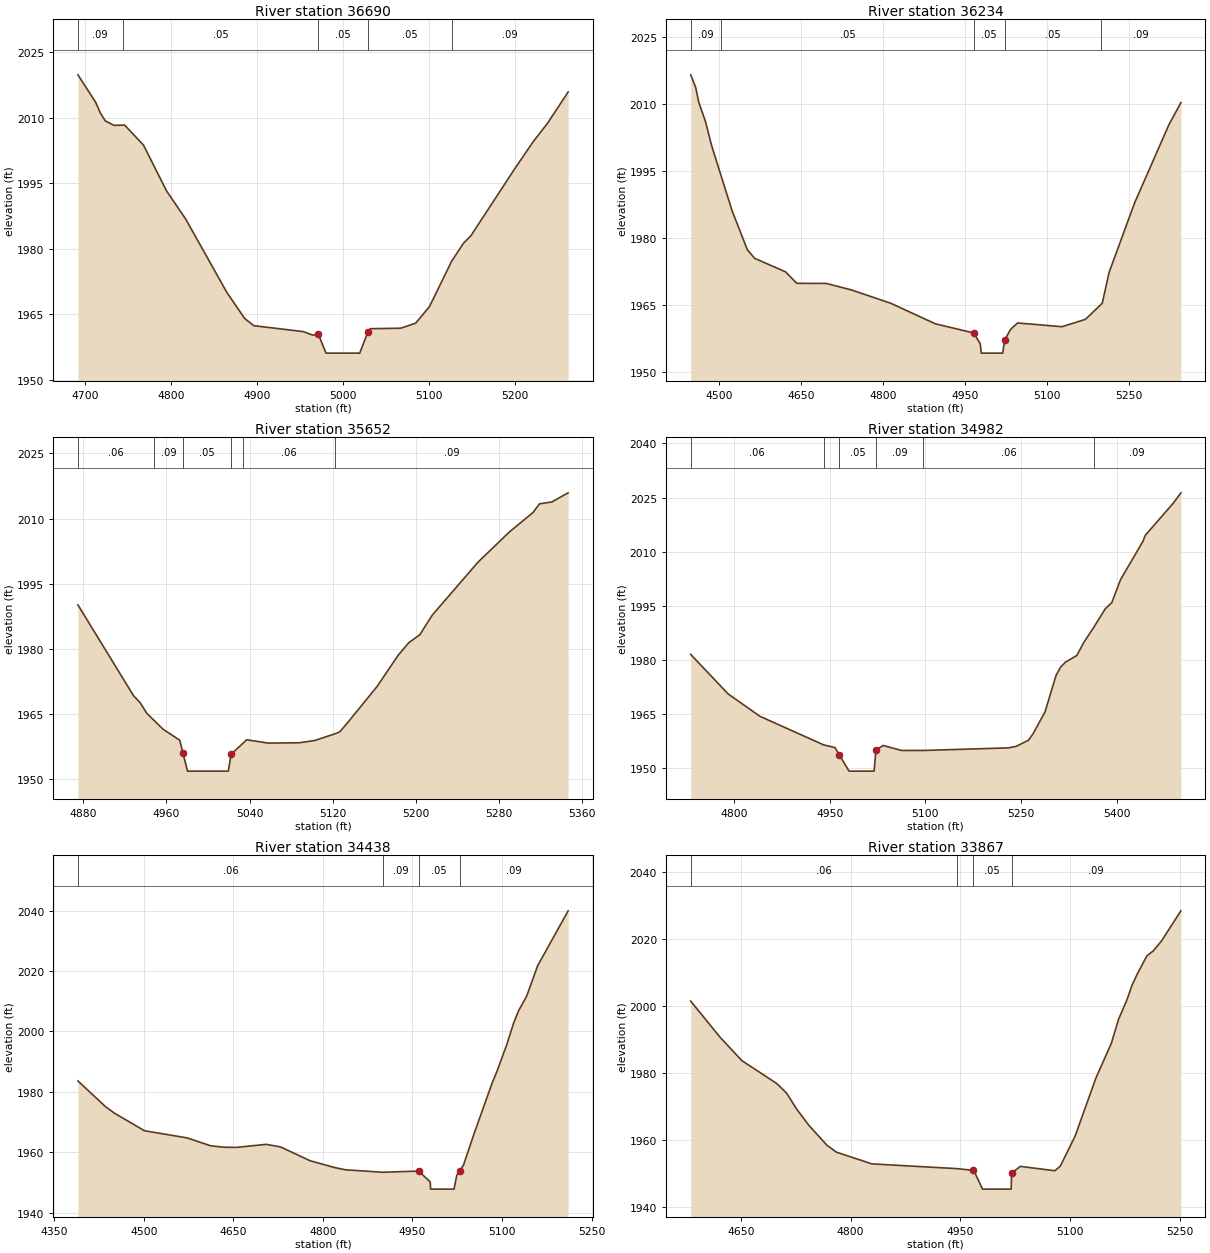
Type RM Length L Ch R = 1 ,36690   ,456,456,456
BEGIN DESCRIPTION:
Turkey_Crk_XS74
END DESCRIPTION:
XS GIS Cut Line= 6
       905367.34       727120.58       905484.97       727167.63
       905563.38       727222.52       905690.42       727307.21
       905771.97       727310.35       905881.75       727337.01
#Sta/Elev= 30
  4692.1  2019.8  4712.7 2013.53  4718.2 2011.06  4723.9 2009.27  4734.1 2008.24
    4744 2008.29  4746.4  2008.3  4768.3 2003.72  4795.1 1993.24  4817.2 1986.86
  4865.1 1970.04  4885.9 1964.05  4896.5 1962.41  4954.1 1961.05  4965.2 1960.23
  4971.3 1960.55  4980.4 1956.13  5019.6 1956.13    5029 1960.92    5032 1961.72
  5067.2 1961.83  5084.5 1962.97  5100.6 1966.76  5126.5  1977.2  5140.3  1981.3
  5148.7 1982.96  5199.5 1998.24  5220.8  2004.4  5237.9 2008.74  5261.8 2015.88
#Mann= 5 ,-1 , 0
  4692.1     .09       0    4744     .05       0  4971.3     .05       0
    5029     .05       0  5126.5     .09       0
Bank Sta=4971.3,5029
Exp/Cntr=0.3,0.1

Type RM Length L Ch R = 1 ,36234   ,582,582,582
BEGIN DESCRIPTION:
Turkey_Crk_XS73
END DESCRIPTION:
XS GIS Cut Line= 6
       905092.89       727758.89       905212.08       727788.69
       905395.57       727780.85       905566.52       727710.27
       905637.09       727631.86       905889.59       727468.75
#Sta/Elev= 30
  4448.2 2016.54  4457.3 2013.76    4463  2010.4    4475  2006.2  4486.5 2000.73
  4504.1 1993.87  4524.1 1986.09  4551.9 1977.41  4565.4 1975.46  4621.9 1972.45
  4642.5 1969.87  4696.6 1969.85  4742.4  1968.4  4814.4 1965.42  4896.3 1960.81
  4966.5 1958.76  4978.2 1956.41  4980.4 1954.25  5019.6 1954.25  5022.9 1957.12
  5033.8 1959.54  5046.8    1961  5128.2 1960.16  5171.1 1961.82  5198.9 1965.07
  5201.9 1965.47  5214.4 1972.35  5261.5 1988.02  5324.2 2005.46  5345.8 2010.32
#Mann= 5 ,-1 , 0
  4448.2     .09       0  4504.1     .05       0  4966.5     .05       0
  5022.9     .05       0  5198.9     .09       0
Bank Sta=4966.5,5022.9
Exp/Cntr=0.3,0.1

Type RM Length L Ch R = 1 ,35652   ,670,670,670
BEGIN DESCRIPTION:
Turkey_Crk_XS72
END DESCRIPTION:
XS GIS Cut Line= 6
       906051.13        728114.9        906057.4       728022.37
       906055.84       727948.66       906049.56       727870.24
       906011.92        727733.8       906011.92       727649.11
#Sta/Elev= 30
    4875 1990.12  4928.6 1969.17  4934.8 1967.64    4941 1965.24  4948.2 1963.54
  4956.7 1961.54  4972.9 1958.97    49761956.031  4980.4 1951.86  5019.6 1951.86
  5022.3 1955.73  5033.7 1958.28  5037.3 1959.08  5057.9 1958.31  5087.9 1958.39
  5102.8 1958.91  5122.3 1960.46  5126.8 1960.91  5133.7 1962.83  5162.6 1971.32
    5183 1978.54  5193.2 1981.43  5203.8 1983.26  5215.7 1987.76  5259.9    2000
  5289.6 2006.84  5312.6 2011.37  5318.8 2013.37  5330.8 2013.82  5346.4 2015.91
#Mann= 6 ,-1 , 0
    4875     .06       0  4948.2     .09       0    4976     .05       0
  5022.3     .09       0  5033.7     .06       0  5122.3     .09       0
Bank Sta=4976,5022.3
Exp/Cntr=0.3,0.1

Type RM Length L Ch R = 1 ,34982   ,544,544,544
BEGIN DESCRIPTION:
Turkey_Crk_XS71
END DESCRIPTION:
XS GIS Cut Line= 6
       906552.99       728033.35       906623.57       727964.34
       906676.89       727859.26       906653.37       727766.73
       906483.99       727443.66       906483.99        727357.4
#Sta/Elev= 30
  4732.4 1981.58  4790.9 1970.66  4840.9 1964.43  4940.9  1956.5  4958.3 1955.78
  4965.21953.741  4980.4 1949.25  5019.6 1949.25  5022.5 1955.01  5033.6 1956.36
  5062.6 1954.98  5096.4 1954.97  5229.9 1955.69  5242.3 1956.12  5261.4 1957.81
  5268.5 1959.57  5287.3 1965.66  5304.7 1975.81  5311.6 1978.02  5319.1  1979.4
  5337.1 1981.28  5348.1 1984.92  5363.5 1989.03  5381.7 1994.23  5391.9 1995.92
  5405.6  2002.3  5440.7 2012.91  5444.1 2014.51  5488.4 2023.52  5500.1 2026.33
#Mann= 6 ,-1 , 0
  4732.4     .06       0  4940.9     .09       0  4965.2     .05       0
  5022.5     .09       0  5096.4     .06       0  5363.5     .09       0
Bank Sta=4965.2,5022.5
Exp/Cntr=0.3,0.1

Type RM Length L Ch R = 1 ,34438   ,571,571,571
BEGIN DESCRIPTION:
Turkey_Crk_XS70
END DESCRIPTION:
XS GIS Cut Line= 6
       906560.83        728055.3       906833.72        727896.9
       907018.78       727868.67       907145.82       727826.33
       907249.33       727780.85       907318.33       727762.03
#Sta/Elev= 30
  4389.5 1983.62  4435.6 1975.12  4450.5 1972.96  4501.1 1967.13  4572.7 1964.75
  4611.7 1962.16    4633 1961.69  4654.7 1961.62  4705.1 1962.63    4729 1961.77
  4778.5  1957.2  4820.2 1954.92  4837.7 1954.21  4900.2 1953.39  4960.2 1953.78
  4979.7 1950.21  4980.4 1947.81  5019.6 1947.81  5024.1 1952.34  5028.8  1953.7
  5035.6 1955.84  5053.8 1966.49  5083.6 1982.99  5091.9 1986.97  5107.8 1995.56
  5119.4 2002.72  5127.7 2006.81  5141.3 2011.68  5159.7 2021.73  5210.8  2039.9
#Mann= 4 ,-1 , 0
  4389.5     .06       0  4900.2     .09       0  4960.2     .05       0
  5028.8     .09       0
Bank Sta=4960.2,5028.8
Exp/Cntr=0.3,0.1

Type RM Length L Ch R = 1 ,33867   ,635,635,635
BEGIN DESCRIPTION:
Turkey_Crk_XS69
END DESCRIPTION:
XS GIS Cut Line= 6
       906567.11       728477.18       906669.05       728419.15
       906722.37       728348.58        906879.2       728320.35
        906968.6       728378.38       907158.36       728430.13
#Sta/Elev= 30
  4581.1 2001.47  4621.4 1990.64  4651.2 1983.66  4698.6 1976.86  4712.3 1973.96
  4726.5 1969.05    4743 1964.27  4767.2 1958.44  4780.4  1956.3  4829.1 1952.78
  4945.6 1951.36  4966.9 1950.86  4969.8 1950.22  4980.4 1945.23  5019.6 1945.23
  5020.3 1950.01  5032.1 1952.04  5079.4 1950.73    5087 1952.14  5107.3 1961.19
  5135.6 1978.46  5156.7 1988.84  5166.5 1995.96  5178.2 2001.91  5184.8  2006.1
  5192.2 2009.57  5205.3 2014.99  5213.9 2016.45  5225.1 2019.37  5251.9 2028.47
#Mann= 4 ,-1 , 0
  4581.1     .06       0  4945.6     .09       0  4966.9     .05       0
  5020.3     .09       0
Bank Sta=4966.9,5020.3
Exp/Cntr=0.3,0.1

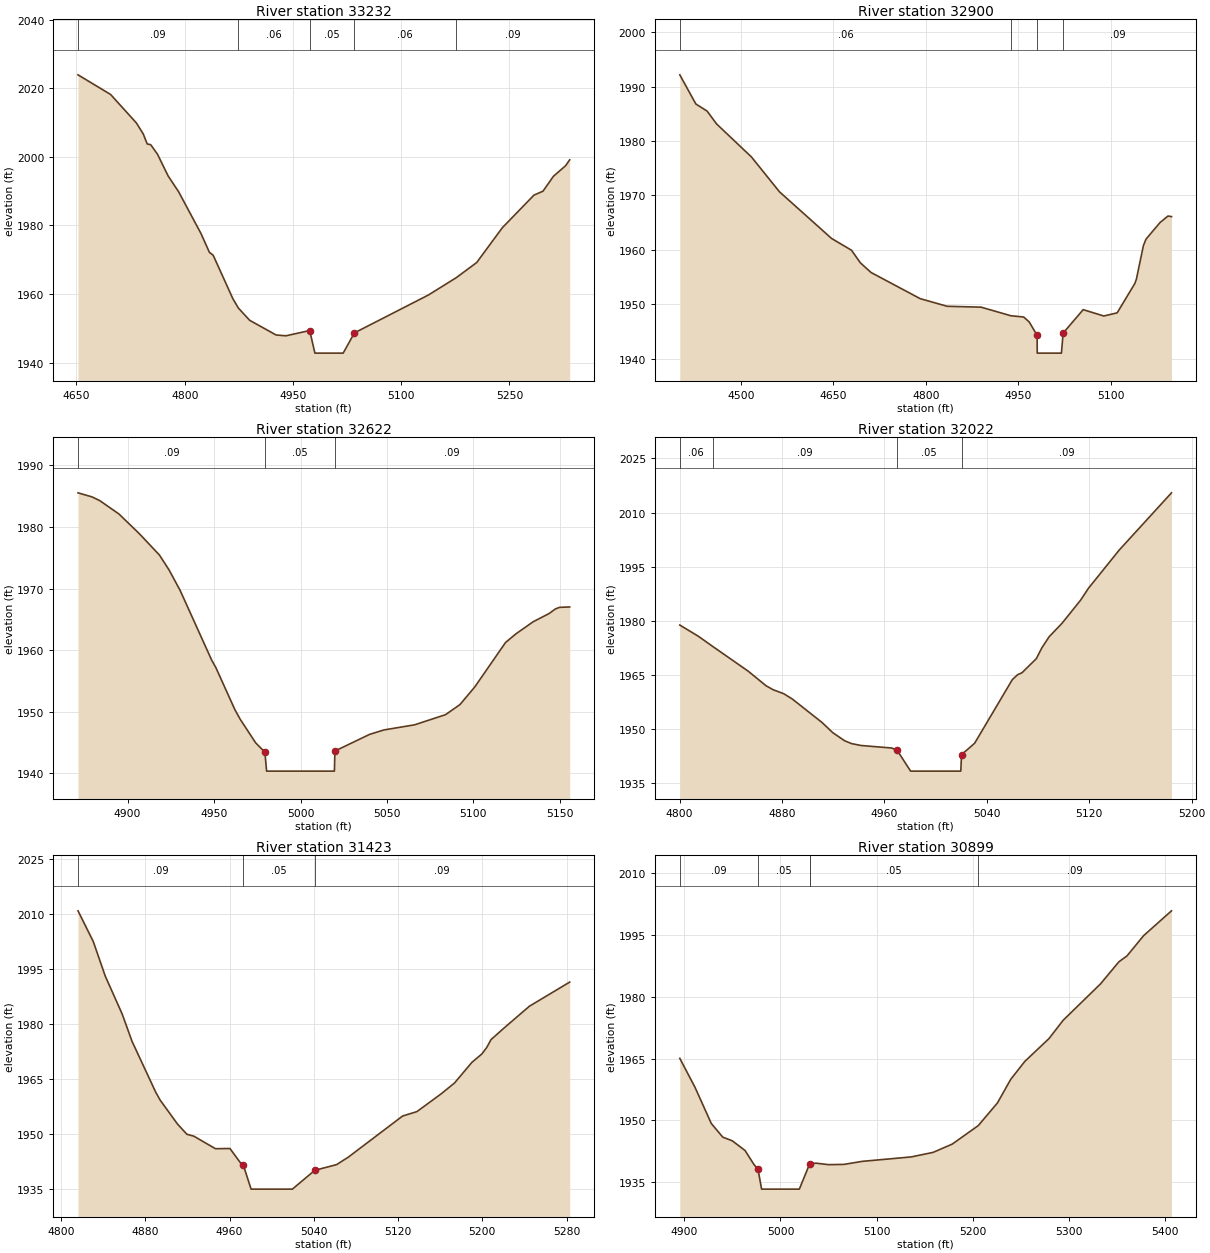
Type RM Length L Ch R = 1 ,33232   ,332,332,332
BEGIN DESCRIPTION:
Turkey_Crk_XS68
END DESCRIPTION:
XS GIS Cut Line= 6
       906571.81       728856.71       906664.34       728892.78
       906778.83       728969.63       906855.68        728971.2
       907128.57       728850.44       907177.18       728801.82
#Sta/Elev= 30
  4652.1  2023.9  4697.3 2018.17  4733.1 2009.85  4742.5 2006.68    4748 2003.76
  4752.9 2003.52  4762.3 2000.75    4777 1994.43  4791.6  1989.8  4822.6 1977.62
  4834.2 1972.16  4839.4 1971.33  4866.7 1958.65  4874.3 1955.94  4889.9 1952.36
  4926.6 1948.07  4940.3 1947.83  4973.2 1949.37  4980.4 1942.78  5019.6 1942.78
  5035.1 1948.67  5137.7 1959.72  5176.2 1964.76  5204.6 1969.18  5240.1 1979.32
    5284 1988.84  5296.5 1989.99    5311 1994.34  5327.8  1997.4  5333.5 1999.12
#Mann= 5 ,-1 , 0
  4652.1     .09       0  4874.3     .06       0  4973.2     .05       0
  5035.1     .06       0  5176.2     .09       0
Bank Sta=4973.2,5035.1
Exp/Cntr=0.3,0.1

Type RM Length L Ch R = 1 ,32900   ,278,278,278
BEGIN DESCRIPTION:
Turkey_Crk_XS67
END DESCRIPTION:
XS GIS Cut Line= 6
       906306.77       729532.66       906385.18       729433.85
       906473.01       729366.42       906847.84       729251.93
       906899.59       729222.13       906937.23       729120.19
#Sta/Elev= 30
  4400.8 1992.15  4426.8  1986.8  4445.2 1985.48  4460.4 1983.14    4517 1977.07
  4562.4 1970.68  4646.9 1962.11  4679.2 1959.95  4693.6 1957.64  4710.8 1955.87
  4790.6 1951.06  4834.3 1949.66  4889.2  1949.5  4937.7 1947.92  4958.4 1947.69
  4967.4 1946.78  4980.2 1944.33  4980.4 1941.06  5019.6 1941.06  5022.4 1944.74
  5054.9 1949.04  5088.3 1947.88    5110 1948.45  5138.8 1953.87  5141.2 1954.65
  5152.5 1960.78  5156.8 1961.99  5179.5 1965.03  5192.4 1966.23  5198.1 1966.12
#Mann= 4 ,-1 , 0
  4400.8     .06       0  4937.7     .09       0  4980.2     .05       0
  5022.4     .09       0
Bank Sta=4980.2,5022.4
Exp/Cntr=0.3,0.1

Type RM Length L Ch R = 1 ,32622   ,600,600,600
BEGIN DESCRIPTION:
Turkey_Crk_XS66
END DESCRIPTION:
XS GIS Cut Line= 5
       907073.67       729361.71       907050.15       729320.94
       907031.33       729264.48       906990.55       729167.24
       906954.48       729104.51
#Sta/Elev= 30
  4871.3 1985.56  4879.4  1984.9  4883.9 1984.29    4895 1982.12  4906.8 1978.92
  4918.4 1975.46    4924 1973.03  4930.4  1969.7  4948.6 1958.41  4951.1 1957.15
    4962 1950.38  4965.1  1948.8  4974.1 1944.95  4979.4 1943.45  4980.4 1940.37
  5019.6 1940.37  5019.9 1943.63  5039.9 1946.33  5048.3 1947.06    5066 1947.89
  5083.9 1949.54  5092.2 1951.17  5100.8 1954.04  5118.6 1961.26  5124.6 1962.66
  5134.6 1964.63  5143.8 1965.96  5147.4  1966.7  5149.8 1966.96  5155.7 1967.03
#Mann= 3 ,-1 , 0
  4871.3     .09       0  4979.4     .05       0  5019.9     .09       0
Bank Sta=4979.4,5019.9
Exp/Cntr=0.3,0.1

Type RM Length L Ch R = 1 ,32022   ,599,599,599
BEGIN DESCRIPTION:
Turkey_Crk_XS65
END DESCRIPTION:
XS GIS Cut Line= 6
       907497.12       729051.18       907504.96       728975.91
        907478.3       728902.19       907446.93       728844.17
       907412.43       728761.05       907406.16       728687.33
#Sta/Elev= 30
  4800.1 1978.83  4814.5 1975.74  4825.8  1972.9  4853.5 1966.05  4867.4 1962.02
  4872.9 1960.91  4881.3 1959.79  4888.1 1958.29  4911.2 1951.82  4919.6 1948.99
    4929 1946.72  4934.3 1945.96  4941.6 1945.44  4965.5 1944.74  4969.7 1944.21
  4980.4 1938.33  5019.6 1938.33  5020.2  1942.9  5030.4 1946.05  5059.9 1963.72
  5064.1 1965.09  5067.4  1965.6  5078.6 1969.51    5083 1972.55  5088.6 1975.58
  5098.7 1979.32  5113.2 1985.73  5119.3 1989.01  5143.4 1999.63  5184.2 2015.48
#Mann= 4 ,-1 , 0
  4800.1     .06       0  4825.8     .09       0  4969.7     .05       0
  5020.2     .09       0
Bank Sta=4969.7,5020.2
Exp/Cntr=0.3,0.1

Type RM Length L Ch R = 1 ,31423   ,524,524,524
BEGIN DESCRIPTION:
Turkey_Crk_XS64
END DESCRIPTION:
XS GIS Cut Line= 6
        907824.9       729215.86       907835.88       729112.35
       907848.42       729049.62       907897.04       728952.38
       907904.88       728819.07       907901.75       728762.61
#Sta/Elev= 30
    4816 2010.82  4830.4 2002.54  4841.9 1993.05    4858 1982.71  4867.3 1975.31
  4889.9 1961.41  4894.1 1959.27  4910.5 1952.79  4919.4 1950.01  4926.1 1949.47
  4946.6 1946.07  4960.3 1946.13  4970.4 1942.19  4973.1 1941.54  4980.4 1935.07
  5019.6 1935.07  5040.9 1940.19  5061.6 1941.74  5072.8 1943.79  5124.3 1954.97
  5137.9 1956.17    5161 1961.02  5173.6 1963.96  5190.1 1969.57  5199.6 1971.87
  5204.2 1973.62  5208.3 1975.78  5220.6 1978.91  5244.7 1984.85    5283 1991.42
#Mann= 3 ,-1 , 0
    4816     .09       0  4973.1     .05       0  5040.9     .09       0
Bank Sta=4973.1,5040.9
Exp/Cntr=0.3,0.1

Type RM Length L Ch R = 1 ,30899   ,427,427,427
BEGIN DESCRIPTION:
Turkey_Crk_XS63
END DESCRIPTION:
XS GIS Cut Line= 6
       908372.24       728895.92       908340.88       728855.14
       908215.41       728640.28       908152.68       728585.39
       908086.81       728577.55       908028.78       728558.73
#Sta/Elev= 30
  4895.4 1965.06  4911.2 1958.02  4928.1 1949.23    4940 1945.91    4950    1945
  4963.2 1942.65  4972.3  1939.3  4976.7 1938.05  4980.4 1933.26  5019.6 1933.26
  5030.2 1939.31  5030.4 1939.34  5036.8 1939.58  5049.8 1939.21  5065.8 1939.27
  5084.9 1940.01  5135.9 1941.09  5158.7  1942.2  5178.5 1944.21  5205.5  1948.7
  5225.5 1954.23  5239.3 1959.97  5253.9 1964.31    5279 1969.86  5293.8 1974.33
  5332.5 1983.15  5351.7 1988.54  5360.1 1989.97  5377.4  1994.9  5406.3 2000.92
#Mann= 5 ,-1 , 0
  4895.4     .09       0  4976.7     .05       0  5030.2     .09       0
  5030.4     .05       0  5205.5     .09       0
Bank Sta=4976.7,5030.2
Exp/Cntr=0.3,0.1

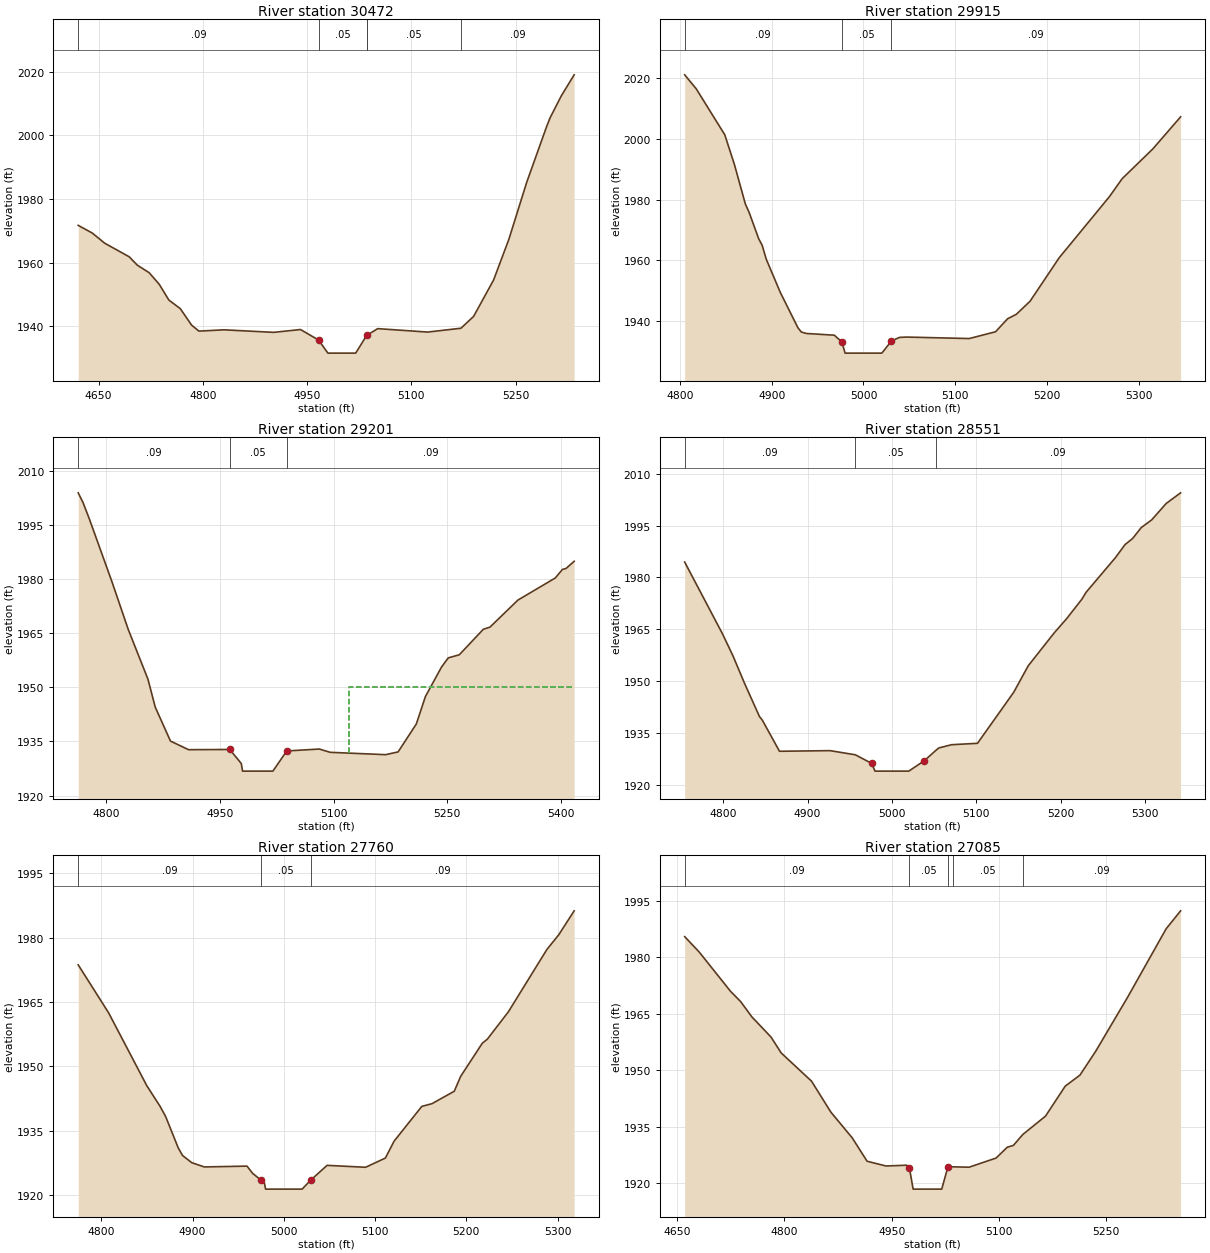
Type RM Length L Ch R = 1 ,30472   ,557,557,557
BEGIN DESCRIPTION:
Turkey_Crk_XS62
END DESCRIPTION:
XS GIS Cut Line= 6
       908417.72       728892.78        908646.7       728610.49
       908674.93       728591.67       908772.17       728489.73
       908825.49        728461.5       908883.52       728362.69
#Sta/Elev= 30
  4620.7  1971.7  4641.3 1969.23  4658.7  1966.1  4694.2  1961.8  4705.7 1959.19
  4722.8 1956.81  4737.4 1953.14  4751.1 1948.22  4767.6 1945.51  4783.9 1940.32
  4794.4 1938.44  4830.5 1938.85  4902.1 1938.05  4940.6 1938.94  4966.7 1935.63
    4980 1931.52    5020 1931.52  5035.9  1937.1  5036.6 1937.19  5051.7 1939.22
  5123.5 1938.14  5171.4 1939.34  5189.7 1943.06  5218.5 1954.53  5240.4 1967.28
  5266.2 1985.28    5295 2002.89  5299.8 2005.53  5315.9 2012.41  5334.4 2019.03
#Mann= 5 ,-1 , 0
  4620.7     .09       0  4966.7     .05       0  5035.9     .09       0
  5036.6     .05       0  5171.4     .09       0
Bank Sta=4966.7,5035.9
Exp/Cntr=0.3,0.1

Type RM Length L Ch R = 1 ,29915   ,714,714,714
BEGIN DESCRIPTION:
Turkey_Crk_XS61
END DESCRIPTION:
XS GIS Cut Line= 6
       908354.99       729186.06       908381.65       729157.83
       908489.87        729124.9       908652.97        729159.4
       908823.92       729157.83       908874.11       729151.56
#Sta/Elev= 30
  4805.2 2021.15  4817.7 2016.58  4848.9 2001.37  4859.3 1991.66  4871.3 1978.55
  4875.6 1975.62  4885.8 1967.09  4889.6 1964.92  4894.1  1960.3  4909.4 1949.35
  4928.6 1937.69  4932.3 1936.29  4937.9 1935.81  4968.2 1935.25  4976.4 1933.03
    4980 1929.33    5020 1929.33  5030.4  1933.3  5039.1 1934.52  5046.9 1934.63
  5115.2 1934.14  5143.9 1936.38    5157 1940.66  5166.6 1942.16  5181.5 1946.46
  5213.2 1960.79  5267.9 1980.94  5281.8 1986.88  5315.2  1996.7  5345.5 2007.29
#Mann= 3 ,-1 , 0
  4805.2     .09       0  4976.4     .05       0  5030.4     .09       0
Bank Sta=4976.4,5030.4
Exp/Cntr=0.3,0.1

Type RM Length L Ch R = 1 ,29201   ,650,650,650
BEGIN DESCRIPTION:
Turkey_Crk_XS60
END DESCRIPTION:
XS GIS Cut Line= 6
       908285.99       729893.37       908395.77       729810.25
       908530.64       729830.64       908673.36       729814.96
        908745.5        729857.3       908859.99        729758.5
#Sta/Elev= 30
  4763.2  2003.9  4769.5 2001.23  4777.8 1996.72  4807.9 1979.15  4829.1  1966.1
  4855.2 1952.26  4864.8 1944.53  4884.9 1935.11  4908.8 1932.72  4963.1 1932.78
  4978.3  1928.9    4980 1926.78    5020 1926.78  5038.3 1932.37  5081.3  1932.9
  5095.6 1931.99  5168.8 1931.34  5185.2 1932.11  5209.2 1939.84  5221.2 1947.45
  5242.4  1955.6  5251.3 1958.16  5265.9 1959.02  5297.6 1966.09  5306.3 1966.68
  5343.3 1974.19  5392.5  1980.3    5402 1982.68  5406.6 1982.92  5417.4 1984.93
#Mann= 3 ,-1 , 0
  4763.2     .09       0  4963.1     .05       0  5038.3     .09       0
#XS Ineff= 2 , 0
       0                    5120       0    1950
Permanent Ineff=
       F       F
Bank Sta=4963.1,5038.3
Exp/Cntr=0.3,0.1

Type RM Length L Ch R = 1 ,28551   ,791,791,791
BEGIN DESCRIPTION:
Turkey_Crk_XS59
END DESCRIPTION:
XS GIS Cut Line= 6
       908985.46       730313.68       908996.43       730120.78
        908933.7        730050.2       908914.88       730007.86
       908913.31       729959.24       909046.62       729805.55
#Sta/Elev= 30
  4754.3 1984.46  4799.2 1963.71  4811.8 1957.26  4825.2 1949.51    4843 1939.87
  4846.4 1938.83  4866.7 1929.86  4926.7 1930.04  4956.7 1928.84  4975.9 1926.37
    4980 1924.13    5020 1924.13  5038.5 1927.15  5052.2 1930.14  5055.8 1930.83
  5070.7 1931.75  5101.5 1932.16  5144.4 1946.88  5161.7 1954.55  5192.5 1964.04
  5206.9 1968.04  5225.2 1973.73  5230.2 1975.73  5264.8 1985.66  5276.4 1989.49
  5285.5 1991.28  5295.6  1994.4  5308.1 1996.64  5325.1 2001.34  5342.3 2004.43
#Mann= 3 ,-1 , 0
  4754.3     .09       0  4956.7     .05       0  5052.2     .09       0
Bank Sta=4975.9,5038.5
Exp/Cntr=0.3,0.1

Type RM Length L Ch R = 1 ,27760   ,675,675,675
BEGIN DESCRIPTION:
Turkey_Crk_XS58
END DESCRIPTION:
XS GIS Cut Line= 6
       909643.68       730018.68       909616.08       729896.98
       909599.77       729767.75       909569.66       729703.76
         909527.       729659.85       909387.73       729588.33
#Sta/Elev= 30
  4774.6 1973.63  4807.9 1962.47  4849.8 1945.48  4864.2 1940.73  4870.4 1938.32
  4884.3 1930.97  4888.9 1929.24  4899.1 1927.55  4912.8 1926.56  4959.6 1926.75
  4965.8 1925.06    4975 1923.49  4978.3 1923.26    4980 1921.39    5020 1921.39
  5029.7 1923.54  5047.4 1926.93  5089.6 1926.48  5111.3 1928.63  5120.8 1932.55
  5151.2 1940.66  5162.3 1941.29  5186.8 1944.19  5193.8 1947.65  5217.5 1955.37
    5223 1956.31  5246.1 1962.69  5288.3 1977.21  5301.4 1980.66  5318.2 1986.22
#Mann= 3 ,-1 , 0
  4774.6     .09       0    4975     .05       0  5029.7     .09       0
Bank Sta=4975,5029.7
Exp/Cntr=0.3,0.1

Type RM Length L Ch R = 1 ,27085   ,458,458,458
BEGIN DESCRIPTION:
Turkey_Crk_XS57
END DESCRIPTION:
XS GIS Cut Line= 6
       910138.01       729684.94       910165.62       729481.69
       910161.85       729426.48       909988.71       729332.38
        909944.8       729263.38       909897.12       729117.84
#Sta/Elev= 30
  4660.4 1985.52  4680.7 1981.44  4724.6    1971  4738.7 1968.28  4754.3 1964.24
  4781.2 1958.86  4795.4 1954.65  4837.8 1947.17    4865 1938.92  4894.8 1932.11
  4915.6  1925.9  4942.2 1924.64    4971 1924.85  4974.9 1924.02    4980  1918.5
    5020  1918.5  5028.5 1924.29  5035.2 1924.42  5058.3 1924.32  5096.1 1926.75
  5111.7 1929.63  5120.3 1930.11  5133.4    1933  5165.2 1937.88  5192.8 1945.84
  5213.3 1948.75  5235.1    1955  5279.9 1969.38  5333.9 1987.59  5354.2 1992.37
#Mann= 5 ,-1 , 0
  4660.4     .09       0  4974.9     .05       0  5028.5     .09       0
  5035.2     .05       0  5133.4     .09       0
Bank Sta=4974.9,5028.5
Exp/Cntr=0.3,0.1

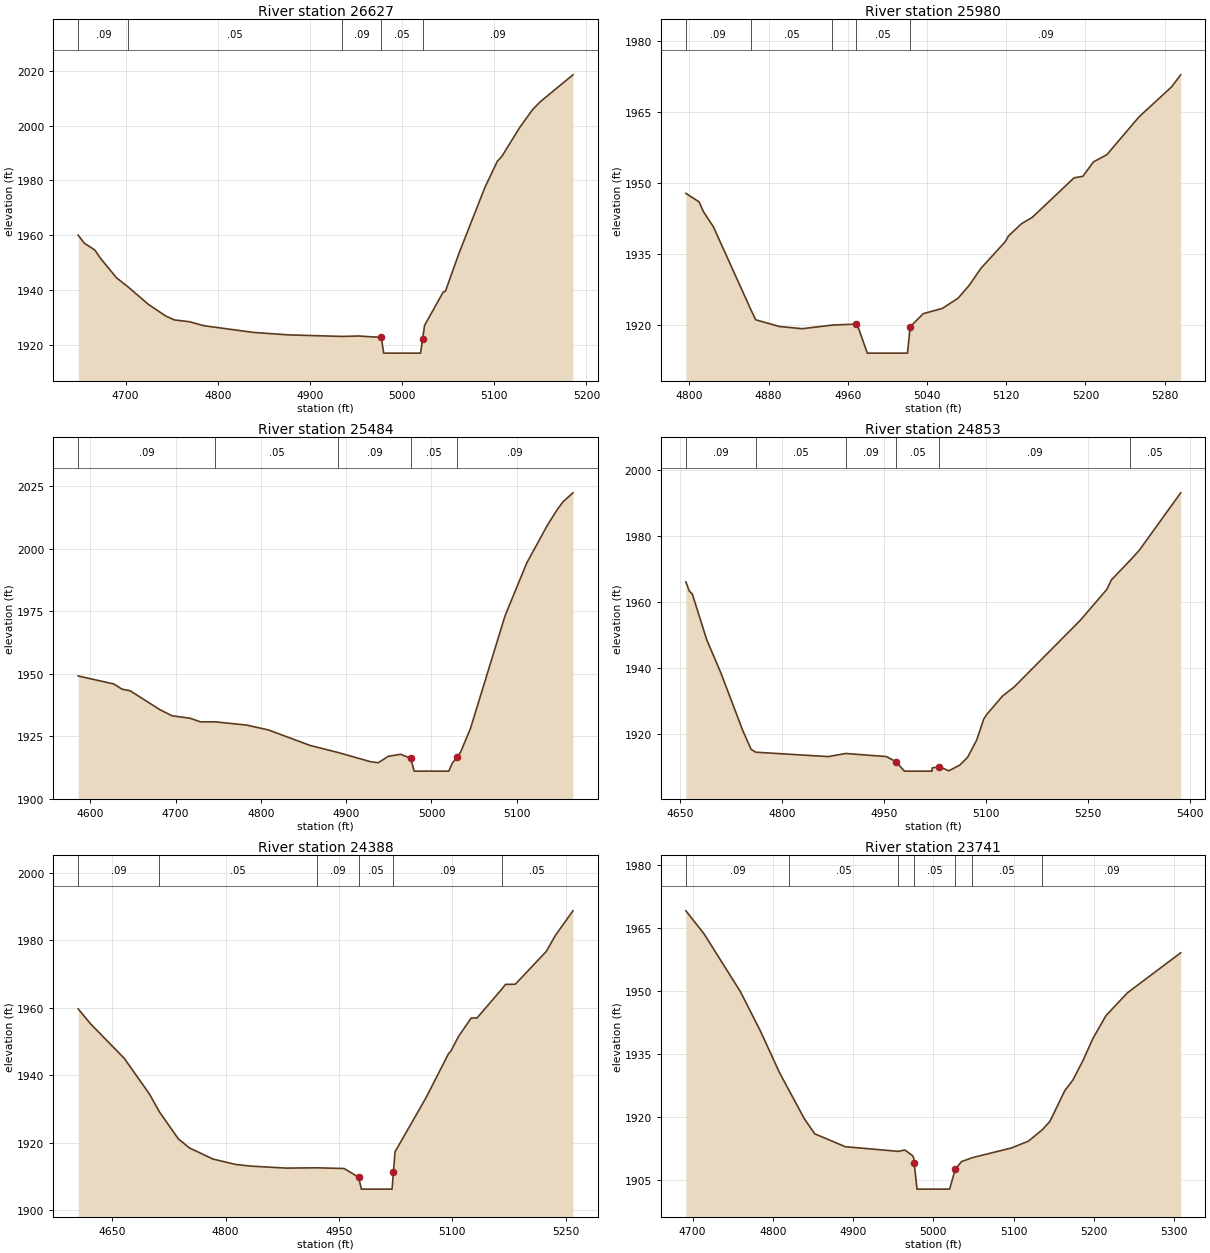
Type RM Length L Ch R = 1 ,26627   ,647,647,647
BEGIN DESCRIPTION:
Turkey_Crk_XS56
END DESCRIPTION:
XS GIS Cut Line= 6
       910466.73       729610.92        910431.6       729548.19
       910429.09       729481.69       910455.44         729296.
       910481.79       729265.89       910534.49       729105.29
#Sta/Elev= 30
  4648.5 1960.03  4655.3 1957.06  4666.7 1954.57  4672.5 1951.67  4690.1 1944.46
  4703.1 1941.02  4724.7 1934.75  4743.8 1930.45    4753 1929.07  4769.4 1928.41
  4784.9 1926.97  4838.3 1924.53  4876.8 1923.62  4934.8 1923.05  4952.5 1923.21
  4977.4 1922.69    4980 1916.96    5020 1916.96  5022.21922.123  5024.3 1927.05
  5044.6 1939.28  5046.9 1939.49  5061.8 1953.51  5089.8 1977.45  5103.2 1986.96
  5108.1 1988.73  5127.7 1999.39  5141.5 2005.84  5149.8  2008.7  5185.3 2018.54
#Mann= 5 ,-1 , 0
  4648.5     .09       0  4703.1     .05       0  4934.8     .09       0
  4977.4     .05       0  5022.2     .09       0
Bank Sta=4977.4,5022.2
Exp/Cntr=0.3,0.1

Type RM Length L Ch R = 1 ,25980   ,496,496,496
BEGIN DESCRIPTION:
Turkey_Crk_XS55
END DESCRIPTION:
XS GIS Cut Line= 6
       911087.79       729624.72       911043.88       729568.26
       911060.19       729372.53       911120.41       729317.33
       911129.19       729211.94       911144.25       729170.53
#Sta/Elev= 30
  4796.5 1947.82  4809.8 1946.02  4814.3 1943.91  4824.3 1940.73  4861.9  1923.3
    4867 1921.06  4890.8 1919.64    4914 1919.17  4944.5 1919.94  4967.9 1920.14
  4969.5 1920.07  4979.7    1914  5020.3    1914    5023 1919.58  5036.3 1922.36
  5055.4 1923.46  5071.3 1925.61  5082.6 1928.34  5094.4 1931.94  5119.2 1937.63
  5122.2 1938.78  5135.4 1941.39  5146.4 1942.76  5188.5  1951.1  5197.5 1951.44
  5208.1 1954.48  5221.7 1956.02  5254.1    1964    5287 1970.36  5296.2 1972.91
#Mann= 5 ,-1 , 0
  4796.5     .09       0  4861.9     .05       0  4944.5     .09       0
  4967.9     .05       0    5023     .09       0
Bank Sta=4967.9,5023
Exp/Cntr=0.3,0.1

Type RM Length L Ch R = 1 ,25484   ,631,631,631
BEGIN DESCRIPTION:
Turkey_Crk_XS54
END DESCRIPTION:
XS GIS Cut Line= 6
       911109.12       729617.19       911367.58       729538.15
       911474.22       729521.84       911534.45       729520.58
        911577.1       729538.15        911657.4       729589.59
#Sta/Elev= 30
  4585.9 1949.05  4627.8 1945.84  4637.3 1943.77  4646.8 1943.14  4681.9 1935.53
  4696.1 1933.11  4716.8 1932.17  4729.3 1930.69  4746.3 1930.71  4783.5 1929.39
  4808.9 1927.46    4858 1921.23  4890.9  1918.4  4928.6 1914.75  4937.7 1914.34
  4949.3  1916.9  4963.8 1917.73  4975.7 1916.12  4979.7 1910.98  5020.3 1910.98
  5024.3 1914.09  5030.2 1916.63  5034.1 1918.54  5045.8 1928.16  5086.3 1973.19
  5111.6 1994.21  5135.9 2009.38  5147.8 2015.82  5154.3 2018.77  5165.8 2022.32
#Mann= 5 ,-1 , 0
  4585.9     .09       0  4746.3     .05       0  4890.9     .09       0
  4975.7     .05       0  5030.2     .09       0
Bank Sta=4975.7,5030.2
Exp/Cntr=0.3,0.1

Type RM Length L Ch R = 1 ,24853   ,465,465,465
BEGIN DESCRIPTION:
Turkey_Crk_XS53
END DESCRIPTION:
XS GIS Cut Line= 6
       910784.16       730092.71       911050.15       729937.13
       911155.54       729935.87       911189.42       729910.78
       911242.11       729910.78       911446.62        729835.5
#Sta/Elev= 30
  4658.4 1966.03  4663.4  1963.3  4667.8 1962.42    4689 1948.59    4710 1938.46
  4742.4 1920.93  4754.3 1915.46    4761 1914.59  4867.7 1913.26  4893.4  1914.2
  4953.2 1913.27    4967 1911.73  4979.7 1908.87  5020.3 1908.87  5020.4 1909.83
  5030.8 1910.21    5045 1908.97  5061.1 1910.71  5072.5 1913.05  5085.9  1918.3
  5096.3 1924.63  5100.6 1925.99  5123.9 1931.57  5140.9  1934.3  5237.9 1954.39
  5277.2  1963.8  5283.9 1966.67  5310.9 1972.46    5325 1975.65  5385.7 1992.97
#Mann= 6 ,-1 , 0
  4658.4     .09       0    4761     .05       0  4893.4     .09       0
    4967     .05       0  5030.8     .09       0  5310.9     .05       0
Bank Sta=4967,5030.8
Exp/Cntr=0.3,0.1

Type RM Length L Ch R = 1 ,24388   ,647,647,647
BEGIN DESCRIPTION:
Turkey_Crk_XS52
END DESCRIPTION:
XS GIS Cut Line= 6
       911181.89       730428.95       911222.04       730407.62
       911279.75       730314.78       911546.99       729993.59
       911552.01       729945.91       911544.48       729913.29
#Sta/Elev= 30
  4604.8 1959.69  4621.2 1955.25  4665.7 1945.05  4699.1 1934.47  4712.4 1929.14
  4737.5 1921.12  4752.2 1918.45  4783.3 1915.16  4813.1 1913.57  4833.4 1913.07
  4880.1 1912.48  4920.4 1912.57  4956.8 1912.36  4975.9 1909.81  4979.7 1906.25
  5020.3 1906.25  5022.1 1911.35  5024.2  1917.3  5065.3 1933.37  5095.1 1946.43
  5097.9 1947.08  5108.4 1951.55    5125 1956.98  5132.7 1956.97  5165.2 1965.44
  5170.5 1966.93  5183.5 1966.99  5224.4 1976.71  5236.5 1981.46  5259.7 1988.74
#Mann= 6 ,-1 , 0
  4604.8     .09       0  4712.4     .05       0  4920.4     .09       0
  4975.9     .05       0  5022.1     .09       0  5165.2     .05       0
Bank Sta=4975.9,5022.1
Exp/Cntr=0.3,0.1

Type RM Length L Ch R = 1 ,23741   ,423,423,423
BEGIN DESCRIPTION:
Turkey_Crk_XS51
END DESCRIPTION:
XS GIS Cut Line= 6
       911195.69       730570.73        911347.5       730573.24
       911465.44        730590.8       911593.42       730679.88
       911674.97       730712.51       911762.79       730763.95
#Sta/Elev= 30
  4691.6 1969.02  4714.3 1963.53  4759.5 1949.79  4784.4 1940.44  4808.5 1930.41
  4820.1  1926.3  4839.4 1919.46  4852.2 1915.93  4890.3 1912.86  4956.5 1911.75
  4964.4 1912.08    4974 1910.76  4975.4  1910.3  4976.21908.897  4979.7 1902.76
  5020.3 1902.76  5027.3 1907.47  5035.1 1909.31  5048.5 1910.24  5097.5 1912.57
  5118.5 1914.18  5135.9 1916.91  5145.3 1918.88  5163.8 1926.19  5173.9 1928.72
  5186.4 1933.33  5198.8 1938.59  5215.2 1944.07    5242 1949.51  5308.3 1959.03
#Mann= 7 ,-1 , 0
  4691.6     .09       0  4820.1     .05       0  4956.5     .09       0
  4976.2     .05       0  5027.3     .09       0  5048.5     .05       0
  5135.9     .09       0
Bank Sta=4976.2,5027.3
Exp/Cntr=0.3,0.1