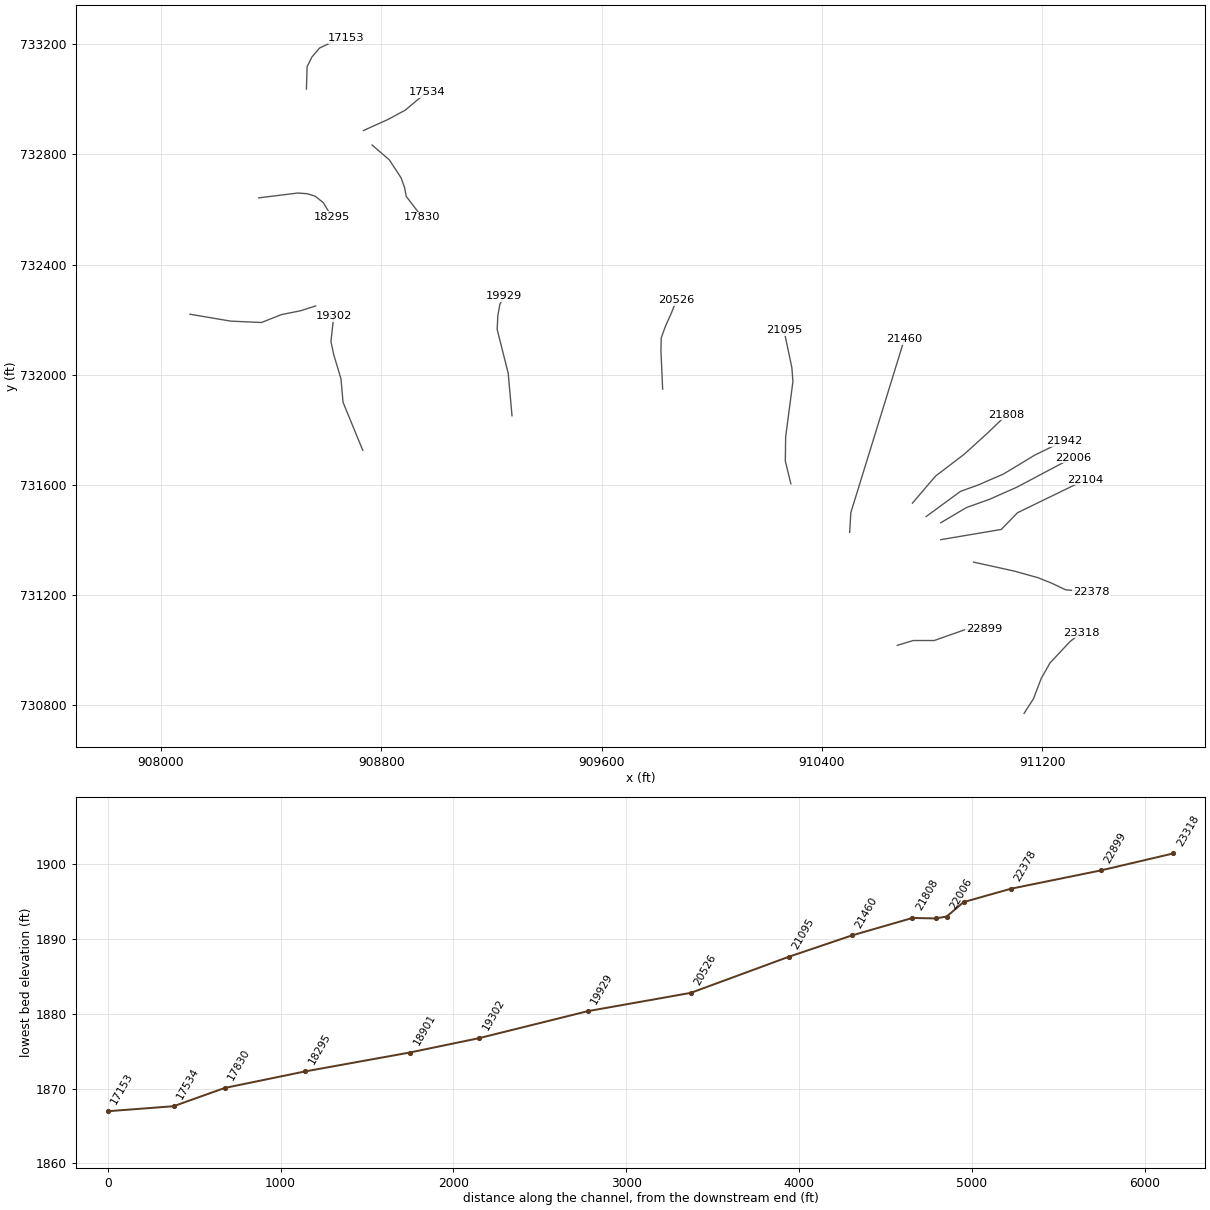
HEC-RAS study lds_turkey_crk.prj: Turkey Creek Limited Detail Study

--- lds_turkey_crk.g01 (geometry) --- (continued)

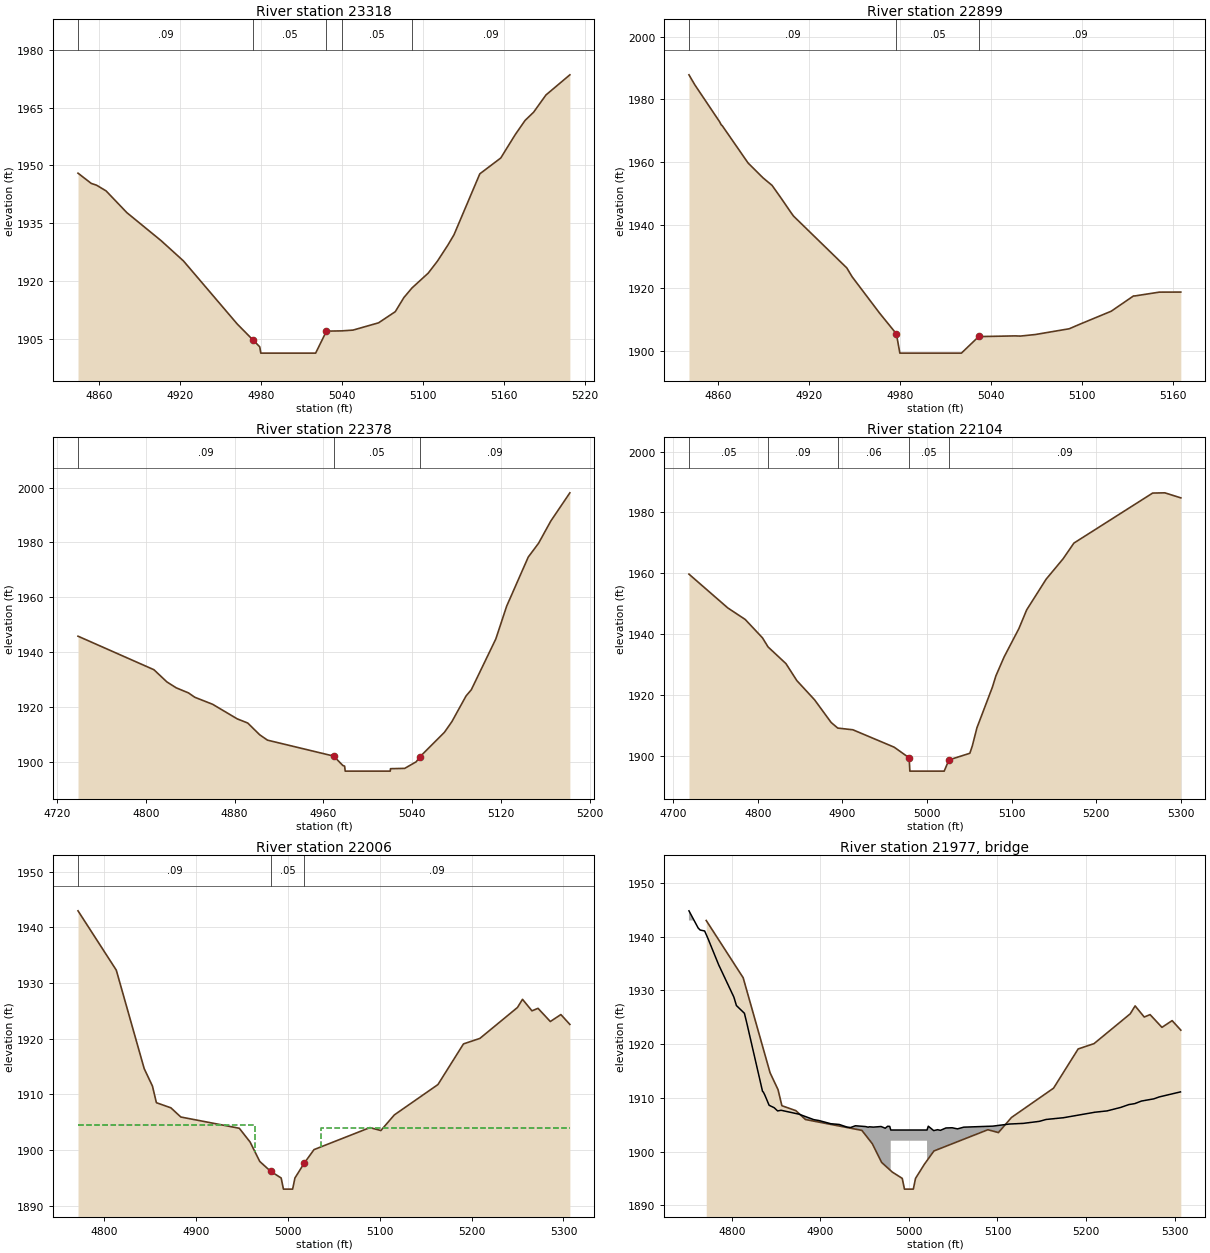
Type RM Length L Ch R = 1 ,23318   ,419,419,419
BEGIN DESCRIPTION:
Turkey_Crk_XS50
END DESCRIPTION:
XS GIS Cut Line= 6
       911134.21       730768.97       911168.09       730821.66
       911196.94       730896.94       911228.31       730952.15
       911301.08       731029.93       911341.23        731061.3
#Sta/Elev= 30
  4844.3 1948.01  4854.1 1945.36  4858.1 1944.89  4865.1 1943.42  4880.5 1937.79
  4905.9 1930.53  4922.4  1925.3  4962.3 1908.95  4974.21904.735  4978.9 1903.07
  4979.7 1901.44  5020.3 1901.44  5028.3 1907.13  5039.7  1907.2    5048  1907.4
  5066.9 1909.28  5079.3 1912.17  5085.6 1915.79  5091.6 1918.28  5103.7 1922.15
  5110.5 1925.24  5118.3 1929.43  5122.8 1932.09  5141.9 1947.84  5157.4 1951.93
  5168.1 1957.97  5175.4 1961.65  5181.7 1963.77  5190.9 1968.25  5208.6 1973.46
#Mann= 5 ,-1 , 0
  4844.3     .09       0  4974.2     .05       0  5028.3     .09       0
  5039.7     .05       0  5091.6     .09       0
Bank Sta=4974.2,5028.3
Exp/Cntr=0.3,0.1

Type RM Length L Ch R = 1 ,22899   ,521,521,521
BEGIN DESCRIPTION:
Turkey_Crk_XS49
END DESCRIPTION:
XS GIS Cut Line= 6
       910673.75       731016.13       910731.47        731033.7
         910808.        731033.7       910868.22       731055.03
       910922.17       731073.85       910988.67       731076.36
#Sta/Elev= 30
  4840.6 1987.82  4844.5 1984.61  4860.8 1972.88  4861.9 1971.88  4862.5 1971.65
  4862.9 1971.38  4879.6 1959.73  4889.5 1954.98  4895.4 1952.61  4900.9 1948.87
  4908.1  1943.8  4909.6 1942.81  4944.7 1926.31  4948.2  1923.5  4966.3 1911.93
  4977.4 1905.32  4979.7 1899.17  5020.3 1899.17  5031.8 1904.49  5033.6 1904.45
  5055.7 1904.66  5059.2  1904.6  5069.1  1905.1  5091.4 1906.93  5098.4 1908.38
  5119.1 1912.52  5133.8 1917.39  5134.6 1917.38  5150.8  1918.6    5165 1918.62
#Mann= 3 ,-1 , 0
  4840.6     .09       0  4977.4     .05       0  5031.8     .09       0
Bank Sta=4977.4,5031.8
Exp/Cntr=0.3,0.1

Type RM Length L Ch R = 1 ,22378   ,274,274,274
BEGIN DESCRIPTION:
Turkey_Crk_XS48
END DESCRIPTION:
XS GIS Cut Line= 6
       910951.03        731318.5       911099.08       731285.88
        911184.4       731262.04       911234.58       731241.97
       911284.77       731218.13       911377.61       731209.35
#Sta/Elev= 30
    4739 1945.86  4807.4 1933.65  4819.1  1929.2  4827.5 1927.05  4838.5 1925.21
  4844.2 1923.62  4860.3 1921.06  4882.4 1915.76  4891.9 1914.24  4902.7 1909.95
  4909.7    1908  4969.3  1902.2  4977.5  1898.8  4979.2 1898.53  4979.7 1896.72
  5020.3 1896.72  5020.5 1897.61  5033.3 1897.72  5043.7 1900.13  5046.8 1901.85
  5069.1 1910.86  5075.8 1914.74  5088.6 1924.11  5093.3 1926.35  5115.4 1944.86
  5125.1 1956.74  5144.6 1974.67  5153.9 1979.71  5164.9 1987.78  5182.1 1998.07
#Mann= 3 ,-1 , 0
    4739     .09       0  4969.3     .05       0  5046.8     .09       0
Bank Sta=4969.3,5046.8
Exp/Cntr=0.3,0.1

Type RM Length L Ch R = 1 ,22104   ,98,98,98
BEGIN DESCRIPTION:
turkey crk z8
END DESCRIPTION:
XS GIS Cut Line= 4
       910831.87       731400.19       911051.31       731437.33
        911110.4       731498.09       911356.85       731617.94
#Sta/Elev= 30
  4718.6 1959.69  4764.6 1948.56  4785.1 1944.79  4805.5 1938.75  4812.1 1935.76
  4833.3 1930.26  4846.1  1924.7  4867.1 1918.37  4886.7 1910.91  4894.5 1909.08
  4912.4 1908.52  4961.2  1902.8  4978.9  1899.3  4979.7 1894.93  5020.3 1894.93
  5025.9 1898.61  5050.6  1900.8  5053.5 1903.18    5059 1909.18  5077.2 1922.48
  5081.4 1926.24  5091.2 1932.51  5108.6 1941.79  5117.8 1947.94  5140.8 1958.03
  5160.9 1964.75  5173.6 1969.89  5266.7 1986.34  5281.1 1986.42    5300 1984.76
#Mann= 5 ,-1 , 0
  4718.6     .05       0  4812.1     .09       0  4894.5     .06       0
  4978.9     .05       0  5025.9     .09       0
Bank Sta=4978.9,5025.9
Exp/Cntr=0.5,0.3

Type RM Length L Ch R = 1 ,22006   ,64,64,64
BEGIN DESCRIPTION:
Turkey_Crk_XS47
END DESCRIPTION:
XS GIS Cut Line= 5
       910831.76       731461.66       910924.68       731516.74
       911008.75       731546.85       911107.86       731590.76
       911311.12       731698.67
#Sta/Elev= 30
  4771.2 1942.98  4812.9 1932.33  4843.3 1914.64  4852.3  1911.5  4856.6 1908.52
  4872.4  1907.6  4883.2 1905.95  4946.9 1903.93  4958.7 1901.45  4969.2 1897.97
  4981.2 1896.18  4992.5    1895    4995    1893    5005    1893  5007.5    1895
  5017.61897.656  5028.3  1900.1  5089.2 1904.05  5101.1 1903.52  5115.8 1906.33
  5163.3 1911.78  5191.1 1919.08    5209 1920.07  5249.9 1925.62  5255.4 1927.09
  5265.7 1925.02  5272.3 1925.47  5285.7  1923.1  5297.2 1924.35    5307 1922.58
#Mann= 3 ,-1 , 0
  4771.2     .09       0  4981.2     .05       0  5017.6     .09       0
#XS Ineff= 2 , 0
       0    4964 1904.59    5036       0 1903.97
Permanent Ineff=
       F       F
Bank Sta=4981.2,5017.6
Exp/Cntr=0.5,0.3

Type RM Length L Ch R = 3 ,21977   ,,,
BEGIN DESCRIPTION:
Turkey_Crk_XS46
Structure ID: Old NC 20 HWY SR 1629
Approximate Survey Structure
END DESCRIPTION:
Bridge Culvert--1,0,-1,-1, 0
Deck Dist Width WeirC Skew NumUp NumDn MinLoCord MaxHiCord MaxSubmerge Is_Ogee
15.5,25,3,0, 60, 60, , , , 0, 1,1,,
  4751.7  4762.1  4764.3  4769.4  4773.1  4785.2  4802.4  4805.3  4814.3  4817.1
  4834.8  4835.7  4837.5  4842.2  4847.9  4851.8  4855.7  4876.1  4892.6  4898.3
  4911.8  4921.4  4930.1  4934.1  4939.6  4951.2  4954.1  4955.2  4959.8  4968.6
  4973.3    4976  4978.4  4979.5  4979.5  5020.5  5020.5  5021.9    5028  5032.4
  5035.6  5041.8  5048.8  5054.9  5061.9  5094.7  5113.4  5128.9  5147.3  5154.8
  5174.7    5210  5223.6  5239.1  5248.3    5255  5262.6  5276.6  5282.5  5306.6
 1944.78 1941.58 1941.21 1941.03 1939.65 1934.75 1928.73 1927.15 1925.72 1923.83
 1911.16 1911.06 1910.45  1908.6 1908.15 1907.55 1907.67 1906.94 1905.93 1905.77
 1905.17 1905.03 1904.55 1904.46 1904.79 1904.64 1904.52  1904.6 1904.54 1904.65
 1904.33  1904.7 1904.67    1904    1904    1904    1904 1904.71 1903.89 1904.06
 1903.94 1904.38 1904.42 1904.21 1904.53 1904.72 1905.11 1905.23 1905.61 1905.96
 1906.29 1907.31 1907.55  1908.2 1908.73 1908.91 1909.39  1909.8 1910.15 1911.09
    1873    1873    1873    1873    1873    1873    1873    1873    1873    1873
    1873    1873    1873    1873    1873    1873    1873    1873    1873    1873
    1873    1873    1873    1873    1873    1873    1873    1873    1873    1873
    1873    1873    1873    1873    1902    1902    1873    1873    1873    1873
    1873    1873    1873    1873    1873    1873    1873    1873    1873    1873
    1873    1873    1873    1873    1873    1873    1873    1873    1873    1873
  4751.7  4762.1  4764.3  4769.4  4773.1  4785.2  4802.4  4805.3  4814.3  4817.1
  4834.8  4835.7  4837.5  4842.2  4847.9  4851.8  4855.7  4876.1  4892.6  4898.3
  4911.8  4921.4  4930.1  4934.1  4939.6  4951.2  4954.1  4955.2  4959.8  4968.6
  4973.3    4976  4978.4  4979.5  4979.5  5020.5  5020.5  5021.9    5028  5032.4
  5035.6  5041.8  5048.8  5054.9  5061.9  5094.7  5113.4  5128.9  5147.3  5154.8
  5174.7    5210  5223.6  5239.1  5248.3    5255  5262.6  5276.6  5282.5  5306.6
 1944.78 1941.58 1941.21 1941.03 1939.65 1934.75 1928.73 1927.15 1925.72 1923.83
 1911.16 1911.06 1910.45  1908.6 1908.15 1907.55 1907.67 1906.94 1905.93 1905.77
 1905.17 1905.03 1904.55 1904.46 1904.79 1904.64 1904.52  1904.6 1904.54 1904.65
 1904.33  1904.7 1904.67    1904    1904    1904    1904 1904.71 1903.89 1904.06
 1903.94 1904.38 1904.42 1904.21 1904.53 1904.72 1905.11 1905.23 1905.61 1905.96
 1906.29 1907.31 1907.55  1908.2 1908.73 1908.91 1909.39  1909.8 1910.15 1911.09
    1873    1873    1873    1873    1873    1873    1873    1873    1873    1873
    1873    1873    1873    1873    1873    1873    1873    1873    1873    1873
    1873    1873    1873    1873    1873    1873    1873    1873    1873    1873
    1873    1873    1873    1873    1902    1902    1873    1873    1873    1873
    1873    1873    1873    1873    1873    1873    1873    1873    1873    1873
    1873    1873    1873    1873    1873    1873    1873    1873    1873    1873
Abutment Skew #Up #Dn= , 2 , 2
  4979.5    4982
    1902 1896.22
  4979.5    4982
    1902 1896.08
Abutment Skew #Up #Dn= , 2 , 2
    5018  5020.5
 1897.76    1902
    5018  5020.5
 1895.58    1902
BR Coef= 1 , 1 , 0 ,1.25, 0 ,,,0.8,0,2,0,
WSPro=,,,, 1 ,,,, 0 ,,,, 0 ,,,,-1 ,-1 ,-1 , 0 , 0 , 0 , 0 , 0
BC Design=,, 0 ,, 0 ,,,,,,
BC HTab HWMax=1942.98

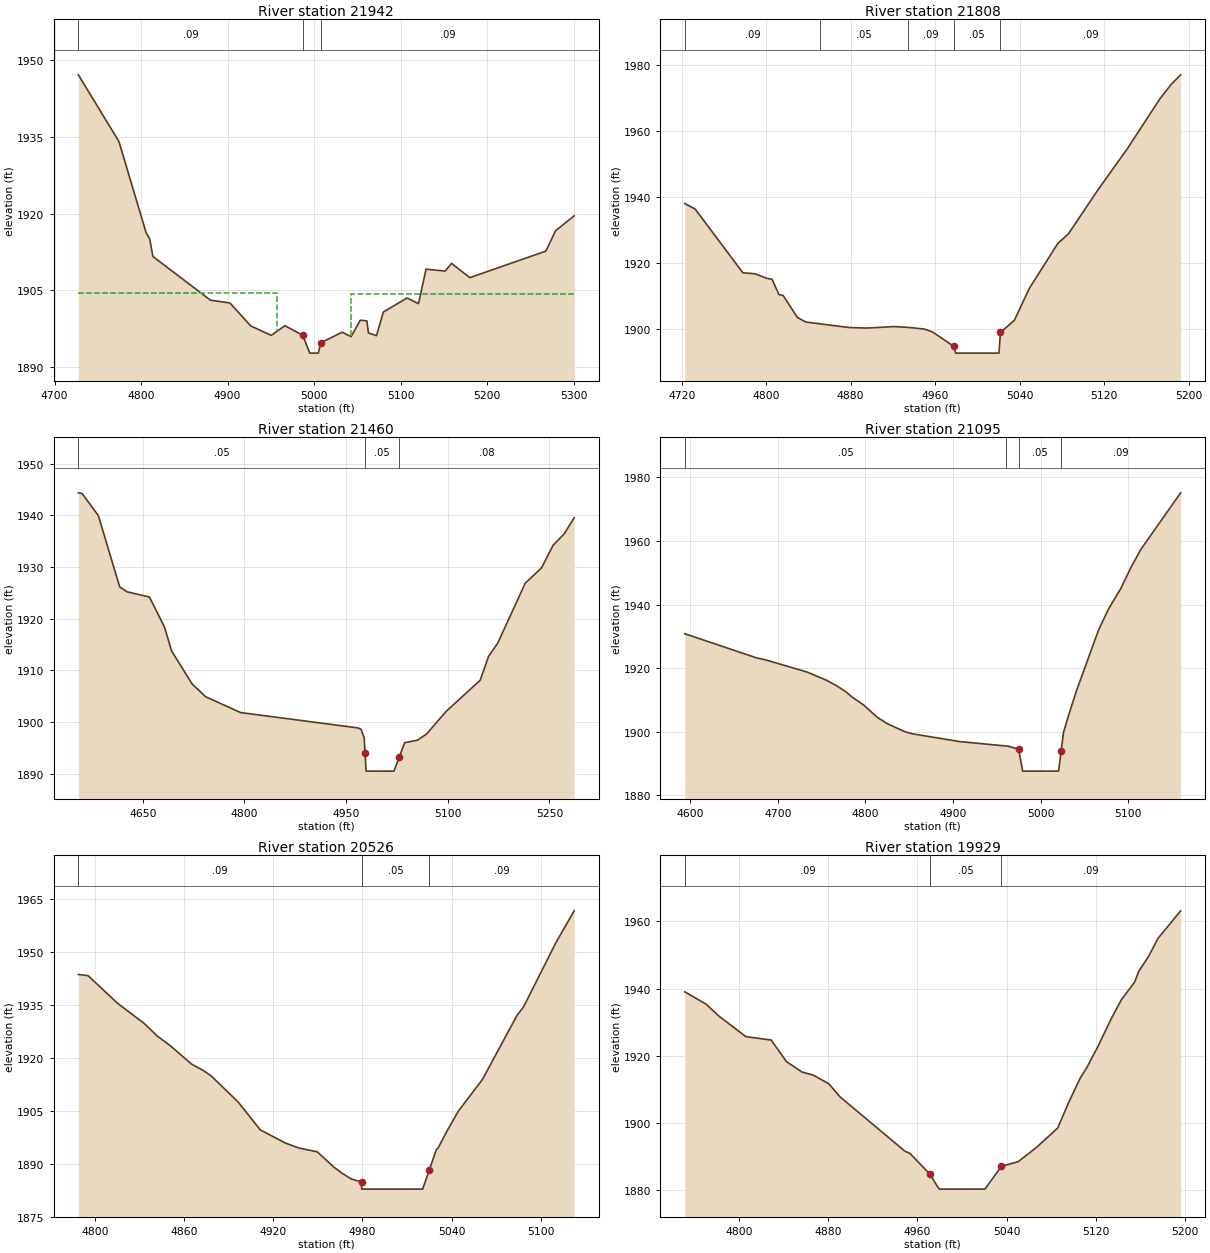
Type RM Length L Ch R = 1 ,21942   ,134,134,134
BEGIN DESCRIPTION:
Turkey_Crk_XS45
END DESCRIPTION:
XS GIS Cut Line= 6
       910778.68       731484.24       910903.35       731575.71
       910966.09       731598.29       911058.93       731638.44
       911173.11       731707.45        911278.5       731758.89
#Sta/Elev= 30
  4727.5 1947.18  4774.4 1934.15  4805.8 1916.33    4810  1915.1  4813.7 1911.65
  4880.2 1903.11  4902.8 1902.55  4926.8 1898.07  4950.4 1896.22  4966.3 1898.12
  4986.9 1896.23    4995 1892.75    5005 1892.75  5007.5 1894.75  5032.4 1896.84
  5042.8 1895.97  5053.4 1899.19    5061 1899.06  5062.8 1896.71  5072.1 1896.16
  5080.1  1900.8  5107.5 1903.54  5120.7 1902.43  5129.4 1909.17  5151.5  1908.8
  5158.9 1910.31    5180 1907.51  5267.9  1912.7  5279.1 1916.68  5300.6 1919.61
#Mann= 3 ,-1 , 0
  4727.5     .09       0  4986.9     .05       0  5007.5     .09       0
#XS Ineff= 2 , 0
       0    4957 1904.58    5043       0 1904.39
Permanent Ineff=
       F       F
Bank Sta=4986.9,5007.5
Exp/Cntr=0.5,0.3

Type RM Length L Ch R = 1 ,21808   ,348,348,348
BEGIN DESCRIPTION:
Turkey_Crk_XS44
END DESCRIPTION:
XS GIS Cut Line= 5
       910728.96       731533.05       910812.56       731631.06
       910917.59       731711.24       911002.29       731788.03
       911070.05       731853.53
#Sta/Elev= 30
    4723 1938.07  4732.8 1936.41    4778 1917.12  4789.5 1916.82    4801 1915.41
  4805.6 1915.17  4812.1 1910.56  4816.2 1910.23  4829.7 1903.58  4837.7 1902.21
  4851.3 1901.66  4878.2 1900.57  4895.2 1900.39  4920.9 1900.84  4934.4 1900.61
    4950 1900.08  4957.5 1899.23  4977.9 1894.82  4979.5 1892.81  5020.5 1892.81
  5021.9 1899.09  5035.1 1902.75  5049.3 1912.43  5076.2 1925.99  5086.3 1928.92
  5114.4  1942.3  5142.1 1954.69  5172.7 1969.68  5183.7 1974.18  5192.5 1977.02
#Mann= 5 ,-1 , 0
    4723     .09       0  4851.3     .05       0  4934.4     .09       0
  4977.9     .05       0  5021.9     .09       0
Bank Sta=4977.9,5021.9
Exp/Cntr=0.3,0.1

Type RM Length L Ch R = 1 ,21460   ,365,365,365
BEGIN DESCRIPTION:
turkey crk z11
END DESCRIPTION:
XS GIS Cut Line= 3
       910500.86       731426.65       910505.11       731498.23
       910699.66       732128.89
#Sta/Elev= 30
  4554.8 1944.33  4560.4  1944.2  4584.4 1939.91  4615.8 1926.15  4626.7 1925.19
  4659.8 1924.16  4681.9 1918.38  4692.5 1913.72  4722.8 1907.34  4742.7 1904.88
  4794.2 1901.82  4967.5 1898.85  4972.1 1898.56  4976.6 1896.95  4977.91894.054
  4979.5 1890.49  5020.5 1890.49  5028.21893.154  5036.4 1895.99  5055.6 1896.49
  5068.9  1897.7  5097.7 1902.06  5147.8 1908.07  5160.2 1912.69  5173.7 1915.25
  5214.3 1926.84  5238.5 1929.83  5255.2 1934.15    5272 1936.44  5286.5 1939.49
#Mann= 3 ,-1 , 0
  4554.8     .05       0  4977.9     .05       0  5028.2     .08       0
Bank Sta=4977.9,5028.2
Exp/Cntr=0.3,0.1

Type RM Length L Ch R = 1 ,21095   ,569,569,569
BEGIN DESCRIPTION:
Turkey_Crk_XS43
END DESCRIPTION:
XS GIS Cut Line= 6
       910287.32       731603.31       910267.24       731686.12
        910268.5       731773.94       910294.85       731974.69
       910291.08       732024.88       910262.23       732161.63
#Sta/Elev= 30
  4593.8 1930.84  4674.8 1923.33    4687 1922.54  4733.5 1918.78    4756 1916.15
  4767.1 1914.49  4778.8 1912.37  4783.8 1911.11  4798.1  1908.4  4813.6 1904.55
  4825.3 1902.52  4845.6 1899.97  4853.4 1899.38  4907.5 1896.93  4960.6 1895.54
  4963.2 1895.47  4974.9 1894.53  4979.5 1887.64  5020.5 1887.64  5023.41893.932
  5026.1 1899.79  5031.3  1904.6  5040.7 1912.74    5064 1930.41  5066.7 1932.32
  5077.4 1938.57  5091.4 1944.98    5103  1951.6  5114.3  1957.3  5159.8 1975.13
#Mann= 4 ,-1 , 0
  4593.8     .05       0  4960.6     .09       0  4974.9     .05       0
  5023.4     .09       0
Bank Sta=4974.9,5023.4
Exp/Cntr=0.3,0.1

Type RM Length L Ch R = 1 ,20526   ,597,597,597
BEGIN DESCRIPTION:
Turkey_Crk_XS42
END DESCRIPTION:
XS GIS Cut Line= 6
       909821.84       731947.09       909815.57       732087.61
       909816.82       732134.03       909831.88       732175.43
       909853.21       732223.11       909872.03       732269.53
#Sta/Elev= 30
  4788.9  1943.6  4795.4 1943.28  4815.3 1935.44  4833.2 1929.73    4842 1926.16
  4850.8 1923.42  4865.1  1918.2    4873  1916.4  4878.3 1914.86  4896.4 1907.47
  4911.3 1899.57  4928.3 1895.84  4937.6  1894.4  4949.6 1893.37    4961 1888.96
  4966.4 1887.28  4972.3 1885.71  4979.4 1884.82  4979.5  1882.8  5020.5  1882.8
    50251888.278  5029.7    1894  5030.8 1894.37  5035.9  1898.5  5044.4 1904.83
  5060.7 1913.86    5084 1932.04  5088.4 1934.43    5110 1952.53  5122.4 1961.63
#Mann= 3 ,-1 , 0
  4788.9     .09       0  4979.4     .05       0    5025     .09       0
Bank Sta=4979.4,5025
Exp/Cntr=0.3,0.1

Type RM Length L Ch R = 1 ,19929   ,627,627,627
BEGIN DESCRIPTION:
Turkey_Crk_XS41
END DESCRIPTION:
XS GIS Cut Line= 6
       909274.81       731850.48       909261.01        732004.8
       909220.86       732164.14       909223.37       732214.33
        909230.9       732255.73       909245.95       732284.59
#Sta/Elev= 30
  4751.6 1939.04  4770.8 1935.35  4782.2 1931.82  4806.3 1925.72    4829 1924.69
  4842.7 1918.29  4856.6 1915.19  4866.7 1914.27  4880.7 1911.69  4890.5 1907.86
    4949  1891.6  4953.3 1890.99  4971.2 1884.83  4979.5 1880.35  5020.5 1880.35
  5035.3 1887.13  5050.4 1888.52  5066.7 1892.75  5085.7 1898.51  5095.4    1906
  5105.9 1913.36  5111.9 1916.54  5121.2  1922.4  5133.7 1931.01  5142.8 1936.68
  5154.6 1941.89  5158.3 1945.08  5167.4 1949.71  5175.5 1954.88  5195.9 1963.14
#Mann= 3 ,-1 , 0
  4751.6     .09       0  4971.2     .05       0  5035.3     .09       0
Bank Sta=4971.2,5035.3
Exp/Cntr=0.3,0.1

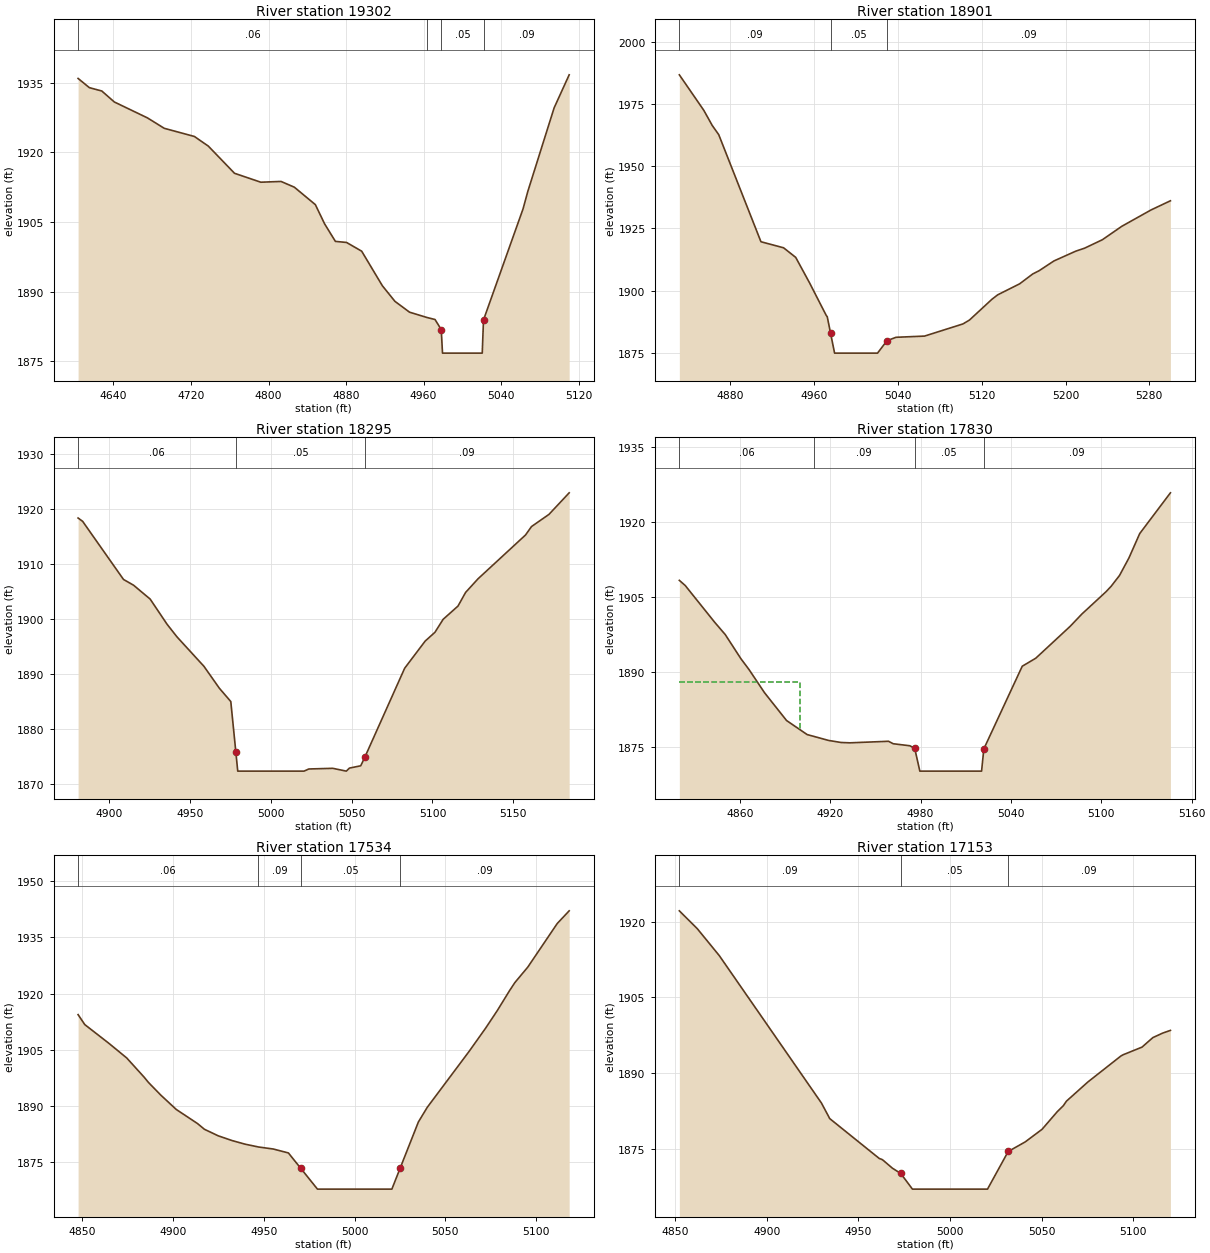
Type RM Length L Ch R = 1 ,19302   ,401,401,401
BEGIN DESCRIPTION:
Turkey_Crk_XS40
END DESCRIPTION:
XS GIS Cut Line= 6
        908732.8       731725.01       908661.28       731899.41
       908653.76       731984.73       908627.41       732072.55
       908617.37       732120.23       908627.41       732211.82
#Sta/Elev= 30
  4603.5 1935.92  4615.1 1933.94    4628 1933.21  4640.9 1930.85    4675 1927.43
  4692.4 1925.18  4723.5 1923.42  4737.9 1921.34  4764.9 1915.49    4792 1913.57
  4812.9 1913.73  4826.6  1912.5  4848.3 1908.74  4857.9 1904.58    4869 1900.82
  4880.5 1900.59  4896.1 1898.71  4917.5 1891.25  4930.4 1887.91  4945.5 1885.57
  4963.4 1884.43  4971.8 1883.99  4978.2 1881.82  4979.5 1876.75  5020.5 1876.75
  5021.8 1883.89  5062.6 1907.82  5067.5 1911.57  5094.7  1929.6  5110.2  1936.7
#Mann= 4 ,-1 , 0
  4603.5     .06       0  4963.4     .09       0  4978.2     .05       0
  5021.8     .09       0
Bank Sta=4978.2,5021.8
Exp/Cntr=0.3,0.1

Type RM Length L Ch R = 1 ,18901   ,606,606,606
BEGIN DESCRIPTION:
Turkey_Crk_XS39
END DESCRIPTION:
XS GIS Cut Line= 6
       908105.47       732219.35       908253.52       732194.25
       908365.19       732189.24       908437.96       732218.09
       908506.96       732231.89       908562.17       732249.46
#Sta/Elev= 30
  4831.3 1986.69  4854.6 1972.46  4862.7 1966.34  4868.9 1962.65  4909.2  1919.6
  4930.8 1917.17  4942.4 1913.31  4955.6 1903.08  4971.5 1890.01  4972.5 1889.46
  4975.61882.981  4979.5 1874.83  5020.5 1874.83  5029.5 1879.82  5038.1 1881.19
  5065.4 1881.68    5102 1886.56  5108.2  1888.1  5129.7 1896.47  5135.2 1898.26
  5156.1 1902.67  5168.7 1906.66  5174.8 1907.97  5188.9 1911.88  5209.6 1915.79
  5218.2 1917.02  5235.1  1920.4  5253.7 1925.81  5281.7  1932.4  5300.1 1936.06
#Mann= 3 ,-1 , 0
  4831.3     .09       0  4975.6     .05       0  5029.5     .09       0
Bank Sta=4975.6,5029.5
Exp/Cntr=0.3,0.1

Type RM Length L Ch R = 1 ,18295   ,465,465,465
BEGIN DESCRIPTION:
Turkey_Crk_XS38
END DESCRIPTION:
XS GIS Cut Line= 6
       908355.15       732642.17       908496.92       732659.73
        908530.8       732657.22       908559.66       732648.44
       908589.77        732624.6       908619.88       732574.41
#Sta/Elev= 30
  4880.7 1918.32  4883.5 1917.72  4908.8 1907.15    4915 1906.11  4925.3 1903.58
  4935.8 1898.99  4941.9 1896.71  4958.6 1891.35  4968.1 1887.38  4975.2 1884.95
  4978.31875.831  4979.5  1872.3  5020.5  1872.3  5023.5 1872.69  5038.3 1872.81
  5046.7  1872.3  5048.6 1872.85  5055.6 1873.27  5058.3 1874.93  5082.8 1891.01
  5095.5 1895.95  5101.5 1897.53  5106.6  1899.9  5115.8 1902.31  5120.5 1904.79
  5128.2 1907.27  5157.6 1915.24  5161.3 1916.77  5172.1 1918.98  5184.6  1922.9
#Mann= 3 ,-1 , 0
  4880.7     .06       0  4978.3     .05       0  5058.3     .09       0
Bank Sta=4978.3,5058.3
Exp/Cntr=0.3,0.1

Type RM Length L Ch R = 1 ,17830   ,296,296,296
BEGIN DESCRIPTION:
Turkey_Crk_XS37
END DESCRIPTION:
XS GIS Cut Line= 6
       908766.68       732834.13       908829.41       732780.18
       908872.07       732714.94       908884.61       732679.81
       908890.89       732647.18        908948.6       732571.91
#Sta/Elev= 30
  4819.8 1908.32  4823.7 1907.29  4843.3 1899.91  4850.3 1897.45  4860.7 1892.61
  4866.1 1890.43  4876.4 1885.79    4891 1880.23  4904.7 1877.41    4909 1877.06
  4918.9 1876.24  4927.2 1875.83    4933 1875.76  4958.7 1876.07  4961.8 1875.58
  4972.9 1875.17  4976.1 1874.65  4979.5 1870.09  5020.5 1870.09    5022 1874.55
  5047.5 1891.11  5056.5 1892.72  5079.3  1899.1  5087.1 1901.57  5103.1 1906.03
  5106.5 1907.12  5112.1  1909.3  5118.4 1912.84  5125.5 1917.69  5145.9 1925.86
#Mann= 4 ,-1 , 0
  4819.8     .06       0    4909     .09       0  4976.1     .05       0
    5022     .09       0
#XS Ineff= 2 , 0
       0    4900    1888               0
Permanent Ineff=
       F       F
Bank Sta=4976.1,5022
Exp/Cntr=0.3,0.1

Type RM Length L Ch R = 1 ,17534   ,381,381,381
BEGIN DESCRIPTION:
Turkey_Crk_XS36
END DESCRIPTION:
XS GIS Cut Line= 4
       908735.31       732886.82       908824.39       732926.97
       908887.12       732960.85       908964.91       733026.09
#Sta/Elev= 30
  4847.6 1914.35  4851.3 1911.68  4864.6 1906.66  4874.4 1902.75  4883.9 1897.66
  4886.4 1896.19  4893.2  1892.8  4901.7 1888.97  4913.4  1885.2  4917.2 1883.67
  4924.8 1881.92  4932.5 1880.64  4939.7 1879.67    4947 1878.93  4955.2 1878.38
  4963.5 1877.33  4970.21873.276  4979.5 1867.65  5020.5 1867.65  5025.21873.432
  5035.1 1885.61    5040 1889.54  5063.1 1904.54  5072.1 1910.69  5078.6 1915.44
  5085.4 1920.81  5088.3 1922.94  5095.4 1927.07  5111.6 1938.72  5118.2 1942.13
#Mann= 4 ,-1 , 0
  4847.6     .06       0    4947     .09       0  4970.2     .05       0
  5025.2     .09       0
Bank Sta=4970.2,5025.2
Exp/Cntr=0.3,0.1

Type RM Length L Ch R = 1 ,17153   ,318,318,318
BEGIN DESCRIPTION:
Turkey_Crk_XS35
END DESCRIPTION:
XS GIS Cut Line= 6
       908528.29       733037.38        908530.8       733118.94
       908548.37       733154.07       908575.97       733186.69
       908629.92       733211.78       908673.83       733221.82
#Sta/Elev= 26
  4852.2 1922.14    4862  1918.6    4874 1913.27  4929.8 1884.05  4933.8 1881.33
  4934.3 1880.97  4961.4 1873.05  4962.8 1872.87  4963.5  1872.7  4968.6 1871.12
  4973.1 1870.09  4979.5 1866.98  5020.5 1866.98  5031.8 1874.44  5041.1 1876.34
  5050.3 1878.84  5058.6 1882.33  5061.9 1883.51  5063.6 1884.41  5075.3 1888.21
  5093.4 1893.38  5094.7 1893.63  5104.9 1895.13  5110.8 1897.01  5116.2 1897.91
  5120.4 1898.44
#Mann= 3 ,-1 , 0
  4852.2     .09       0  4973.1     .05       0  5031.8     .09       0
Bank Sta=4973.1,5031.8
Exp/Cntr=0.3,0.1