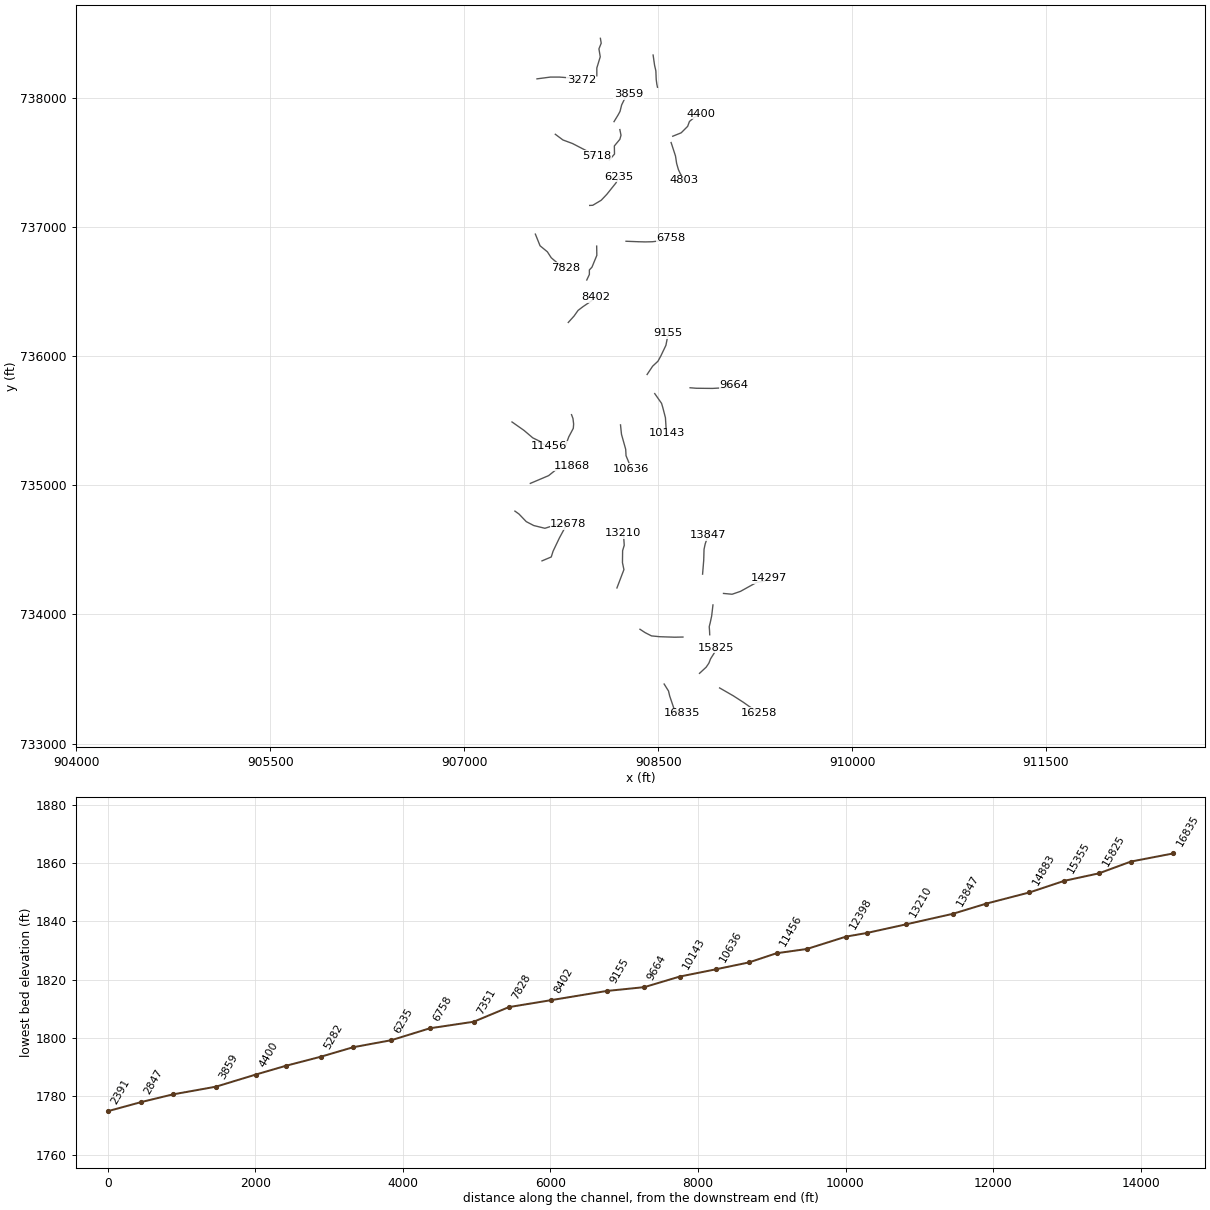
HEC-RAS study lds_turkey_crk.prj: Turkey Creek Limited Detail Study

--- lds_turkey_crk.g01 (geometry) --- (continued)

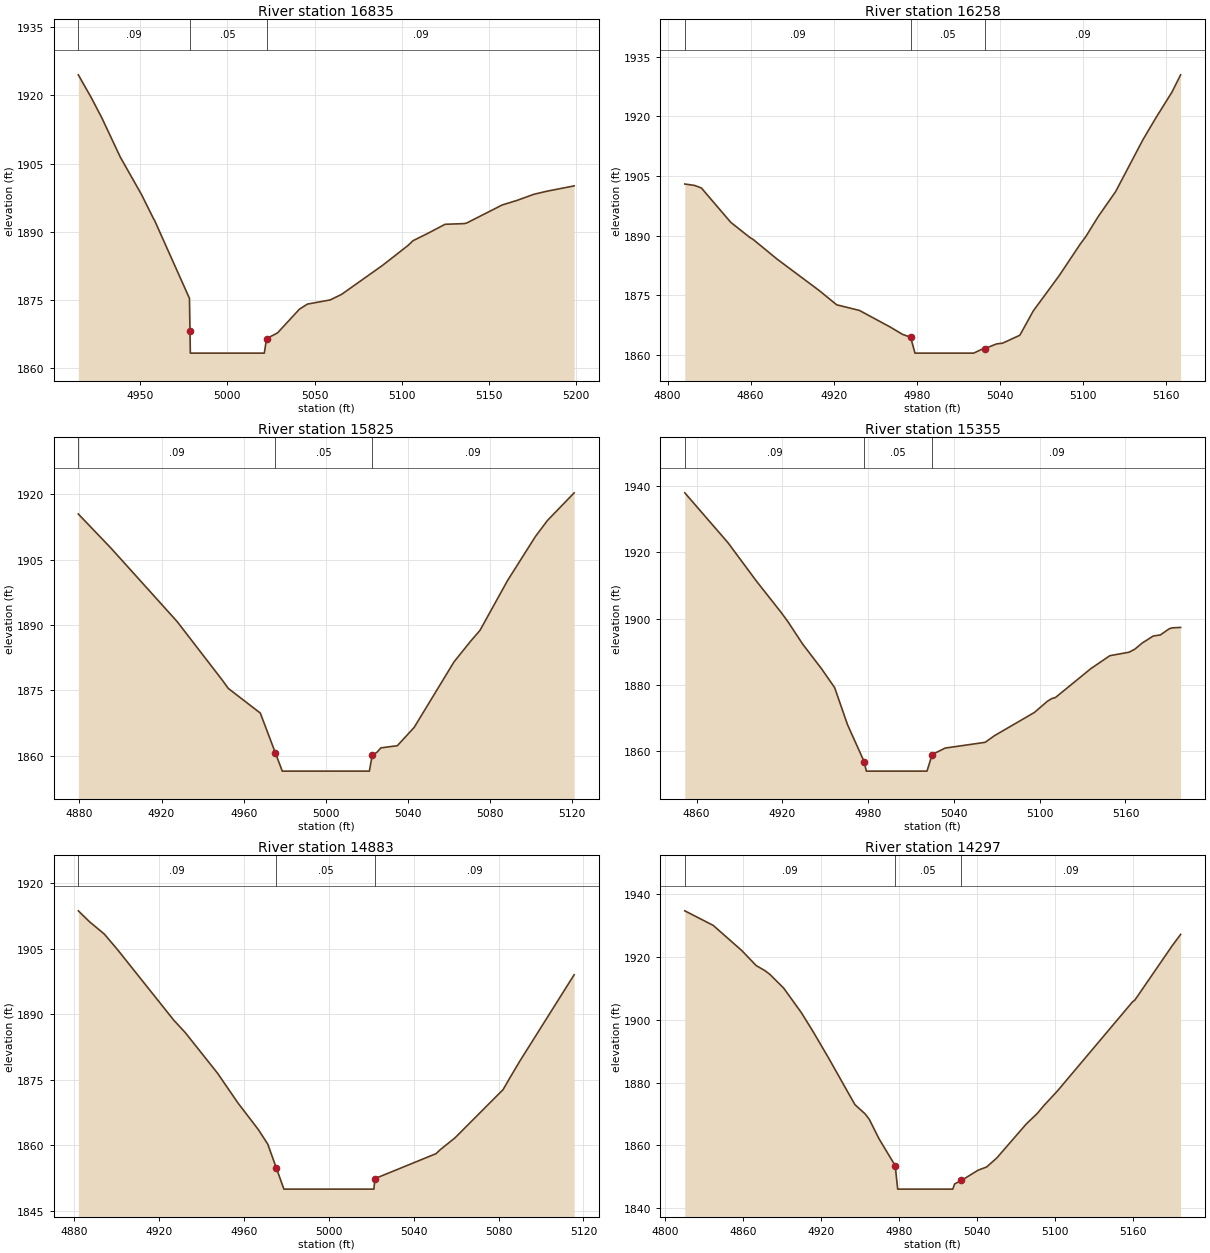
Type RM Length L Ch R = 1 ,16835   ,577,577,577
BEGIN DESCRIPTION:
Turkey_Crk_XS34
END DESCRIPTION:
XS GIS Cut Line= 6
       908545.86       733461.46       908579.73       733407.51
       908588.51       733369.87       908619.88       733277.02
        908624.9       733256.95       908683.87       733234.36
#Sta/Elev= 30
  4914.6 1924.53  4922.1 1919.45    4928 1915.12  4938.6 1906.47  4950.9 1898.13
  4957.9 1892.72  4958.2 1892.59  4978.3 1875.34  4978.61868.103  4978.8 1863.29
  5021.2 1863.29  5022.5 1866.49  5028.3 1867.64  5029.1 1867.87  5041.3 1872.95
  5045.9 1874.08    5059    1875  5065.5 1876.22  5088.9 1882.58  5103.6 1886.99
  5106.4 1888.02    5115 1889.66  5124.8 1891.64  5135.7 1891.79  5137.2 1891.92
  5157.6  1895.9  5165.9 1896.88  5175.7 1898.24  5183.3 1898.93  5198.8 1900.09
#Mann= 3 ,-1 , 0
  4914.6     .09       0  4978.6     .05       0  5022.5     .09       0
Bank Sta=4978.6,5022.5
Exp/Cntr=0.3,0.1

Type RM Length L Ch R = 1 ,16258   ,433,433,433
BEGIN DESCRIPTION:
Turkey_Crk_XS33
END DESCRIPTION:
XS GIS Cut Line= 5
       908974.95       733431.34       909081.59       733369.87
       909159.38       733319.68       909202.04       733289.57
       909277.32       733239.38
#Sta/Elev= 30
  4812.4 1902.98  4819.5 1902.62  4824.4 1901.98  4845.6 1893.36  4859.9 1889.42
  4861.6 1889.11  4878.9 1884.17  4909.5 1876.23  4922.2 1872.63  4938.6 1871.22
  4960.5 1867.12  4969.8  1865.2  4975.6  1864.5  4978.8 1860.49  5021.2 1860.49
  5028.1 1861.61  5029.3 1861.63  5037.8 1862.81  5042.1 1862.99  5054.6 1864.99
  5064.3  1871.1    5083 1879.94  5098.5 1888.02  5102.2 1889.73  5111.4 1894.89
  5123.8 1901.06  5143.5 1914.07  5152.7 1919.48  5164.5 1926.05  5170.8 1930.41
#Mann= 3 ,-1 , 0
  4812.4     .09       0  4975.6     .05       0  5029.3     .09       0
Bank Sta=4975.6,5029.3
Exp/Cntr=0.3,0.1

Type RM Length L Ch R = 1 ,15825   ,470,470,470
BEGIN DESCRIPTION:
Turkey_Crk_XS32
END DESCRIPTION:
XS GIS Cut Line= 6
       908819.37       733544.26       908870.81       733591.94
       908892.14       733623.31       908904.69       733655.93
       908932.29       733699.84       908947.35       733743.75
#Sta/Elev= 23
  4879.5 1915.44  4895.4 1907.61  4927.6 1890.77  4949.7 1877.26  4952.5 1875.43
  4968.1 1869.77  4975.41860.682  4978.8 1856.45  5021.2 1856.45  5022.6 1860.13
  5024.9 1860.78  5026.8 1861.79  5034.7 1862.27  5034.9 1862.33    5043 1866.48
  5062.4 1881.51  5070.4 1886.21  5074.4 1888.38  5075.1 1888.79  5088.5  1900.2
    5102 1910.25  5107.9 1913.96  5120.9  1920.3
#Mann= 3 ,-1 , 0
  4879.5     .09       0  4975.4     .05       0  5022.6     .09       0
Bank Sta=4975.4,5022.6
Exp/Cntr=0.3,0.1

Type RM Length L Ch R = 1 ,15355   ,472,472,472
BEGIN DESCRIPTION:
Turkey_Crk_XS31
END DESCRIPTION:
XS GIS Cut Line= 6
       908358.91       733885.53       908399.06       733859.18
       908447.99       733834.09       908511.98       733827.82
       908627.41       733824.05        908691.4       733825.31
#Sta/Elev= 30
  4851.8 1938.02    4882 1922.95  4902.1 1911.22    4919 1901.97  4924.1 1898.96
  4934.2 1892.32  4947.5  1884.8  4956.6 1879.14  4965.6 1867.94  4977.2 1856.79
  4978.8 1853.88  5021.2 1853.88  5024.8 1858.89  5033.9 1860.85  5061.9 1862.59
  5068.4  1864.6  5096.3 1871.61  5105.4    1875  5108.5 1875.82    5111 1876.12
  5135.9  1884.9  5149.1 1888.78  5162.5 1889.83  5166.6 1890.75  5171.6 1892.57
  5179.5 1894.74  5184.4 1895.05  5190.6 1896.91  5192.6 1897.19  5198.6 1897.33
#Mann= 3 ,-1 , 0
  4851.8     .09       0  4977.2     .05       0  5024.8     .09       0
Bank Sta=4977.2,5024.8
Exp/Cntr=0.3,0.1

Type RM Length L Ch R = 1 ,14883   ,586,586,586
BEGIN DESCRIPTION:
Turkey_Crk_XS30
END DESCRIPTION:
XS GIS Cut Line= 6
       908923.51       734073.73       908913.47       733988.41
       908902.18       733935.72       908894.65        733905.6
       908897.16       733872.98       908898.41       733842.87
#Sta/Elev= 22
  4881.9 1913.69  4887.3 1911.13  4894.1 1908.39  4900.4 1904.78  4926.9 1888.62
  4932.3 1885.78  4947.5 1876.48  4957.2 1869.61  4966.9 1863.45  4967.8 1862.76
  4971.2  1860.2  4975.21854.779  4978.8  1849.9  5021.2  1849.9  5021.7 1852.31
  5050.5 1858.03  5052.7 1859.03  5059.4 1861.64  5082.1 1872.71  5085.4 1875.49
    5090 1879.25  5115.6 1899.04
#Mann= 3 ,-1 , 0
  4881.9     .09       0  4975.2     .05       0  5021.7     .09       0
Bank Sta=4975.2,5021.7
Exp/Cntr=0.3,0.1

Type RM Length L Ch R = 1 ,14297   ,450,450,450
BEGIN DESCRIPTION:
Turkey_Crk_XS29
END DESCRIPTION:
XS GIS Cut Line= 6
       909005.06       734162.81       909071.56       734156.54
        909136.8       734179.12       909261.01       734248.13
       909322.49       734258.16       909357.62       734279.49
#Sta/Elev= 30
    4815 1934.73  4836.8 1930.11  4858.8 1922.09  4869.9  1917.3  4876.6 1915.69
  4880.4 1914.51  4891.1  1910.1  4904.7 1902.27  4913.2 1896.61  4925.9 1887.65
  4945.9 1872.98  4953.8 1870.01    4957 1868.26  4964.5 1862.06  4976.9 1853.54
  4978.8 1846.06  5021.2 1846.06  5022.6 1847.71  5027.8 1848.81  5040.6 1852.08
  5047.2 1853.11    5055 1855.96  5077.8 1866.85  5086.2 1870.17  5091.2 1872.65
  5101.6 1877.28  5159.5 1905.73  5161.2 1906.24    5190  1923.6  5196.5 1927.22
#Mann= 3 ,-1 , 0
    4815     .09       0  4976.9     .05       0  5027.8     .09       0
Bank Sta=4976.9,5027.8
Exp/Cntr=0.3,0.1

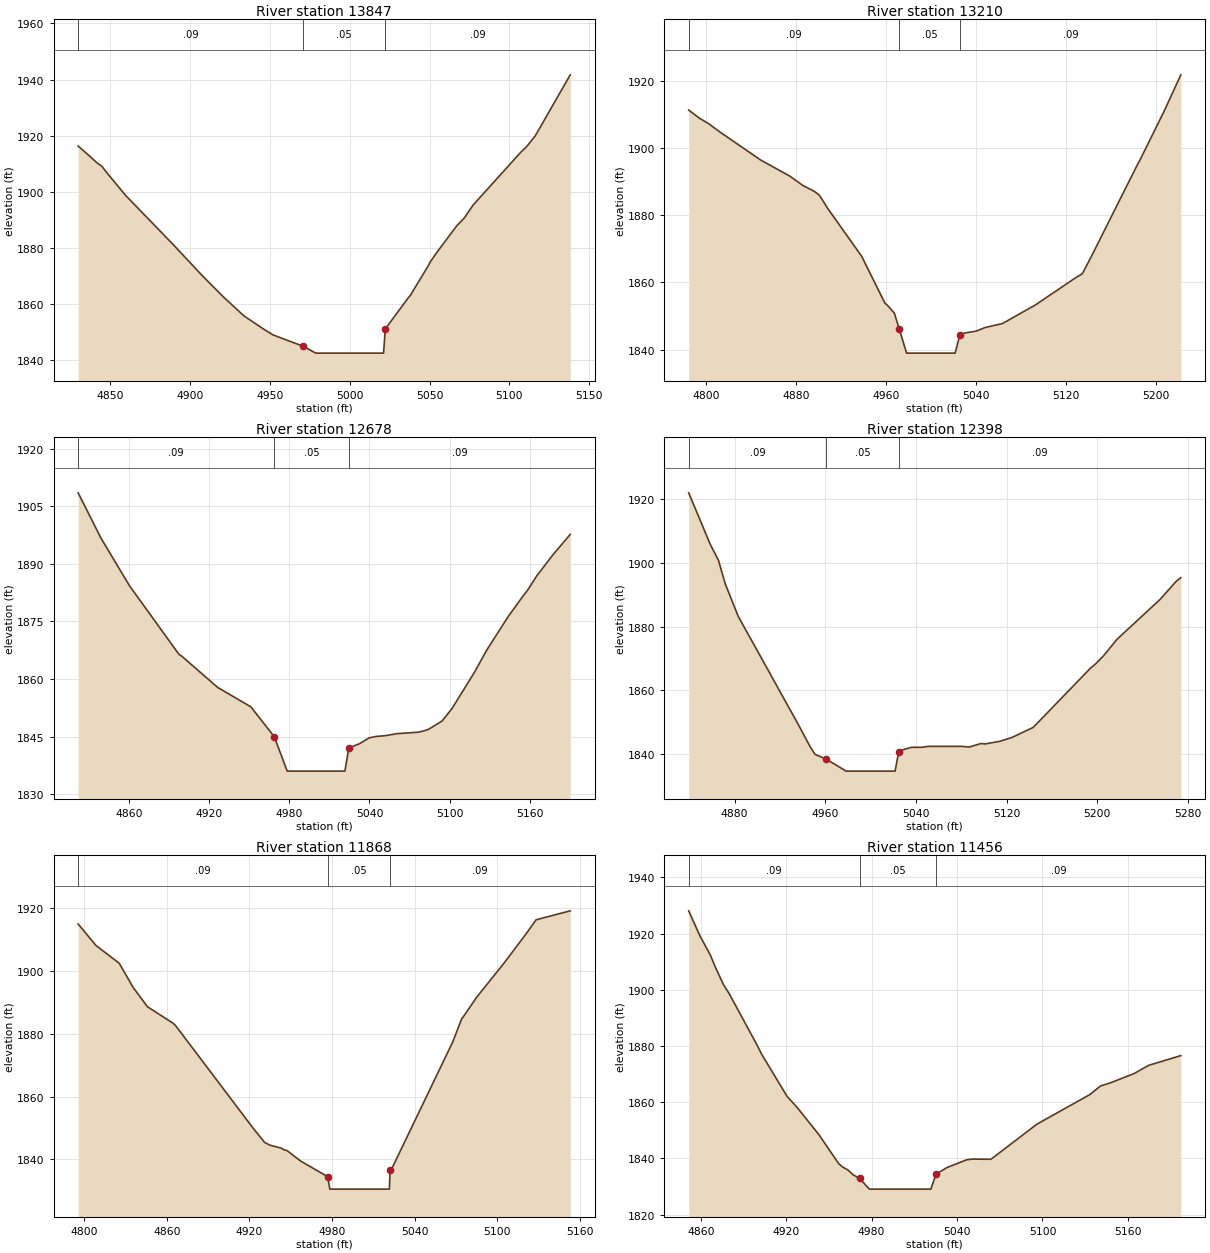
Type RM Length L Ch R = 1 ,13847   ,637,637,637
BEGIN DESCRIPTION:
Turkey_Crk_XS28
END DESCRIPTION:
XS GIS Cut Line= 6
       908843.21       734312.11       908851.99       734420.01
        908854.5       734504.08       908863.28       734545.48
       908875.83       734583.12       908888.38       734614.49
#Sta/Elev= 29
    4830  1916.3  4834.5  1914.1  4841.9 1910.29  4844.9 1909.07  4847.7 1907.01
  4859.7 1898.75  4889.3 1881.36  4907.9 1870.06  4920.9 1862.63  4933.7 1855.88
  4946.2 1851.11  4952.1 1849.04  4970.8 1845.04  4978.8 1842.58  5021.2 1842.58
  5022.3 1851.19  5036.7  1862.3  5038.1  1863.2  5039.1  1864.2  5049.1 1873.58
  5050.6 1875.19    5055 1878.77  5066.9 1887.83  5071.9 1890.81  5077.3 1895.32
  5106.9 1913.97  5111.1 1916.32  5116.2 1919.96  5138.1 1941.67
#Mann= 3 ,-1 , 0
    4830     .09       0  4970.8     .05       0  5022.3     .09       0
Bank Sta=4970.8,5022.3
Exp/Cntr=0.3,0.1

Type RM Length L Ch R = 1 ,13210   ,532,532,532
BEGIN DESCRIPTION:
Turkey_Crk_XS27
END DESCRIPTION:
XS GIS Cut Line= 6
       908180.75       734205.47        908234.7       734347.24
       908223.41       734401.19       908224.66       734494.04
       908237.21       734535.44       908230.94       734628.29
#Sta/Elev= 30
  4784.4 1911.23  4793.8 1908.84  4801.9 1907.24    4812 1904.75  4848.3 1896.41
  4874.8 1891.51  4885.8 1888.85  4896.5    1887  4900.8 1885.88  4908.4 1881.87
  4938.4 1867.74  4959.1 1853.82  4961.3 1853.18  4967.5 1850.83  4971.81846.143
  4978.4 1838.95  5021.6 1838.95  5025.9 1844.48  5030.8 1844.98  5040.1 1845.47
  5048.2 1846.55  5063.7 1847.74  5092.7  1853.2  5129.4 1861.48  5134.8 1862.53
  5142.7 1867.57  5184.4 1895.33    5186 1896.26  5208.1 1911.18  5222.5  1921.7
#Mann= 3 ,-1 , 0
  4784.4     .09       0  4971.8     .05       0  5025.9     .09       0
Bank Sta=4971.8,5025.9
Exp/Cntr=0.3,0.1

Type RM Length L Ch R = 1 ,12678   ,280,280,280
BEGIN DESCRIPTION:
Turkey_Crk_XS26
END DESCRIPTION:
XS GIS Cut Line= 6
        907601.1       734414.99       907672.62       734445.11
       907686.42       734489.02       907735.35        734591.9
       907785.54       734684.75       907805.61        734699.8
#Sta/Elev= 30
  4821.9 1908.46  4839.1 1896.59  4860.5 1884.18  4897.3 1866.43  4899.5 1865.91
  4926.3  1857.8  4951.2 1852.73  4968.7 1844.97  4978.4 1835.99  5021.6 1835.99
  5024.5 1842.02  5032.6 1843.14  5039.7 1844.65  5044.7    1845  5052.3 1845.25
  5060.9 1845.76  5076.3 1846.12  5081.1  1846.5  5084.2 1846.88  5094.4 1849.06
  5101.8  1852.3  5118.7 1861.79  5126.8 1866.91  5128.8 1868.07    5144 1876.32
  5155.9 1882.03  5158.2 1883.02  5165.2 1886.82  5176.8  1892.1  5190.3 1897.64
#Mann= 3 ,-1 , 0
  4821.9     .09       0  4968.7     .05       0  5024.5     .09       0
Bank Sta=4968.7,5024.5
Exp/Cntr=0.3,0.1

Type RM Length L Ch R = 1 ,12398   ,530,530,530
BEGIN DESCRIPTION:
Turkey_Crk_XS25
END DESCRIPTION:
XS GIS Cut Line= 6
       907391.57       734800.17       907422.94       734777.59
        907479.4       734718.62       907537.11       734688.51
       907623.68       734667.18        907775.5       734716.11
#Sta/Elev= 30
  4839.4 1921.86  4858.4 1905.77  4865.7 1900.73  4871.7 1893.34  4883.2 1883.15
    4936 1849.44  4946.6  1842.4  4950.9    1840  4960.8 1838.52  4978.4 1834.75
  5021.6 1834.75  5024.8 1840.87  5027.9 1841.38    5036  1842.2  5045.7 1842.22
  5050.9 1842.51  5079.9 1842.51    5087 1842.29  5097.4 1843.39    5101 1843.26
  5113.9 1844.07  5124.8 1845.29  5143.5 1848.43  5194.2 1867.02  5198.1 1868.15
  5205.3 1870.73  5217.5 1876.02  5255.8 1888.59  5269.5 1894.08  5273.8 1895.31
#Mann= 3 ,-1 , 0
  4839.4     .09       0  4960.8     .05       0  5024.8     .09       0
Bank Sta=4960.8,5024.8
Exp/Cntr=0.3,0.1

Type RM Length L Ch R = 1 ,11868   ,412,412,412
BEGIN DESCRIPTION:
Turkey_Crk_XS24
END DESCRIPTION:
XS GIS Cut Line= 6
       907510.77       735014.72       907652.54       735074.94
       907703.98       735116.35       907759.19       735138.93
       907804.36       735140.19       907834.47       735151.48
#Sta/Elev= 27
  4795.7 1915.03  4808.7 1908.15  4825.5 1902.52  4835.6 1894.82    4846 1888.65
  4864.8 1883.34  4866.6 1882.54  4922.6    1850    4931 1845.41  4934.9 1844.52
    4943  1843.6  4945.1 1843.04  4947.2 1842.82  4957.2 1839.46  4976.8 1834.49
  4978.4 1830.51  5021.6 1830.51  5022.1 1836.75  5023.3 1836.97  5067.6 1877.43
  5074.2 1884.92  5074.8 1885.14    5085  1891.7  5104.7 1902.48  5120.8 1911.86
  5128.1 1916.36  5152.9 1919.22
#Mann= 3 ,-1 , 0
  4795.7     .09       0  4976.8     .05       0  5022.1     .09       0
Bank Sta=4976.8,5022.1
Exp/Cntr=0.3,0.1

Type RM Length L Ch R = 1 ,11456   ,374,374,374
BEGIN DESCRIPTION:
Turkey_Crk_XS23
END DESCRIPTION:
XS GIS Cut Line= 6
       907368.99       735490.23       907461.83       735424.99
       907529.59       735367.28       907578.52       735343.44
       907608.63        735319.6       907655.05       735300.78
#Sta/Elev= 30
  4851.5 1928.09  4859.6 1918.97  4866.6 1912.47    4870 1908.31  4875.9 1901.86
  4880.3  1898.3  4899.2 1880.62  4902.9 1876.93  4920.5 1862.15  4927.8 1858.04
    4943 1848.43  4956.8 1838.17  4959.5 1836.95  4963.3 1835.89  4967.1 1834.13
  4971.6 1832.84  4978.4 1829.05  5021.6 1829.05  5025.2 1834.31  5032.7 1836.67
  5046.8 1839.49  5050.7 1839.74  5063.8 1839.67  5096.2 1852.19  5133.3  1862.7
  5140.8 1865.78  5147.1 1866.75  5164.5  1870.2  5174.6  1873.1  5197.2 1876.57
#Mann= 3 ,-1 , 0
  4851.5     .09       0  4971.6     .05       0  5025.2     .09       0
Bank Sta=4971.6,5025.2
Exp/Cntr=0.3,0.1

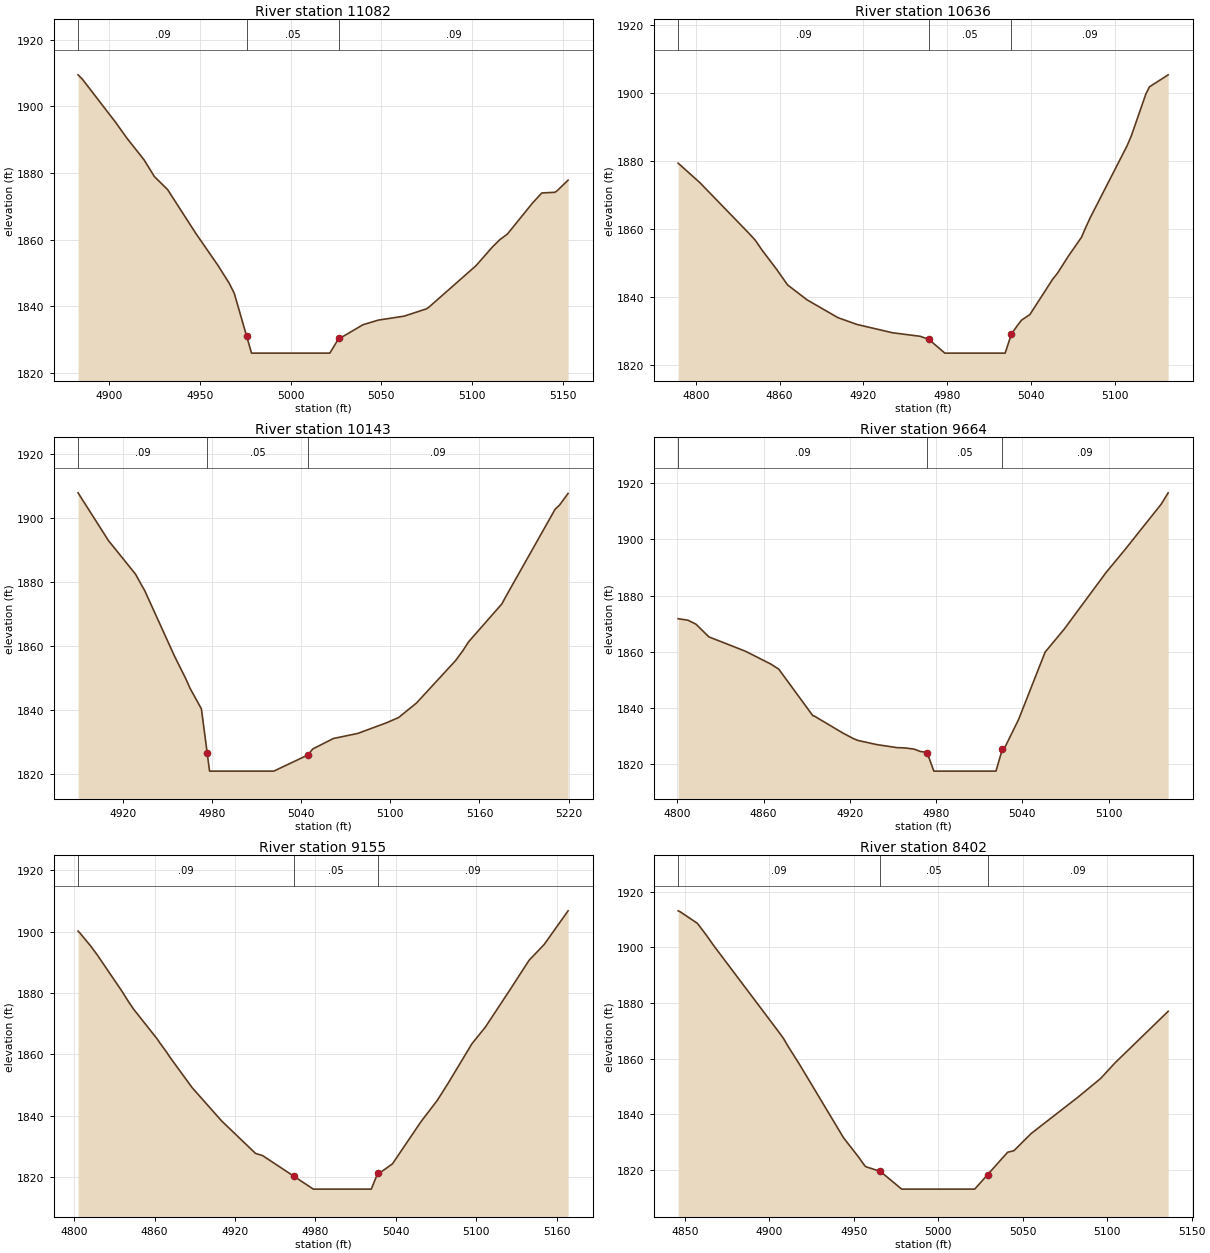
Type RM Length L Ch R = 1 ,11082   ,446,446,446
BEGIN DESCRIPTION:
Turkey_Crk_XS22
END DESCRIPTION:
XS GIS Cut Line= 6
       907829.45       735546.69       907840.74       735516.58
       907845.76       735473.92       907843.25        735441.3
       907808.12       735374.81       907778.01       735293.25
#Sta/Elev= 30
  4882.7 1909.43  4885.1 1908.12  4903.4 1895.19  4909.6 1890.46  4919.1 1883.93
  4924.8  1878.9  4932.1 1874.99  4947.6 1861.89  4959.9 1852.22  4966.1 1846.86
  4968.9 1843.81 4975.751830.896  4978.4  1825.9  5021.6  1825.9  5026.5 1830.32
    5029 1830.95  5039.9 1834.43  5048.4 1835.82  5062.5 1836.99  5074.8 1839.17
  5076.3 1839.72  5102.2 1852.14  5111.4 1857.84  5115.3 1859.92  5119.5 1861.62
  5133.3 1870.89  5138.5 1873.97  5145.7 1874.17  5146.9 1874.61    5153 1877.81
#Mann= 3 ,-1 , 0
  4882.7     .09       0 4975.75     .05       0  5026.5     .09       0
Bank Sta=4975.75,5026.5
Exp/Cntr=0.3,0.1

Type RM Length L Ch R = 1 ,10636   ,493,493,493
BEGIN DESCRIPTION:
Turkey_Crk_XS21
END DESCRIPTION:
XS GIS Cut Line= 6
       908208.35       735467.65       908215.88       735394.88
        908248.5        735278.2       908251.01       735229.27
       908272.34       735177.83       908286.14       735127.64
#Sta/Elev= 30
  4787.3 1879.35  4802.8 1873.66  4838.1 1858.72  4842.6 1856.69  4847.4 1853.82
  4857.8  1848.2  4865.7 1843.59  4879.7 1839.19  4901.8 1833.97  4915.4 1831.98
  4940.9 1829.53  4960.6  1828.5  4966.7 1827.66  4978.4 1823.55  5021.6 1823.55
  5026.1 1829.18  5030.6  1831.8  5033.4 1833.26  5039.3 1834.87  5055.6 1845.24
  5059.2 1847.09    5067 1852.11  5076.3 1857.59  5078.9 1860.08  5082.7 1863.45
  5108.9 1884.41    5112 1887.38  5122.4 1899.65    5125 1901.78  5138.4  1905.3
#Mann= 3 ,-1 , 0
  4787.3     .09       0  4966.7     .05       0  5026.1     .09       0
Bank Sta=4966.7,5026.1
Exp/Cntr=0.3,0.1

Type RM Length L Ch R = 1 ,10143   ,479,479,479
BEGIN DESCRIPTION:
Turkey_Crk_XS20
END DESCRIPTION:
XS GIS Cut Line= 6
       908473.09        735709.8       908525.78       735634.52
       908535.82       735600.64       908555.89       735522.86
       908560.91       735442.56       908565.93       735401.15
#Sta/Elev= 30
  4889.9 1907.93  4910.7 1892.78  4912.2 1891.97  4928.6 1882.52    4933 1878.82
  4934.7 1877.46    4955 1856.75  4962.3 1849.98  4965.3 1846.87  4972.9 1840.48
  4976.81826.696  4978.4 1821.04  5021.6 1821.04  5044.4 1826.05  5047.9 1827.98
  5061.7 1831.23  5078.1 1832.81  5097.4 1836.13  5105.5 1837.75  5117.6  1842.3
  5143.9 1855.55  5147.8    1858  5148.6 1858.51  5152.7 1861.43  5175.1 1873.28
  5177.5 1875.35  5177.9 1875.69  5210.9 1902.82  5213.8 1904.09  5219.6 1907.74
#Mann= 3 ,-1 , 0
  4889.9     .09       0  4976.8     .05       0  5044.4     .09       0
Bank Sta=4976.8,5044.4
Exp/Cntr=0.3,0.1

Type RM Length L Ch R = 1 ,9664    ,509,509,509
BEGIN DESCRIPTION:
Turkey_Crk_XS19
END DESCRIPTION:
XS GIS Cut Line= 6
        908746.6       735754.97       908794.28        735751.2
       908919.74       735749.95       908964.91       735752.46
       909017.61       735756.22        909084.1        735776.3
#Sta/Elev= 30
  4800.5 1871.75  4807.3 1871.22  4812.9  1869.8  4821.9 1865.27  4847.3 1860.16
    4865 1855.58  4870.5 1853.77  4894.2 1837.18  4895.4    1837  4915.3 1830.94
  4922.6 1828.98  4925.8 1828.33  4938.9 1826.86  4952.9 1825.79  4958.3 1825.69
  4964.7 1825.26    4969 1824.42  4972.2 1824.22  4973.8 1823.88  4978.4 1817.42
  5021.6 1817.42    5026 1825.17  5028.1  1826.2  5037.4  1835.9  5055.8 1859.85
  5068.9 1867.92  5098.1 1888.16  5111.6 1896.53  5136.6 1912.62  5141.4 1916.62
#Mann= 3 ,-1 , 0
  4800.5     .09       0  4973.8     .05       0    5026     .09       0
Bank Sta=4973.8,5026
Exp/Cntr=0.3,0.1

Type RM Length L Ch R = 1 ,9155    ,753,753,753
BEGIN DESCRIPTION:
Turkey_Crk_XS18
END DESCRIPTION:
XS GIS Cut Line= 6
       908414.12       735857.85       908456.78       735921.84
       908498.18       735960.73       908519.51       735999.63
       908559.66       736083.69       908577.22       736175.28
#Sta/Elev= 30
  4802.9 1900.14  4804.3 1899.54  4812.4 1895.24  4817.2 1892.42  4835.7 1880.52
  4840.6 1877.12  4844.2  1874.8  4862.2 1864.87  4863.9 1863.74  4868.9 1860.76
  4870.7 1859.53    4888 1849.16    4910 1838.32  4935.3 1827.74  4940.6 1827.03
  4963.71820.357  4978.4 1816.11  5021.6 1816.11  5026.6 1821.46  5029.2 1821.78
  5037.4 1824.34  5058.8 1838.15  5070.8 1844.99  5078.7 1850.43  5096.7 1863.47
  5106.7 1868.88  5124.5 1880.65  5139.3 1890.64  5150.5 1895.75  5168.4 1906.75
#Mann= 3 ,-1 , 0
  4802.9     .09       0  4963.7     .05       0  5026.6     .09       0
Bank Sta=4963.7,5026.6
Exp/Cntr=0.3,0.1

Type RM Length L Ch R = 1 ,8402    ,574,574,574
BEGIN DESCRIPTION:
Turkey_Crk_XS17
END DESCRIPTION:
XS GIS Cut Line= 6
       907804.36       736260.59       907849.52       736310.78
       907879.63       736353.44       907917.27        736382.3
       907976.24       736422.44       908015.14       736456.32
#Sta/Elev= 26
  4846.1  1913.2  4847.4 1912.83  4857.5 1908.69  4862.8 1904.45  4866.8 1900.97
  4905.8 1869.45  4908.5 1867.18  4911.1 1864.47  4913.6 1862.05  4917.9 1857.92
    4944 1831.44  4952.7 1824.66  4956.6 1821.35  4957.2 1821.04  4965.8 1819.32
  4978.4 1812.96  5021.6 1812.96  5029.31818.208  5041.1 1826.25  5044.8  1826.8
  5055.1 1833.02  5082.2 1845.84  5084.6 1847.02  5096.2 1852.86  5104.6 1858.41
  5136.1 1877.01
#Mann= 3 ,-1 , 0
  4846.1     .09       0  4965.8     .05       0  5029.3     .09       0
Bank Sta=4965.8,5029.3
Exp/Cntr=0.3,0.1

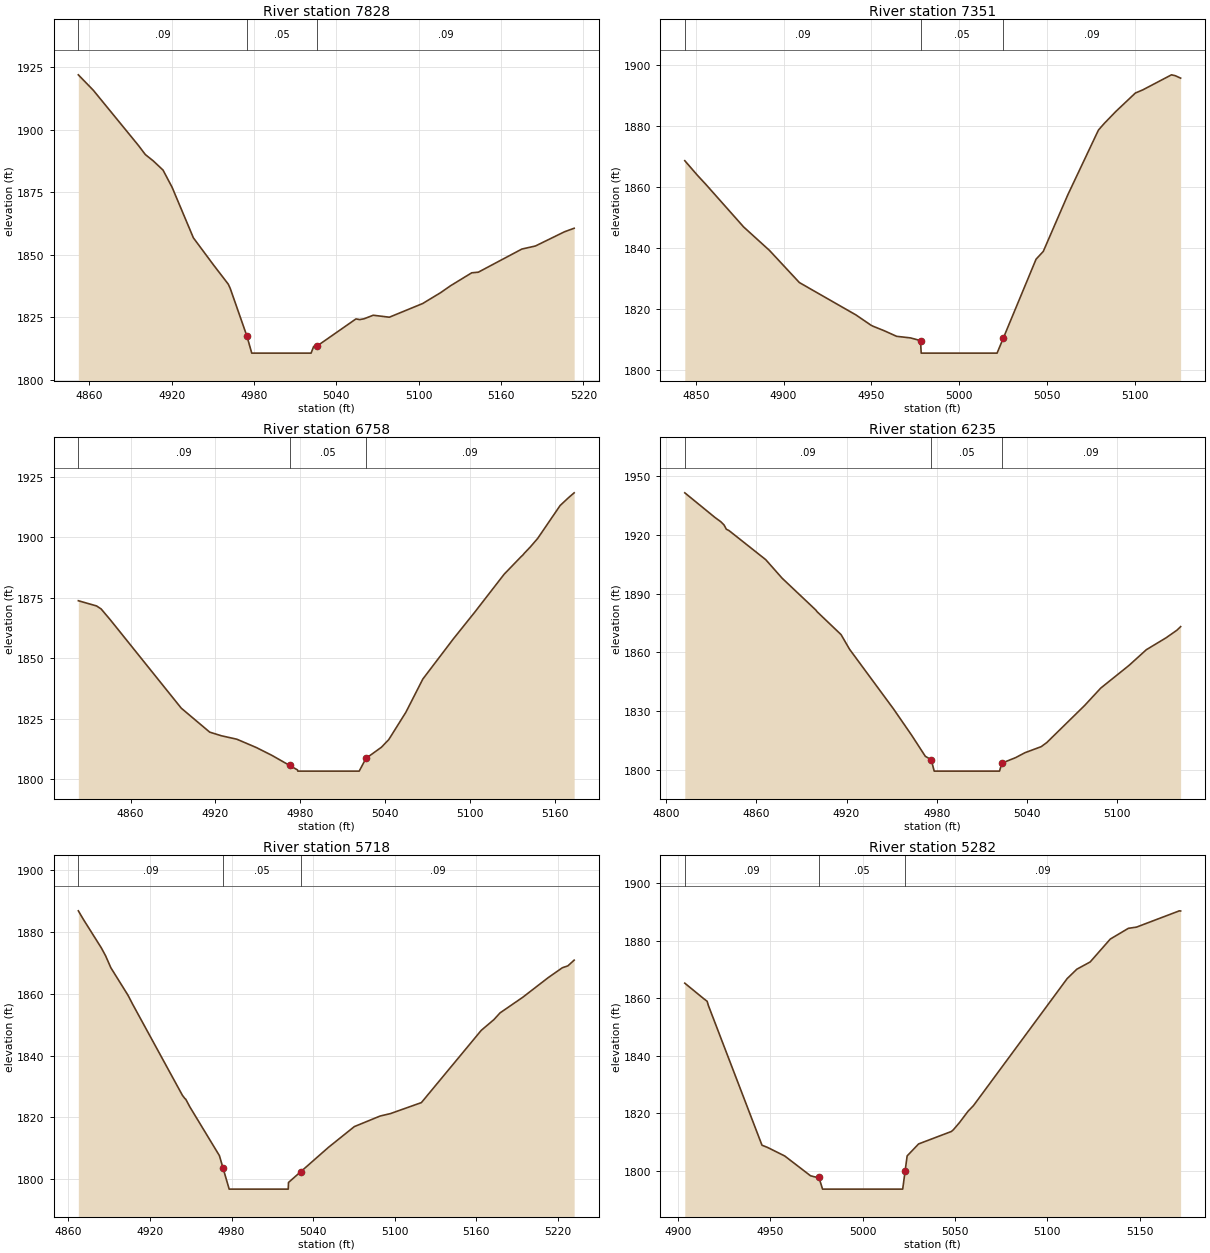
Type RM Length L Ch R = 1 ,7828    ,477,477,477
BEGIN DESCRIPTION:
Turkey_Crk_XS16
END DESCRIPTION:
XS GIS Cut Line= 6
       907549.66       736944.38       907586.04       736854.05
        907642.5       736807.62       907672.62        736761.2
        907722.8       736718.54       907783.03       736685.92
#Sta/Elev= 30
  4852.1 1921.91  4863.1 1915.68    4896 1893.57  4900.9 1890.01  4906.6 1887.51
  4913.8 1883.79  4920.4 1876.91  4935.9 1856.69  4950.4 1845.96  4961.3 1838.16
  4962.7  1836.5  4974.9 1817.34  4978.4 1810.57  5021.6 1810.57  5023.5 1813.23
  5025.9 1813.38  5054.3 1824.26    5057 1823.99  5060.2 1824.31  5066.9 1825.73
  5078.6 1824.94  5102.9 1830.42    5116 1834.78  5123.3 1837.57  5138.6  1842.7
  5143.4 1842.95  5175.1  1852.2    5185 1853.43  5206.2 1859.13  5213.2 1860.53
#Mann= 3 ,-1 , 0
  4852.1     .09       0  4974.9     .05       0  5025.9     .09       0
Bank Sta=4974.9,5025.9
Exp/Cntr=0.3,0.1

Type RM Length L Ch R = 1 ,7351    ,593,593,593
BEGIN DESCRIPTION:
Turkey_Crk_XS15
END DESCRIPTION:
XS GIS Cut Line= 6
       908023.92       736851.54       908025.17       736780.02
       907987.53       736688.43       907967.46        736667.1
       907967.46       736631.97       907947.39       736589.31
#Sta/Elev= 30
  4843.8 1868.62  4850.9 1863.89  4855.8 1860.85  4877.3  1846.9    4892 1839.22
    4909  1828.7  4915.3 1826.61  4941.3 1818.05  4949.9 1814.67  4951.2 1814.31
  4957.3  1812.9  4964.4 1811.06  4972.3 1810.54  4976.1 1809.95    4978  1809.5
  4978.4 1805.55  5021.6 1805.55  5025.11810.404  5043.8 1836.34  5047.9 1838.88
  5061.9 1857.47  5078.9 1878.16  5079.4 1878.72  5082.7 1880.88  5089.2 1884.74
  5100.3 1890.78  5104.7 1891.87  5120.9 1896.76    5123 1896.48  5126.1 1895.68
#Mann= 3 ,-1 , 0
  4843.8     .09       0    4978     .05       0  5025.1     .09       0
Bank Sta=4978,5025.1
Exp/Cntr=0.3,0.1

Type RM Length L Ch R = 1 ,6758    ,523,523,523
BEGIN DESCRIPTION:
Turkey_Crk_XS14
END DESCRIPTION:
XS GIS Cut Line= 6
       908251.01       736889.18       908346.37       736885.41
       908400.32       736884.16       908454.27       736885.41
       908518.25       736892.94       908598.55       736913.01
#Sta/Elev= 30
  4823.1 1873.76    4836  1871.6  4839.2 1870.37  4845.7 1865.88  4895.9 1829.33
    4916 1819.43  4924.2 1817.94  4935.2  1816.5  4949.1 1813.03  4960.1 1809.79
  4972.5 1805.66  4978.1  1803.8  4978.3 1803.31  5021.7 1803.31  5026.5 1808.58
  5037.4 1813.18  5042.6 1816.34  5054.7 1827.64  5066.7 1841.38  5088.3    1858
  5103.4 1869.02  5124.2 1884.72  5136.4 1892.11  5137.2  1892.5  5138.5 1893.41
  5142.8 1896.06  5147.9 1899.51  5163.8 1913.14  5169.6  1916.3  5173.7 1918.37
#Mann= 3 ,-1 , 0
  4823.1     .09       0  4972.5     .05       0  5026.5     .09       0
Bank Sta=4972.5,5026.5
Exp/Cntr=0.3,0.1

Type RM Length L Ch R = 1 ,6235    ,517,517,517
BEGIN DESCRIPTION:
Turkey_Crk_XS13
END DESCRIPTION:
XS GIS Cut Line= 6
       907969.97       737166.45       907993.81       737167.71
       908059.05        737206.6       908102.96       737253.03
       908173.22       737340.85       908197.06       737388.53
#Sta/Elev= 30
  4812.5 1941.55  4832.7 1928.86  4836.4  1926.8  4838.6 1925.11  4840.1 1922.94
  4841.9 1922.24  4866.3 1907.37  4877.2 1897.89  4899.6 1881.61  4900.5  1880.7
  4916.4 1869.02    4922 1861.58  4951.2 1831.08  4963.2 1817.69  4972.4  1806.8
  4976.3 1805.08  4978.3 1799.22  5021.7 1799.22  5023.3 1803.31  5032.4 1806.12
  5038.6 1808.63  5049.4 1811.73  5053.1 1813.81  5078.3  1832.8    5089 1841.68
  5107.8 1853.29  5119.3 1861.31  5132.4 1867.39  5139.7 1871.33  5142.1 1873.11
#Mann= 3 ,-1 , 0
  4812.5     .09       0  4976.3     .05       0  5023.3     .09       0
Bank Sta=4976.3,5023.3
Exp/Cntr=0.3,0.1

Type RM Length L Ch R = 1 ,5718    ,436,436,436
BEGIN DESCRIPTION:
Turkey_Crk_XS12
END DESCRIPTION:
XS GIS Cut Line= 6
       907703.98       737717.25       907762.95       737673.34
       907836.98       737645.73       907948.64       737588.02
       907987.53       737559.16       908023.92       737549.12
#Sta/Elev= 30
  4867.4  1886.8  4871.1 1884.04  4884.3 1874.82  4887.4  1872.3  4891.3  1868.4
    4904 1859.44  4907.3 1856.62  4943.9 1827.16  4945.8 1826.05  4946.3 1825.94
  4949.4 1823.39  4971.1 1807.65  4973.71803.735  4978.3 1796.81  5021.7 1796.81
  5021.9 1798.96    50311802.479  5051.2 1810.29  5070.3 1817.03  5089.3 1820.45
  5096.9 1821.24  5119.6 1824.79  5163.6 1848.15  5172.9 1851.62  5177.4 1853.79
  5194.1 1858.84  5212.8 1865.19  5223.2 1868.39  5227.3 1869.01  5231.9 1870.85
#Mann= 3 ,-1 , 0
  4867.4     .09       0  4973.7     .05       0    5031     .09       0
Bank Sta=4973.7,5031
Exp/Cntr=0.3,0.1

Type RM Length L Ch R = 1 ,5282    ,479,479,479
BEGIN DESCRIPTION:
Turkey_Crk_XS11
END DESCRIPTION:
XS GIS Cut Line= 6
       908203.34       737753.63       908212.12       737709.72
       908203.34       737678.35       908160.68       737626.91
       908161.93       737564.18       908121.78       737517.76
#Sta/Elev= 30
  4903.7 1865.23  4913.8 1859.91  4915.8 1858.92  4916.5 1857.42  4945.5 1808.85
  4948.5 1808.08  4957.8 1805.11  4971.8 1798.21  4974.3  1797.8  4976.3 1797.71
  4978.3 1793.57  5021.7 1793.57    50231799.826  5024.1 1805.12  5030.3 1809.29
  5048.1 1813.64  5049.2 1814.27  5052.5 1816.76  5057.1 1820.68    5060 1822.61
  5110.8 1866.86  5111.4 1867.22    5116 1870.09  5123.2  1872.6  5134.1 1880.57
  5143.9 1884.31  5148.3 1884.73  5171.2 1890.32  5171.4  1890.4  5172.2 1890.34
#Mann= 3 ,-1 , 0
  4903.7     .09       0  4976.3     .05       0    5023     .09       0
Bank Sta=4976.3,5023
Exp/Cntr=0.3,0.1

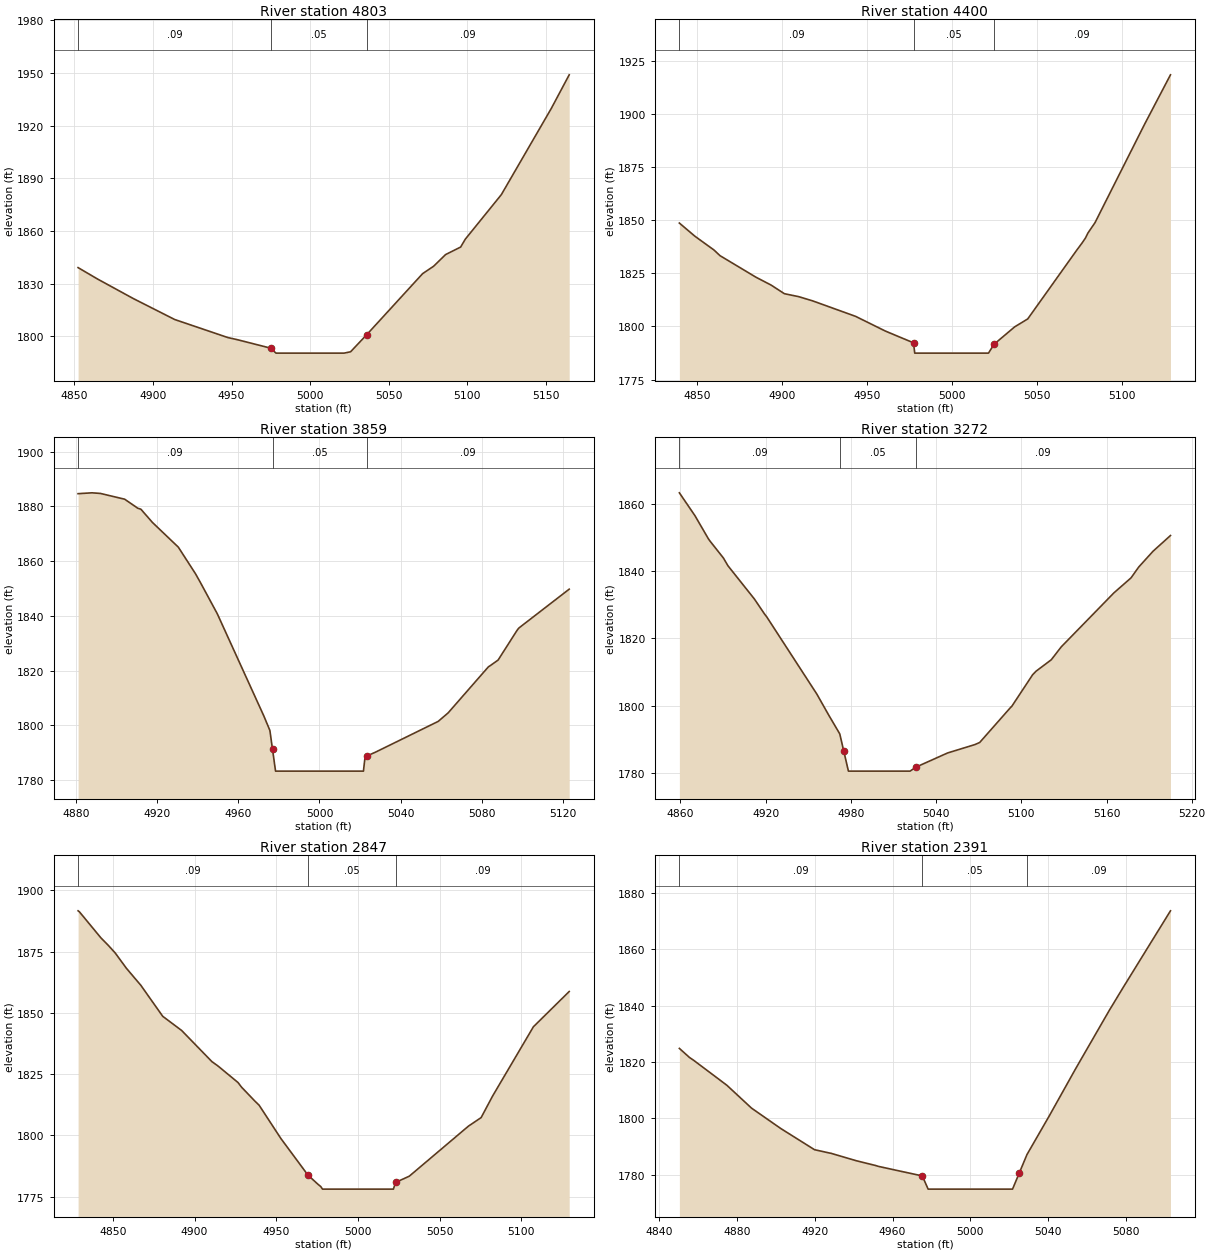
Type RM Length L Ch R = 1 ,4803    ,403,403,403
BEGIN DESCRIPTION:
Turkey_Crk_XS10
END DESCRIPTION:
XS GIS Cut Line= 6
       908599.81       737653.26       908633.68       737549.12
       908642.47       737491.41       908656.27       737443.73
       908668.81       737416.13       908702.69       737360.93
#Sta/Elev= 22
  4852.3 1839.15  4864.8 1832.59  4887.5  1821.5  4913.8 1809.58  4947.7 1799.28
  4953.3 1798.17  4961.9 1796.22  4974.9 1793.25  4978.3 1790.42  5021.7 1790.42
  5025.8 1791.19    5036 1800.85  5069.9 1833.99  5071.7 1835.74  5078.7 1839.96
  5086.3 1846.59  5095.9 1850.89  5098.8 1855.31  5100.2 1856.87  5121.8 1880.75
  5153.6 1929.86    5165 1949.02
#Mann= 3 ,-1 , 0
  4852.3     .09       0  4974.9     .05       0    5036     .09       0
Bank Sta=4974.9,5036
Exp/Cntr=0.3,0.1

Type RM Length L Ch R = 1 ,4400    ,541,541,541
BEGIN DESCRIPTION:
Turkey_Crk_XS9
END DESCRIPTION:
XS GIS Cut Line= 6
       908612.35       737702.19        908677.6       737728.54
       908727.78       737778.73       908741.58       737816.37
       908781.73       737850.24       908829.41       737877.84
#Sta/Elev= 24
  4839.8 1848.75    4849 1842.51  4860.2 1836.03  4863.7 1833.39  4884.8 1823.26
  4893.8 1819.51  4901.6 1815.46  4910.1 1814.05  4918.3 1812.06  4943.5 1804.78
  4961.1 1797.82  4977.6  1792.3  4978.3 1787.45  5021.7 1787.45    5025 1791.64
  5037.1 1799.82  5044.8 1803.57  5073.7 1836.04  5076.8 1839.38  5078.8 1841.74
  5080.2 1844.03  5084.4 1848.95  5113.4 1895.07  5128.8 1918.61
#Mann= 3 ,-1 , 0
  4839.8     .09       0  4977.6     .05       0    5025     .09       0
Bank Sta=4977.6,5025
Exp/Cntr=0.3,0.1

Type RM Length L Ch R = 1 ,3859    ,587,587,587
BEGIN DESCRIPTION:
Turkey_Crk_XS8
END DESCRIPTION:
XS GIS Cut Line= 6
       908158.17       737815.11       908189.53       737866.55
       908204.59       737894.16       908217.14       737944.34
       908243.48       737998.29       908271.09       738025.89
#Sta/Elev= 30
  4880.8 1884.68  4887.7 1884.99  4891.8 1884.77  4903.8 1882.66  4910.3 1879.35
  4911.8 1879.01  4917.5 1874.17  4930.3 1865.13  4938.8 1855.38  4941.1 1852.34
  4949.5 1840.84  4972.5 1803.47  4975.5 1798.15  4976.81791.247  4978.3 1783.28
  5021.7 1783.28  5022.5 1788.48  5023.3 1788.79  5024.2 1789.08  5027.7 1790.23
  5058.6 1801.45  5063.5 1804.55  5083.4  1821.4  5084.3 1821.82  5088.2 1823.88
  5097.5 1834.67  5098.2 1835.36  5098.5  1835.6    5099  1835.9  5123.3 1849.78
#Mann= 3 ,-1 , 0
  4880.8     .09       0  4976.8     .05       0  5023.3     .09       0
Bank Sta=4976.8,5023.3
Exp/Cntr=0.3,0.1

Type RM Length L Ch R = 1 ,3272    ,425,425,425
BEGIN DESCRIPTION:
Turkey_Crk_XS7
END DESCRIPTION:
XS GIS Cut Line= 6
       907562.21       738146.34       907666.34       738160.14
       907735.35       738160.14        907816.9       738153.87
       907863.32       738145.09       907904.73       738135.05
#Sta/Elev= 30
  4859.3 1863.23  4870.3 1856.43  4879.7  1849.6  4880.7    1849  4890.3 1843.88
  4893.5 1841.58  4912.1 1831.72  4919.1 1827.35  4920.8 1826.41  4956.1 1803.47
  4964.3 1797.35  4972.2 1791.68    49751786.603  4978.3 1780.62  5021.7 1780.62
  5025.7 1781.78  5048.1 1786.01  5067.4 1788.51  5070.7 1789.12  5092.8 1799.69
  5093.1 1799.73    5108 1809.25  5110.4 1810.29  5121.1 1813.68  5128.1  1817.5
  5165.2 1833.54  5177.2 1837.97  5182.7 1841.23  5192.7 1845.88    5205 1850.56
#Mann= 3 ,-1 , 0
  4859.3     .09       0  4972.2     .05       0  5025.7     .09       0
Bank Sta=4975,5025.7
Exp/Cntr=0.3,0.1

Type RM Length L Ch R = 1 ,2847    ,456,456,456
BEGIN DESCRIPTION:
Turkey_Crk_XS6
END DESCRIPTION:
XS GIS Cut Line= 6
       908052.78       738460.01       908059.05       738422.37
       908041.48       738378.45       908051.52       738316.97
       908025.17        738230.4       908025.17       738170.18
#Sta/Elev= 28
  4828.7 1891.63  4829.5 1891.23  4842.7 1880.57    4847 1877.66  4851.4 1874.44
  4858.3 1868.15  4867.1 1861.23  4880.5 1848.57  4892.1 1842.77  4910.6 1830.07
  4914.4 1828.24  4926.6 1821.53  4928.7 1819.67    4937 1813.89  4939.5 1812.28
  4952.8  1798.7  4969.4 1783.73  4975.5    1780  4977.2 1779.09  4978.3 1778.01
  5021.7 1778.01    5023 1780.74  5031.4 1783.28  5067.6 1803.71  5075.4 1807.22
  5082.4    1816  5107.4  1844.3  5129.3 1858.69
#Mann= 3 ,-1 , 0
  4828.7     .09       0  4969.4     .05       0    5023     .09       0
Bank Sta=4969.4,5023
Exp/Cntr=0.3,0.1

Type RM Length L Ch R = 1 ,2391    ,492,492,492
BEGIN DESCRIPTION:
Turkey_Crk_XS5
END DESCRIPTION:
XS GIS Cut Line= 6
       908460.54       738330.78       908471.83       738251.73
       908481.87       738207.82       908484.38       738142.58
        908489.4       738104.94       908494.42        738081.1
#Sta/Elev= 25
  4850.4 1824.81  4855.6 1821.59  4857.6 1820.66  4874.8 1811.74  4887.5 1803.61
  4902.5 1796.39  4919.9 1788.85  4927.9 1787.63  4928.3 1787.59  4930.2  1787.2
  4941.4 1784.93  4951.2 1783.26  4952.7 1782.94  4965.7 1780.98    4966 1780.94
  4975.3 1779.55  4978.3 1774.86  5021.7 1774.86  5025.11780.484  5029.1  1787.1
  5040.6 1800.88  5054.2 1817.67  5071.3 1838.14  5078.5 1846.35  5102.9 1873.64
#Mann= 3 ,-1 , 0
  4850.4     .09       0  4975.3     .05       0  5029.1     .09       0
Bank Sta=4975.3,5025.1
Exp/Cntr=0.3,0.1