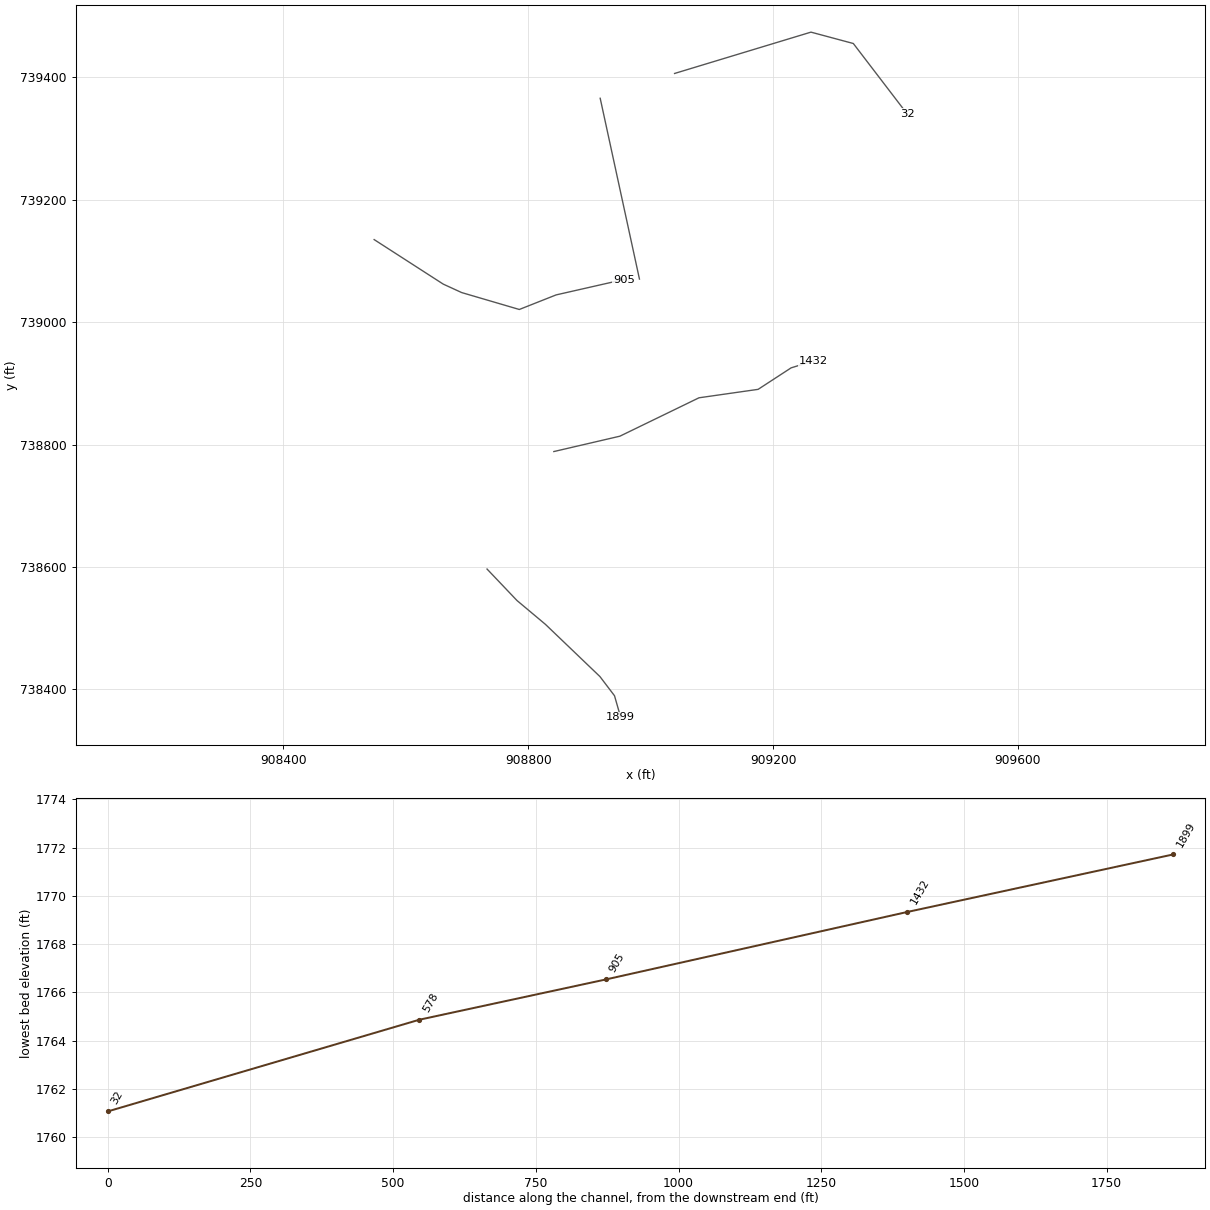
HEC-RAS study lds_turkey_crk.prj: Turkey Creek Limited Detail Study

--- lds_turkey_crk.g01 (geometry) --- (continued)

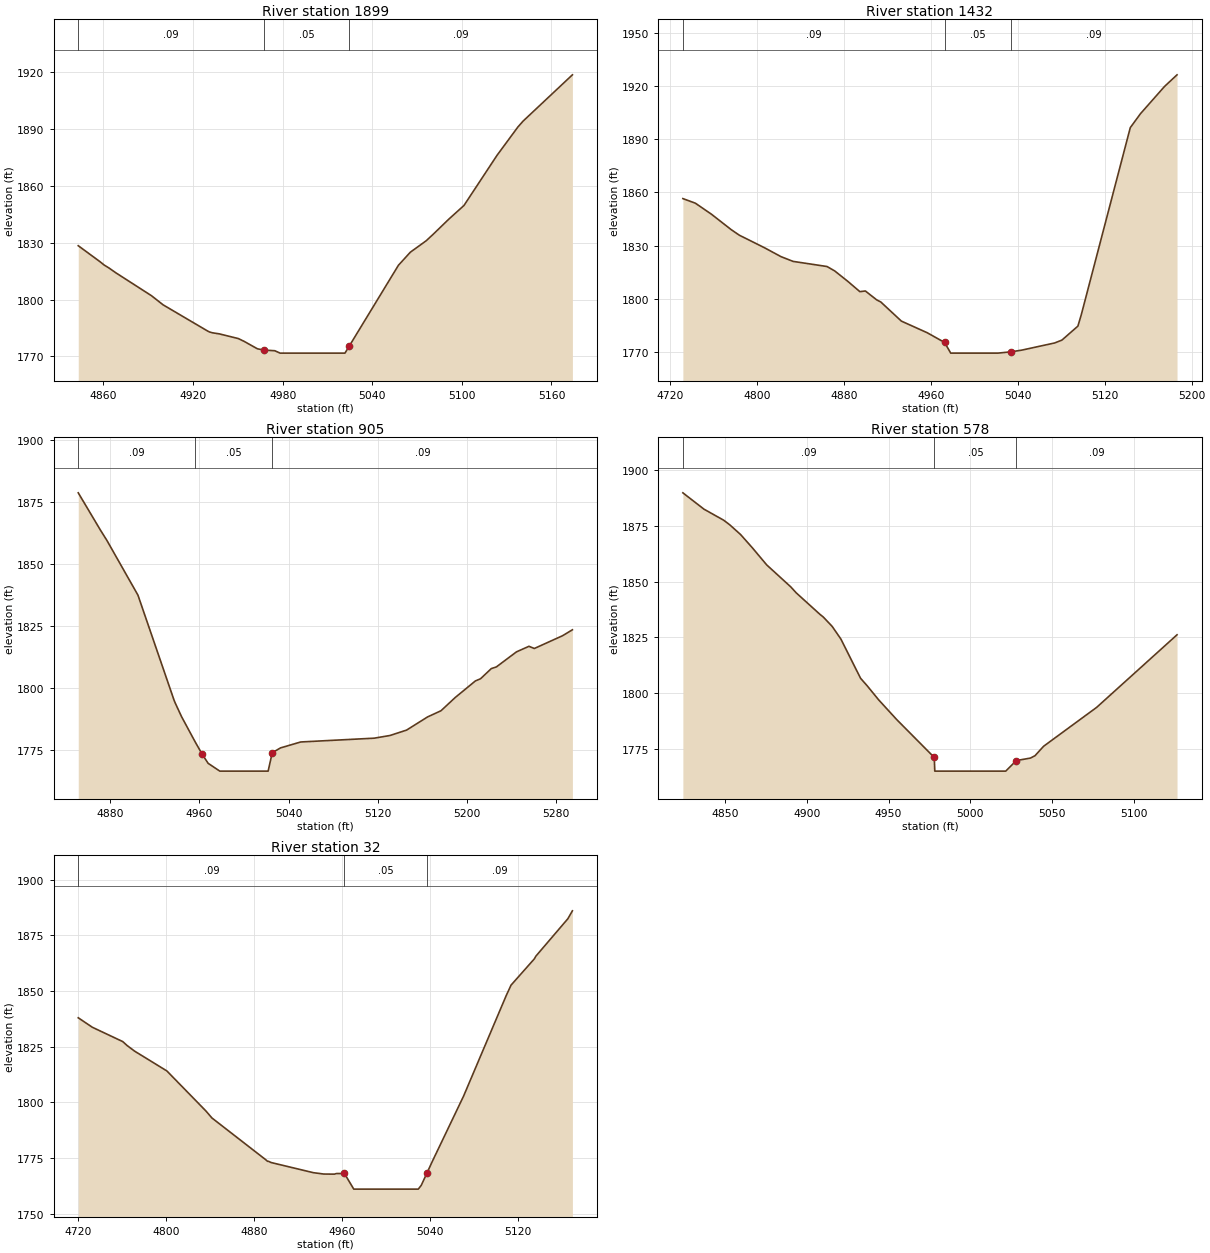
Type RM Length L Ch R = 1 ,1899    ,467,467,467
BEGIN DESCRIPTION:
Turkey_Crk_XS4
END DESCRIPTION:
XS GIS Cut Line= 6
        908732.8       738596.76       908781.73       738545.32
       908828.15       738506.43       908917.23       738421.11
       908941.07       738389.74       908951.11       738354.61
#Sta/Elev= 29
  4843.1 1828.45  4857.6 1820.06  4860.4 1818.28  4863.8 1816.62  4868.1 1814.24
  4892.1 1802.07  4899.9 1797.24  4929.8 1783.36    4931 1782.89  4932.9 1782.47
  4937.5  1781.9  4950.3 1779.41  4954.1 1777.96  4963.1    1774  4967.7 1773.31
  4974.7 1772.99  4978.3 1771.72  5021.7 1771.72  5024.61775.479  5057.5 1818.12
  5065.5 1825.04  5076.1 1831.07  5080.8 1834.51    5091  1842.3  5101.4 1849.72
  5123.5 1876.16  5137.5 1891.15    5141 1894.28    5174 1918.71
#Mann= 3 ,-1 , 0
  4843.1     .09       0  4967.7     .05       0  5024.6     .09       0
Bank Sta=4967.7,5024.6
Exp/Cntr=0.3,0.1

Type RM Length L Ch R = 1 ,1432    ,527,527,527
BEGIN DESCRIPTION:
Turkey_Crk_XS3
END DESCRIPTION:
XS GIS Cut Line= 6
       908841.96       738788.72       908949.86       738813.82
       909079.09       738876.55       909175.69       738890.35
       909229.64       738925.48       909266.03       738936.77
#Sta/Elev= 30
  4731.9 1856.52  4743.4 1853.93  4758.3 1847.66  4776.2 1839.08  4783.8 1835.88
  4807.2 1828.72  4822.2 1823.76  4833.3 1821.09  4864.5  1818.2  4871.6  1815.7
  4883.5  1809.9  4894.7 1804.03  4899.8 1804.39  4910.2 1799.38    4914 1798.18
  4932.9  1787.4  4956.6 1780.86  4972.7 1775.34  4978.3 1769.33  5021.7 1769.33
    5034 1770.08    5044 1771.06    5074 1775.08  5080.6 1776.68  5095.3 1784.56
  5098.4 1790.96  5143.5 1896.56  5152.9 1904.45    5175  1919.8  5186.5 1926.36
#Mann= 3 ,-1 , 0
  4731.9     .09       0  4972.7     .05       0    5034     .09       0
Bank Sta=4972.7,5034
Exp/Cntr=0.3,0.1

Type RM Length L Ch R = 1 ,905     ,327,327,327
BEGIN DESCRIPTION:
Turkey_Crk_XS2
END DESCRIPTION:
XS GIS Cut Line= 6
       908548.37       739135.01       908661.28       739062.24
        908691.4       739048.44        908785.5       739020.84
       908845.72       739044.67       908956.13       739069.77
#Sta/Elev= 30
  4851.2 1878.79    4871 1863.85  4876.9 1859.62  4904.8 1837.53  4937.1 1795.32
  4938.3 1793.99  4944.1 1788.39  4956.3 1778.24  4962.4 1773.43  4967.8  1769.7
  4978.3 1766.54  5021.7 1766.54  5025.4 1773.98  5032.9 1775.92    5051  1778.3
  5116.9 1779.83  5131.1 1780.91    5146 1783.09  5164.9 1788.41  5176.9 1790.89
  5189.7 1796.24  5207.8 1802.92  5212.4 1803.79  5222.1  1807.9  5226.6 1808.56
  5244.7 1814.65  5255.9 1816.89  5260.7    1816    5286 1821.14  5294.9 1823.55
#Mann= 3 ,-1 , 0
  4851.2     .09       0  4956.3     .05       0  5025.4     .09       0
Bank Sta=4962.4,5025.4
Exp/Cntr=0.3,0.1

Type RM Length L Ch R = 1 ,578     ,546,546,546
BEGIN DESCRIPTION:
turkey crk z9
END DESCRIPTION:
XS GIS Cut Line= 2
       908917.66       739365.93       908981.81       739070.53
#Sta/Elev= 26
  4824.2 1889.92  4837.1 1882.58  4849.2  1877.6  4852.9 1875.54  4859.5 1871.18
  4866.7 1865.22  4875.5 1857.52  4890.2 1847.67  4893.5    1845  4908.1 1835.29
    4910 1834.18  4915.5 1829.93  4920.9 1824.18  4932.9 1806.59  4936.9 1803.26
  4943.9 1796.96  4954.9 1788.12    4978 1771.01  4978.3 1764.87  5021.7 1764.87
  5028.2 1769.62  5036.8 1770.73  5039.6 1771.79  5044.9 1776.05  5077.3  1793.5
  5126.5 1826.13
#Mann= 3 , 0 , 0
  4824.2     .09       0    4978     .05       0  5028.2     .09       0
Bank Sta=4978,5028.2
Exp/Cntr=0.3,0.1

Type RM Length L Ch R = 1 ,32      ,0,0,0
BEGIN DESCRIPTION:
turkey crk z10
END DESCRIPTION:
XS GIS Cut Line= 4
        909039.2       739406.44       909262.02       739473.96
       909331.23       739455.39       909419.01       739340.61
#Sta/Elev= 30
  4720.4 1837.99  4733.2 1833.74  4760.8 1827.31  4764.9  1825.5  4771.6 1823.02
  4800.9 1814.13  4836.4 1796.14  4841.8 1793.03  4890.9  1774.2  4892.3 1773.58
  4893.2 1773.56  4895.6 1773.01    4934 1768.45  4943.5 1767.84  4953.2  1767.8
  4954.9 1768.07  4962.2 1768.09  4970.7 1761.07  5029.3 1761.07    5032 1762.78
    50371768.118  5042.5 1773.99  5070.4 1802.78  5109.2 1847.99  5113.2 1852.25
  5113.4 1852.56  5134.7 1864.43  5136.1 1865.65  5165.2 1882.47  5169.3 1886.01
#Mann= 3 , 0 , 0
  4720.4     .09       0  4962.2     .05       0    5037     .09       0
Bank Sta=4962.2,5037
Exp/Cntr=0.3,0.1
Stream Node=Turkey Creek    ,Reach-1         , 0 , 0 ,Upstream end
Stream Node=Turkey Creek    ,Reach-1         , 0 , 1 ,Downstream end

Chan Stop Cuts=-1
Use User Specified Reach Order=0
User Specified Reach Order=Turkey Creek    ,Reach-1