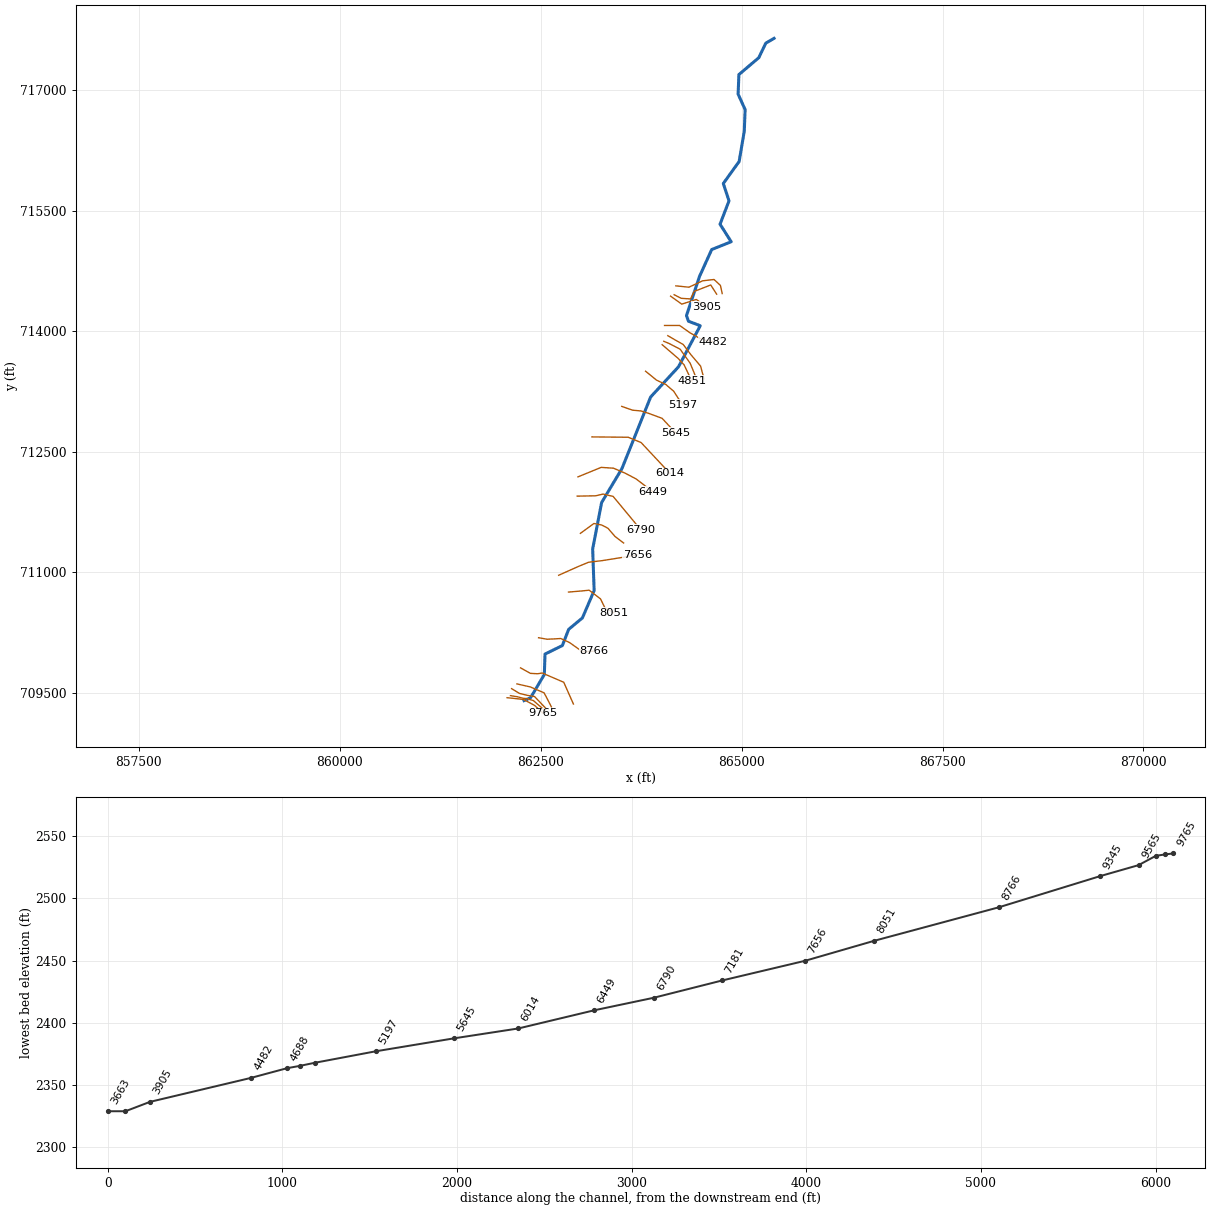
--- lds_willow _crk.prj (project) ---

Proj Title=Willow Creek Limited Detail Study
Current Plan=p02
Default Exp/Contr=0.3,0.1
English Units
Geom File=g01
Flow File=f02
Plan File=p02
Y Axis Title=Elevation
X Axis Title(PF)=Main Channel Distance
X Axis Title(XS)=Station
BEGIN DESCRIPTION:
& RWillow Creek
END DESCRIPTION:
DSS Export Rating Curves= 0
DSS Export Rating Curve Sorted= 0
DSS Export Volume Flow Curves= 0
DXF OffsetX= 0
DXF OffsetY= 0
DXF ScaleX= 1
DXF ScaleY= 10

--- lds_willow _crk.p02 (plan) ---

Plan Title=Floodway Run
Program Version=3.13
Short Identifier=Floodway
Geom File=g01
Flow File=f02
Subcritical Flow
K Sum by GR= 0
Std Step Tol= 0.01
Critical Tol= 0.01
Num of Std Step Trials= 20
Max Error Tol= 0.3
Flow Tol Ratio= 0.001
Split Flow NTrial= 30
Split Flow Tol= 0.02
Split Flow Ratio= 0.02
Log Output Level= 0
Friction Slope Method= 1
Unsteady Friction Slope Method= 2
Unsteady Bridges Friction Slope Method= 1
Parabolic Critical Depth
Global Vel Dist= 0 , 0 , 0
Global Log Level= 0
CheckData=True
Encroach Param=-1 ,10,10, 2
Encroach River=Willow Creek
Encroach Reach=Reach-1
Encroach Node=9765
       1  4967.7    5045
Encroach Node=9716
       1    4969    5017
Encroach Node=9664
       1 4969.79  5016.1
Encroach Node=9565
       1 4960.36  5015.8
Encroach Node=9345
       1 4955.78 5015.04
Encroach Node=8766
       1 4934.16  5013.7
Encroach Node=8051
       1  4870.7 5014.93
Encroach Node=7656
       1  4975.3  5015.1
Encroach Node=7181
       1    4966 5061.74
Encroach Node=6790
       1  4978.9  5024.8
Encroach Node=6449
       1  4898.6 5025.79
Encroach Node=6014
       1 4987.36 5017.42
Encroach Node=5645
       1  4985.9  5089.4
Encroach Node=5197
       1 4981.14 5060.98
Encroach Node=4851
       1    4927  5048.4
Encroach Node=4764
       1  4917.4 5021.86
Encroach Node=4688
       1 4905.89    5011
Encroach Node=4482
       1 4969.63 5016.17
Encroach Node=3905
       1 4988.25 5028.32
Encroach Node=3765
       1  3482.5 3571.77
Encroach Node=3663
       1  3527.4  3655.9
Encroach Node=3399
       4      .7
Encroach Node=2925
       1  4964.5  5014.5
Encroach Node=2456
       1  4842.6 5014.39
Encroach Node=1947
       1 4974.96 5022.97
Encroach Node=1278
       1 4933.92 5066.23
Encroach Node=990
       1 4877.89 5127.24
Encroach Node=869
       1    4920    5100
Encroach Node=790
       1    4940 5035.98
Encroach Node=544
       4      .7
Encroach Node=76
       1  4960.8  5044.5
BEGIN DESCRIPTION:
Floodway Run
END DESCRIPTION:
Computation Interval=1HOUR
Output Interval=1HOUR
Run HTab= 0
Run UNet= 0
Run PostProcess= 0
UNET Theta= 1
UNET Theta Warmup= 1
UNET ZTol= 0.02
UNET ZSATol= 0.05
UNET MxIter= 20
UNET MaxInSteps= 0
UNET DtIC= 0
UNET DtMin= 0
UNET MaxCRTS= 20
UNET WFStab= 2
UNET SFStab= 1
UNET WFX= 1
UNET SFX= 1
UNET DSS MLevel= 4
UNET DZMax Abort= 100
UNET Convert EG Bridges=-1
UNET Use Existing IB Tables=-1
UNET Froude Reduction=False
UNET Froude Limit= 1
UNET Froude Power= 10
Instantaneous Interval=1HOUR
Write IC File= 0
Echo Input=False
Echo Output=False
Write Detailed= 0
Detailed Automatic Start=False, 10

--- lds_willow _crk.f02 (steady flow) ---

Flow Title=Floodway
Program Version=3.13
Number of Profiles= 2
Profile Names=100-year,100-FW
River Rch & RM=Willow Creek,Reach-1         ,9765
    1390    1390
River Rch & RM=Willow Creek,Reach-1         ,8766
    1570    1570
River Rch & RM=Willow Creek,Reach-1         ,6790
    1850    1850
River Rch & RM=Willow Creek,Reach-1         ,1947
    1870    1870
River Rch & RM=Willow Creek,Reach-1         ,790
    2130    2130
Boundary for River Rch & Prof#=Willow Creek,Reach-1         , 1
Up Type= 0
Dn Type= 3
Dn Slope=0.016
Boundary for River Rch & Prof#=Willow Creek,Reach-1         , 2
Up Type= 0
Dn Type= 3
Dn Slope=0.016
DSS Import GetInterval= 0
DSS Import GetPeak= 0
DSS Import FillOption= 0

--- lds_willow _crk.g01 (geometry) ---

Geom Title=Existing Conditions
Program Version=3.13

River Reach=Willow Creek    ,Reach-1
Reach XY= 30
       862292.44       709401.62       862372.85       709436.45
       862544.54       709725.98       862553.27       709980.59
       862769.01       710086.72       862847.53       710288.36
       863018.16        710429.9       863164.55       710771.15
       863146.13       711287.87       863257.61       711866.64
       863509.68       712287.38        863867.4       713179.28
        864213.5       713554.46       864484.94       714066.33
       864338.55       714122.56       864313.35       714192.36
       864476.22       714680.96       864627.45       715014.46
       864869.82        715111.4       864731.18       715329.53
       864842.67       715620.37        864771.9       715836.55
        864968.7       716109.95       865032.69       716487.06
       865043.35       716756.57        864956.1       716948.52
       864965.79       717191.85         865213.       717401.25
       865300.25       717582.54       865403.27       717642.71

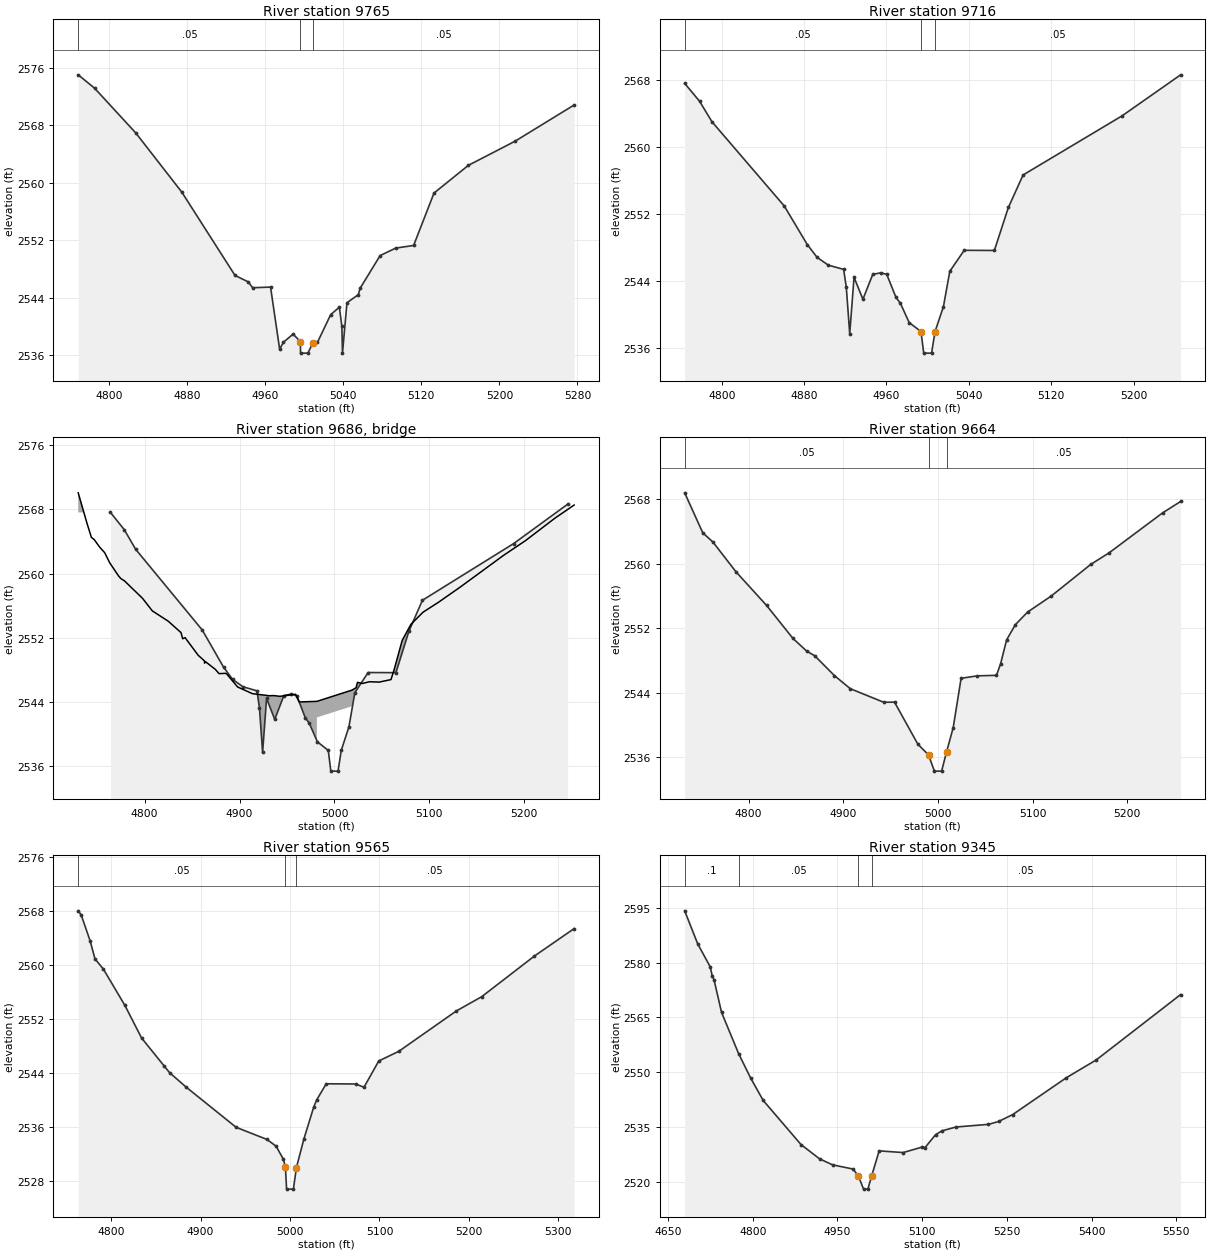
Type RM Length L Ch R = 1 ,9765    ,49,49,49
BEGIN DESCRIPTION:
Willow_Crk_XS28
END DESCRIPTION:
XS GIS Cut Line= 5
       862080.51       709437.85       862198.68       709425.59
       862286.78       709415.55       862425.06       709340.83
       862529.86       709242.72
#Sta/Elev= 30
  4768.4 2575.03  4785.1 2573.18  4827.4 2566.93  4874.6 2558.68  4929.1 2547.08
  4942.6 2546.19  4947.1 2545.37  4965.5 2545.46  4974.8 2536.82  4978.7 2537.78
  4988.6 2538.91  4996.1 2537.86  4996.2 2536.26  5003.8 2536.26  5008.6 2537.64
  5013.6 2537.77  5027.1 2541.62    5036 2542.66  5038.6 2539.97  5039.2 2536.26
  5043.8 2543.28  5055.5 2544.41  5057.2 2545.28  5077.8 2549.85  5093.7 2550.89
  5112.1 2551.26    5133 2558.56  5168.2 2562.42  5215.9 2565.77  5276.6 2570.83
#Mann= 3 ,-1 , 0
  4768.4     .05       0  4996.1     .05       0  5008.6     .05       0
Bank Sta=4996.1,5008.6
Exp/Cntr=0.5,0.3

Type RM Length L Ch R = 1 ,9716    ,52,52,52
BEGIN DESCRIPTION:
Willow_Crk_XS25
END DESCRIPTION:
XS GIS Cut Line= 6
       862122.88        709463.5       862206.49       709450.12
       862278.97       709431.16       862324.38       709426.99
       862408.33       709402.17       862551.09       709278.37
#Sta/Elev= 30
    4764 2567.61  4778.5 2565.47  4790.5 2563.03  4860.7 2552.98  4883.1 2548.37
  4892.6 2546.85  4903.5 2545.92  4918.4 2545.41    4921 2543.26  4924.3 2537.74
  4928.5 2544.47  4937.1 2541.85  4946.7 2544.82  4954.7 2545.01  4960.3 2544.81
  4969.2 2542.08 4973.51 2541.37 4982.08 2539.06  4993.5    2538  4996.2 2535.42
  5003.8 2535.42  5007.2    2538  5015.3 2540.95  5021.5 2545.18  5035.5 2547.69
  5064.8 2547.67  5078.4  2552.8  5092.7 2556.68  5188.9 2563.74  5245.7 2568.63
#Mann= 3 ,-1 , 0
    4764     .05       0  4993.5     .05       0  5007.2     .05       0
#XS Ineff= 2 , 0
       0    4950  2544.1    5041       0  2544.1
Permanent Ineff=
       T       F
Bank Sta=4993.5,5007.2
Exp/Cntr=0.5,0.3

Type RM Length L Ch R = 3 ,9686    ,,,
BEGIN DESCRIPTION:
Willow_Crk_XS26
Structure ID: Trail
Approximate Survey Structure
END DESCRIPTION:
Bridge Culvert--1,0,-1,-1, 0
Deck Dist Width WeirC Skew NumUp NumDn MinLoCord MaxHiCord MaxSubmerge Is_Ogee
11.5,37,3,0, 51, 51, , , , 0, 1,1,,
    4730  4739.3  4743.9  4746.8  4752.7  4757.9  4763.2  4772.2  4774.9  4778.6
  4797.7  4808.1  4824.8  4838.3  4840.1  4842.6  4856.4  4862.9  4863.2    4864
  4874.5  4878.4  4885.3  4886.5    4898  4913.5  4931.5  4936.3  4942.5    4959
  4962.9  4981.5  4981.5  5018.5  5018.5  5022.8  5024.3  5029.5  5036.9  5047.2
  5059.6  5062.9  5071.4  5080.6  5093.4    5110    5133  5178.2  5201.3  5232.6
  5252.6
 2570.05 2566.24  2564.5 2564.24 2563.28  2562.6 2561.34 2559.76 2559.38 2559.11
 2556.93 2555.36 2554.08 2552.66 2551.89 2552.03 2549.84 2549.15 2548.85 2549.05
 2548.08 2547.55 2547.59 2547.51 2545.89 2545.06  2544.8 2544.82 2544.73 2544.98
 2544.03  2544.1  2544.1  2545.5  2545.5  2545.8 2546.47 2546.33 2546.54  2546.5
 2546.81 2548.05 2551.69 2553.69  2555.2 2556.46 2558.36 2562.27  2564.1 2566.92
 2568.53
    2506    2506    2506    2506    2506    2506    2506    2506    2506    2506
    2506    2506    2506    2506    2506    2506    2506    2506    2506    2506
    2506    2506    2506    2506    2506    2506    2506    2506    2506    2506
    2506    2506  2542.1  2543.5    2506    2506    2506    2506    2506    2506
    2506    2506    2506    2506    2506    2506    2506    2506    2506    2506
    2506
    4730  4739.3  4743.9  4746.8  4752.7  4757.9  4763.2  4772.2  4774.9  4778.6
  4797.7  4808.1  4824.8  4838.3  4840.1  4842.6  4856.4  4862.9  4863.2    4864
  4874.5  4878.4  4885.3  4886.5    4898  4913.5  4931.5  4936.3  4942.5    4959
  4962.9  4981.5  4981.5  5018.5  5018.5  5022.8  5024.3  5029.5  5036.9  5047.2
  5059.6  5062.9  5071.4  5080.6  5093.4    5110    5133  5178.2  5201.3  5232.6
  5252.6
 2570.05 2566.24  2564.5 2564.24 2563.28  2562.6 2561.34 2559.76 2559.38 2559.11
 2556.93 2555.36 2554.08 2552.66 2551.89 2552.03 2549.84 2549.15 2548.85 2549.05
 2548.08 2547.55 2547.59 2547.51 2545.89 2545.06  2544.8 2544.82 2544.73 2544.98
 2544.03  2544.1  2544.1  2545.5  2545.5  2545.8 2546.47 2546.33 2546.54  2546.5
 2546.81 2548.05 2551.69 2553.69  2555.2 2556.46 2558.36 2562.27  2564.1 2566.92
 2568.53
    2506    2506    2506    2506    2506    2506    2506    2506    2506    2506
    2506    2506    2506    2506    2506    2506    2506    2506    2506    2506
    2506    2506    2506    2506    2506    2506    2506    2506    2506    2506
    2506    2506  2542.1  2543.5    2506    2506    2506    2506    2506    2506
    2506    2506    2506    2506    2506    2506    2506    2506    2506    2506
    2506
BR Coef= 1 , 1 , 0 ,1.25, 0 ,,,0.8,0,2,0,
WSPro=,,,, 1 ,,,, 0 ,,,, 0 ,,,,-1 ,-1 ,-1 , 0 , 0 , 0 , 0 , 0
BC Design=,, 0 ,, 0 ,,,,,,
BC HTab HWMax=2568.63

Type RM Length L Ch R = 1 ,9664    ,99,99,99
BEGIN DESCRIPTION:
Willow_Crk_XS27
END DESCRIPTION:
XS GIS Cut Line= 5
       862137.33        709550.5       862234.37       709491.38
       862329.16       709467.96       862422.83       709452.35
       862573.36       709295.13
#Sta/Elev= 30
  4732.4 2568.76  4751.5 2563.81  4762.3 2562.66  4786.6 2558.98  4818.9 2554.82
  4846.8 2550.73  4861.2 2549.17  4869.8 2548.58  4890.5 2546.14  4907.3 2544.51
  4942.6 2542.83  4954.1 2542.84  4978.7 2537.64    49902536.306  4996.2  2534.3
  5003.8  2534.3    50092536.656  5016.1  2539.7  5024.4 2545.79  5041.6  2546.1
  5061.8 2546.16  5066.2 2547.62  5072.5 2550.56  5081.7 2552.43  5094.6 2553.99
  5119.5 2555.97  5161.4  2559.9    5181 2561.35  5237.3 2566.28  5256.3 2567.69
#Mann= 3 ,-1 , 0
  4732.4     .05       0    4990     .05       0    5009     .05       0
#XS Ineff= 2 , 0
       0    4954  2542.1  5023.7       0  2542.1
Permanent Ineff=
       F       F
Bank Sta=4990,5009
Exp/Cntr=0.5,0.3

Type RM Length L Ch R = 1 ,9565    ,220,220,220
BEGIN DESCRIPTION:
Willow_Crk_XS29
END DESCRIPTION:
XS GIS Cut Line= 4
       862203.19       709609.58       862370.42       709571.68
       862542.16       709498.07       862632.47       709324.14
#Sta/Elev= 30
  4763.3 2568.04  4766.6 2567.44  4776.7 2563.56    4782 2560.93  4791.4 2559.41
  4815.5 2554.02  4834.1  2549.2  4859.7 2544.99  4865.5 2544.05    4884 2541.91
  4939.8 2535.96  4974.3 2534.16  4984.5 2533.16  4992.7  2531.2  4994.9 2530.08
  4996.2  2526.8  5003.8  2526.8  5007.2    2530  5015.5 2534.21  5026.5 2538.95
  5029.8 2540.01  5040.5 2542.41  5073.6 2542.38  5082.7 2541.89  5099.2 2545.79
  5121.6 2547.22  5185.9  2553.2  5214.2 2555.31  5273.2 2561.34  5317.6 2565.41
#Mann= 3 ,-1 , 0
  4763.3     .05       0  4994.9     .05       0  5007.2     .05       0
Bank Sta=4994.9,5007.2
Exp/Cntr=0.3,0.1

Type RM Length L Ch R = 1 ,9345    ,579,579,579
BEGIN DESCRIPTION:
Willow_Crk_XS24
END DESCRIPTION:
XS GIS Cut Line= 6
       862248.94       709808.95       862371.53       709740.58
       862463.49       709735.87       862517.72        709745.3
       862786.51       709629.77       862906.77       709358.58
#Sta/Elev= 30
  4679.5 2594.19  4702.7 2585.09  4724.8 2578.83  4728.2 2576.39  4731.5 2575.28
  4744.8 2566.35    4775 2555.07  4796.2  2548.4  4818.5 2542.25  4885.4 2530.17
  4918.2 2526.26  4941.3  2524.6  4977.4 2523.46    4987 2521.58  4996.2 2517.95
  5003.8 2517.95  5010.6  2521.6  5023.8 2528.43  5066.3 2527.97  5100.1 2529.48
  5105.1 2529.34  5123.6 2532.86  5135.2 2533.93  5159.9 2534.97  5217.3 2535.69
  5235.2 2536.48  5260.2 2538.37  5355.3 2548.48  5408.2 2553.35  5557.5 2571.25
#Mann= 4 ,-1 , 0
  4679.5      .1       0    4775     .05       0    4987     .05       0
  5010.6     .05       0
Bank Sta=4987,5010.6
Exp/Cntr=0.3,0.1

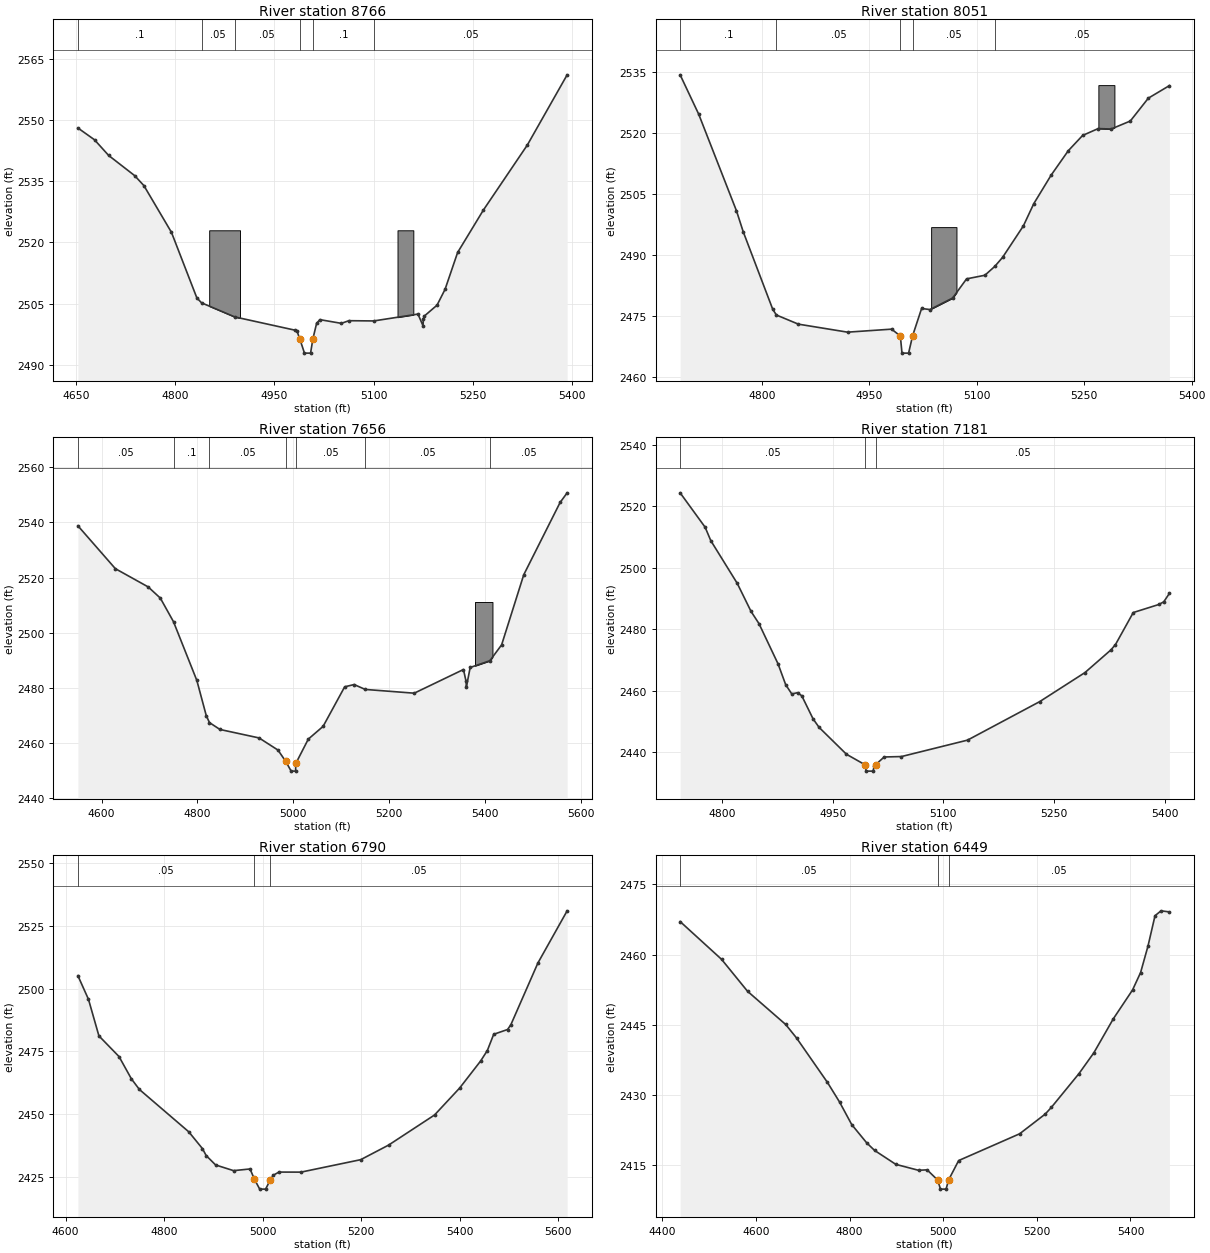
Type RM Length L Ch R = 1 ,8766    ,715,715,715
BEGIN DESCRIPTION:
Willow_Crk_XS23
END DESCRIPTION:
XS GIS Cut Line= 6
       862472.89       710183.86       862583.74       710164.99
       862748.78       710174.42       862857.24       710124.91
       863019.93       710009.37       863161.41       710016.45
#Sta/Elev= 30
  4653.2 2548.02  4678.3 2545.13  4699.7 2541.29  4738.9 2536.36  4752.9 2533.91
  4794.5 2522.48  4832.9 2506.41    4840 2505.21    4890 2501.77  4980.5 2498.54
  4984.2 2498.24  4988.2 2496.45  4995.4  2492.9  5004.6  2492.9  5008.2 2496.45
  5013.7 2500.17  5018.6  2501.1  5051.1 2500.19  5062.5 2500.84    5100 2500.78
  5166.8 2502.46  5174.5 2499.57  5174.9 2501.21  5176.3 2501.96  5195.6 2504.64
  5207.7 2508.51  5226.7 2517.54  5265.5  2527.9    5332 2543.85  5392.1 2561.03
#Mann= 6 ,-1 , 0
  4653.2      .1       0    4840     .05       0    4890     .05       0
  4988.2     .05       0  5008.2      .1       0    5100     .05       0
#XS Ineff= 2 , 0
       0                    5050       0
Permanent Ineff=
       F       T
#Block Obstruct= 2 ,-1
  4851.5  4898.1 2522.97  5135.9  5159.8 2522.97
Bank Sta=4988.2,5008.2
Exp/Cntr=0.3,0.1

Type RM Length L Ch R = 1 ,8051    ,395,395,395
BEGIN DESCRIPTION:
Willow_Crk_XS22
END DESCRIPTION:
XS GIS Cut Line= 6
       862845.47       710752.09        863010.5       710766.23
       863102.46       710775.66       863243.93        710667.2
        863295.8        710561.1       863406.58        710495.1
#Sta/Elev= 30
  4685.5 2534.22  4711.4 2524.57  4764.2 2500.82  4773.6 2495.69  4814.9 2476.61
    4820 2475.22  4850.6 2472.98  4919.4 2471.01  4980.9 2471.75  4993.1 2470.06
  4995.4 2465.86  5004.6 2465.86  5010.3 2470.16  5022.8 2476.83  5034.4 2476.56
  5066.1 2479.39  5085.6  2484.1  5111.2 2484.99    5125 2487.16  5135.9 2489.38
  5164.9  2497.1  5179.5 2502.58  5203.8  2509.6  5227.6 2515.56  5247.7 2519.33
  5269.5 2521.02  5287.5 2520.91  5314.3 2522.87  5339.5 2528.49  5368.9 2531.57
#Mann= 5 ,-1 , 0
  4685.5      .1       0    4820     .05       0  4993.1     .05       0
  5010.3     .05       0    5125     .05       0
#Block Obstruct= 2 ,-1
  5036.1  5071.5 2496.81  5269.7  5292.1 2531.69
Bank Sta=4993.1,5010.3
Exp/Cntr=0.3,0.1

Type RM Length L Ch R = 1 ,7656    ,475,475,475
BEGIN DESCRIPTION:
Willow_Crk_XS30
END DESCRIPTION:
XS GIS Cut Line= 5
       862722.83        710961.2       862964.81       711069.37
       863094.18        711122.9       863260.34       711142.98
       863703.06       711213.23
#Sta/Elev= 30
  4550.5 2538.78  4628.7 2523.22  4697.1 2516.61  4722.5 2512.55    4750 2503.97
  4798.7 2482.67  4818.3 2469.94    4825 2467.39  4846.9  2464.9  4928.5 2461.83
  4967.9 2457.43  4984.1 2453.34  4995.4 2449.79  5004.6 2449.79  5005.1 2452.56
  5031.2  2461.4  5062.1 2466.03  5107.1 2480.37  5126.8 2481.19    5150 2479.42
  5252.2 2478.06  5354.9 2486.65  5360.3 2482.36    5361 2480.31  5368.9 2487.38
    5410 2489.83  5434.5 2495.59  5480.7 2521.03  5556.5 2547.23  5571.2 2550.73
#Mann= 7 ,-1 , 0
  4550.5     .05       0    4750      .1       0    4825     .05       0
  4984.1     .05       0  5005.1     .05       0    5150     .05       0
    5410     .05       0
#Block Obstruct= 1 ,-1
  5378.9  5415.4 2511.13
Bank Sta=4984.1,5005.1
Exp/Cntr=0.3,0.1

Type RM Length L Ch R = 1 ,7181    ,391,391,391
BEGIN DESCRIPTION:
Willow_Crk_XS21
END DESCRIPTION:
XS GIS Cut Line= 6
         862994.       711483.01        863161.4       711605.61
       863258.07       711586.75       863335.88       711546.67
       863425.48       711442.93        863531.6       711362.74
#Sta/Elev= 30
  4742.9 2524.44  4776.8 2513.26  4784.5 2508.89  4820.4 2494.99  4839.1 2485.87
  4849.8 2481.93  4875.7 2468.83  4886.1 2462.04  4894.3 2459.05  4902.1 2459.44
  4907.9 2458.44  4923.2 2450.94  4931.4 2448.16  4968.5 2439.43  4993.1 2436.09
  4995.4 2433.94  5004.6 2433.94    5006 2435.47  5008.1 2436.03  5019.6 2438.54
  5043.1 2438.68  5132.7 2444.02  5230.5 2456.53    5292 2465.99  5327.2 2473.36
  5333.4 2475.11  5357.5 2485.51  5392.2 2488.13  5398.9 2489.01  5406.5 2491.74
#Mann= 3 ,-1 , 0
  4742.9     .05       0  4993.1     .05       0  5008.1     .05       0
Bank Sta=4993.1,5008.1
Exp/Cntr=0.3,0.1

Type RM Length L Ch R = 1 ,6790    ,341,341,341
BEGIN DESCRIPTION:
Willow_Crk_XS31
END DESCRIPTION:
XS GIS Cut Line= 5
       862953.63       711945.91       863184.51       711950.37
       863275.95       711971.56       863400.85       711942.57
       863745.47       711526.58
#Sta/Elev= 30
  4624.9 2505.16  4646.4 2495.72  4667.6 2481.14  4708.4  2472.9  4733.6 2463.99
  4749.8 2459.77    4850 2442.89  4877.7 2436.21  4885.4 2433.41  4904.5 2429.68
  4940.9 2427.41  4974.4 2428.08  4983.2 2424.03    4994 2420.04    5006 2420.04
  5014.8 2423.48  5021.4 2425.56    5033 2426.84  5077.9 2426.82    5199 2431.78
  5255.5 2437.58  5348.9  2449.6  5399.9 2460.35  5442.6 2471.16  5456.1 2475.31
    5469 2481.77  5497.1 2483.68  5503.8 2485.57  5558.8 2510.23  5618.1    2531
#Mann= 3 ,-1 , 0
  4624.9     .05       0  4983.2     .05       0  5014.8     .05       0
Bank Sta=4983.2,5014.8
Exp/Cntr=0.3,0.1

Type RM Length L Ch R = 1 ,6449    ,435,435,435
BEGIN DESCRIPTION:
Willow_Crk_XS20
END DESCRIPTION:
XS GIS Cut Line= 6
       862963.32       712185.63         863251.       712303.53
       863404.26        712294.1       863548.08       712232.79
       863687.19        712159.7       863899.37       711997.03
#Sta/Elev= 30
  4437.8 2467.06  4526.3    2459  4581.8 2452.18  4663.3 2445.09  4686.5 2442.21
  4752.5 2432.73  4778.4 2428.54  4804.4 2423.72  4836.4 2419.82  4853.3  2418.2
  4898.6 2415.23  4947.1 2413.96  4965.5 2414.06  4988.3 2411.85    4994 2409.94
    5006 2409.94  5011.3 2411.89  5032.9 2416.04  5163.1 2421.75  5217.7 2425.95
    5231  2427.4    5290 2434.61  5321.8 2439.06  5363.1 2446.27  5404.4 2452.46
  5421.6 2456.18  5437.3  2461.8  5452.4 2468.31  5465.2 2469.35  5483.1 2469.12
#Mann= 3 ,-1 , 0
  4437.8     .05       0  4988.3     .05       0  5011.3     .05       0
Bank Sta=4988.3,5011.3
Exp/Cntr=0.3,0.1

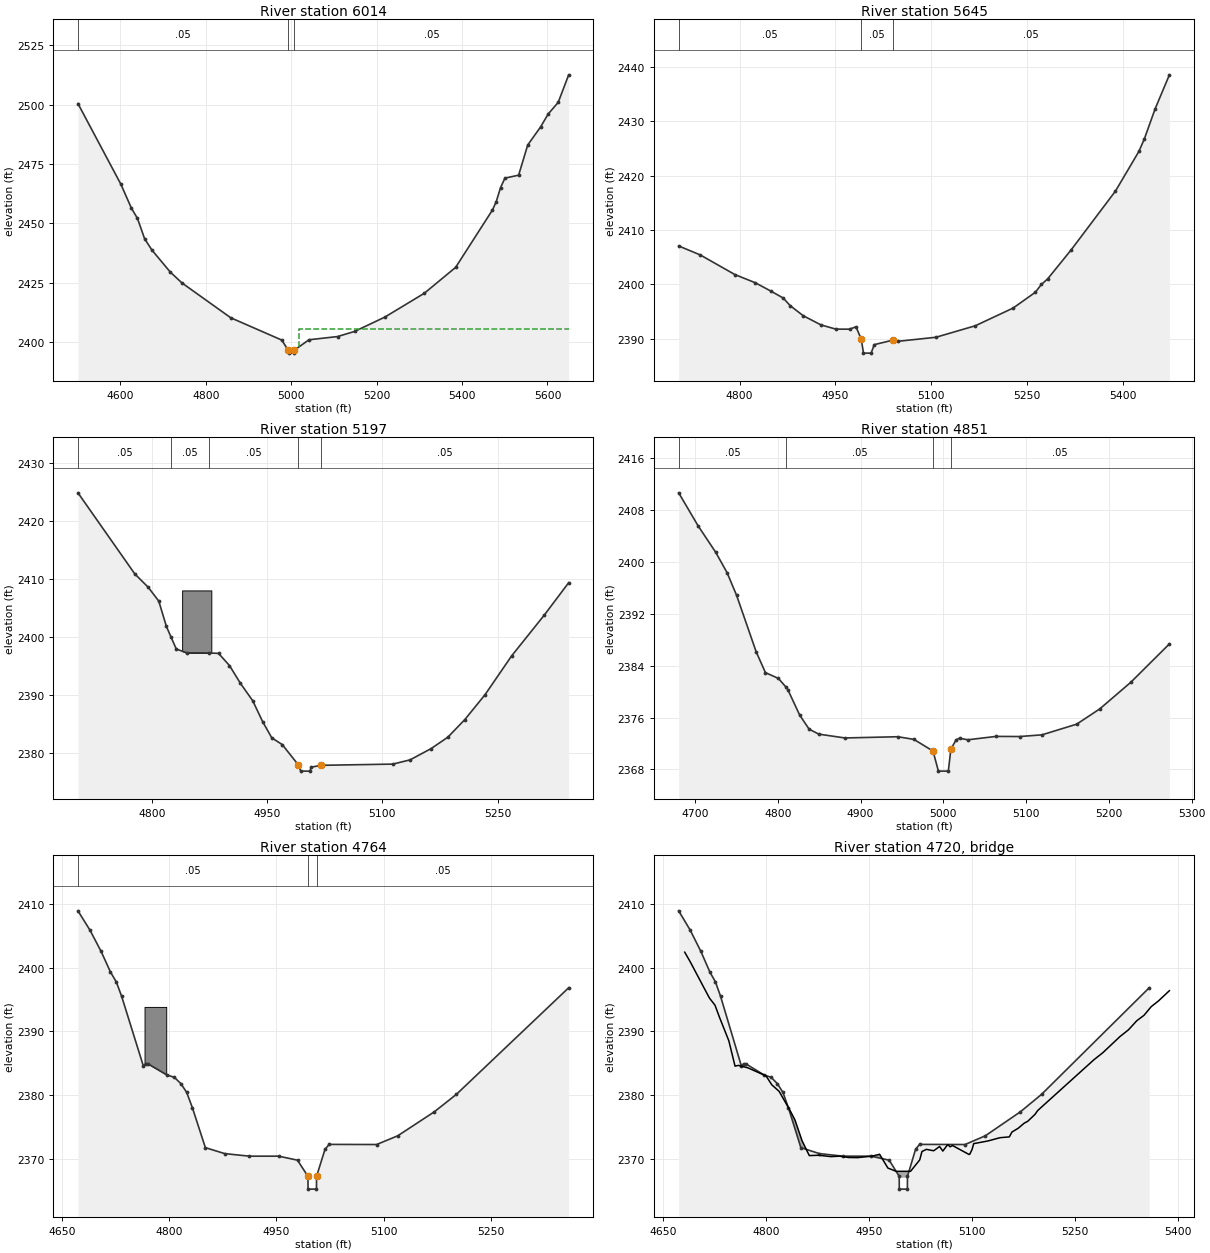
Type RM Length L Ch R = 1 ,6014    ,369,369,369
BEGIN DESCRIPTION:
Willow_Crk_XS32
END DESCRIPTION:
XS GIS Cut Line= 4
       863136.56       712683.05       863589.32       712678.59
       863748.79        712612.8       864106.78       712230.28
#Sta/Elev= 30
  4500.5 2500.45    4601 2466.46  4625.8 2456.34  4639.9 2452.05  4656.6  2443.5
  4673.7 2438.74  4716.5  2429.5    4744 2424.88  4858.5 2410.18  4977.9 2400.79
 4993.09 2396.42    4994  2395.3    5006  2395.3  5006.8 2396.47  5041.5 2400.93
  5108.4 2402.28  5148.5 2404.45  5218.7 2410.43  5311.7 2420.53    5385 2431.44
  5471.3 2455.63    5480  2459.1  5490.1 2464.99  5500.4 2469.04  5532.5 2470.28
  5553.8    2483    5584 2490.62  5601.7 2496.06  5625.2 2500.96  5649.7 2512.56
#Mann= 3 , 0 , 0
  4500.5     .05       0 4993.09     .05       0  5006.8     .05       0
#XS Ineff= 2 , 0
                         5017.42         2405.42
Permanent Ineff=
       F       F
Bank Sta=4993.09,5006.8
Exp/Cntr=0.3,0.1

Type RM Length L Ch R = 1 ,5645    ,448,448,448
BEGIN DESCRIPTION:
Willow_Crk_XS19
END DESCRIPTION:
XS GIS Cut Line= 6
       863507.99       713062.75        863642.4       713015.59
       863746.14       713006.16       863838.09       712977.86
       864010.22        712914.2       864175.24       712737.39
#Sta/Elev= 30
  4704.7 2407.06  4738.5 2405.41  4792.6  2401.8  4824.6 2400.29  4849.2 2398.74
  4868.4 2397.47  4879.1 2396.09  4899.5 2394.23  4927.4 2392.53  4950.8 2391.75
  4972.2 2391.74  4982.3 2392.18  4990.6 2389.87    4994 2387.33    5006 2387.33
  5010.8 2388.89  5040.3 2389.73  5048.2 2389.51  5107.4 2390.25  5169.1 2392.37
  5228.3 2395.63    5263 2398.53  5272.5 2399.97  5282.3    2401  5318.9 2406.31
  5388.5 2417.17  5425.2 2424.48  5433.7 2426.78  5450.6 2432.32  5472.9 2438.57
#Mann= 3 ,-1 , 0
  4704.7     .05       0  4990.6     .05       0  5040.3     .05       0
Bank Sta=4990.6,5040.3
Exp/Cntr=0.3,0.1

Type RM Length L Ch R = 1 ,5197    ,346,346,346
BEGIN DESCRIPTION:
Willow_Crk_XS18
END DESCRIPTION:
XS GIS Cut Line= 6
       863804.57       713500.47       863940.79       713389.56
       864056.32       713335.33       864155.35       713250.44
       864209.58       713165.56       864273.21       713083.07
#Sta/Elev= 30
  4703.9 2424.81  4777.9 2410.85  4795.3 2408.56  4809.1 2406.17    4819 2401.82
    4825 2399.99  4831.9 2397.92  4845.4 2397.27    4875 2397.24  4886.9 2397.17
  4901.1 2395.08  4915.3 2392.03  4931.4 2389.01  4944.3 2385.41  4956.2 2382.63
  4969.8 2381.47  4990.5 2378.02    4994  2376.9    5006  2376.9  5007.3 2377.58
  5020.6  2377.9  5113.8 2378.11  5136.2 2378.84  5163.7 2380.79  5185.4 2382.75
  5207.4 2385.77  5233.7 2390.05  5268.3 2396.73  5310.6 2403.72  5342.6 2409.34
#Mann= 5 ,-1 , 0
  4703.9     .05       0    4825     .05       0    4875     .05       0
  4990.5     .05       0  5020.6     .05       0
#Block Obstruct= 1 ,-1
  4839.5  4877.5 2408.01
Bank Sta=4990.5,5020.6
Exp/Cntr=0.3,0.1

Type RM Length L Ch R = 1 ,4851    ,87,87,87
BEGIN DESCRIPTION:
Willow_Crk_XS33
END DESCRIPTION:
XS GIS Cut Line= 4
       864010.89       713830.56       864207.13       713662.19
       864284.08       713579.66       864378.88       713379.48
#Sta/Elev= 30
  4680.2 2410.69  4703.6 2405.61  4725.1 2401.48  4738.7 2398.36  4750.1 2394.89
  4773.8 2386.16    4785 2382.94  4800.7 2382.04    4810 2380.68    4812 2380.33
  4826.4 2376.38  4837.8 2374.21  4849.5 2373.44  4881.1 2372.85    4945 2373.04
  4964.4 2372.63  4987.5 2370.83    4994 2367.73    5006 2367.73  5009.1 2371.14
  5015.5 2372.57  5019.5  2372.8  5029.7 2372.57  5063.6 2373.09    5092 2373.07
  5119.1 2373.33  5161.1 2374.98    5189 2377.34  5226.5 2381.45  5273.1 2387.37
#Mann= 4 ,-1 , 0
  4680.2     .05       0    4810     .05       0  4987.5     .05       0
  5009.1     .05       0
Bank Sta=4987.5,5009.1
Exp/Cntr=0.5,0.3

Type RM Length L Ch R = 1 ,4764    ,76,76,76
BEGIN DESCRIPTION:
Willow_Crk_XS17
END DESCRIPTION:
XS GIS Cut Line= 6
       864030.89       713872.97       864093.39       713847.31
       864234.21        713774.8       864359.17       713600.33
       864423.48       713443.61       864451.34        713373.4
#Sta/Elev= 30
  4672.7 2408.94  4689.5  2405.9  4705.1 2402.55  4718.1 2399.33  4726.3 2397.76
  4733.8 2395.48  4764.1 2384.53  4767.3 2384.92  4770.6 2384.89  4797.3 2383.13
  4807.3 2382.78  4816.5 2381.78  4824.6  2380.4  4832.6 2377.98  4850.7 2371.72
  4877.8 2370.78  4912.1 2370.38  4953.1 2370.38  4979.4 2369.75    4994  2367.2
  4994.1  2365.2  5005.9  2365.2    5006  2367.2  5017.8 2371.45  5023.6 2372.23
  5089.9 2372.21  5119.4 2373.58  5170.5 2377.35  5201.3 2380.09  5358.2 2396.85
#Mann= 3 ,-1 , 0
  4672.7     .05       0    4994     .05       0    5006     .05       0
#XS Ineff= 2 , 0
       0    4960    2368    5040       0    2368
Permanent Ineff=
       F       F
#Block Obstruct= 1 ,-1
  4765.7    4796 2393.84
Bank Sta=4994,5006
Exp/Cntr=0.5,0.3

Type RM Length L Ch R = 3 ,4720    ,,,
BEGIN DESCRIPTION:
Willow_Crk_XS16
Structure ID: Willow Creek Rd
Approximate Survey Structure
END DESCRIPTION:
Bridge Culvert--1,0,-1,-1, 0
Deck Dist Width WeirC Skew NumUp NumDn MinLoCord MaxHiCord MaxSubmerge Is_Ogee
33.5,21,3,0, 60, 60, , , , 0, 1,1,,
  4681.5  4689.5  4717.5  4725.6  4732.1  4745.8  4754.8  4759.9  4773.6    4800
  4808.3  4819.1  4834.7  4842.1  4852.5    4863  4876.6  4894.6  4907.3  4920.4
  4933.2  4954.9  4965.4  4977.5  4989.5  4989.5  5010.5  5010.5  5023.9  5027.1
  5033.6  5044.2  5052.8  5057.5    5064  5065.5    5068  5071.7  5095.6  5096.7
    5100  5102.5  5123.3  5140.7  5154.4  5158.2  5167.5  5176.1  5181.2  5191.8
  5195.7  5277.8  5290.6  5315.7  5328.1  5339.9  5350.6  5361.2  5371.9  5387.6
 2402.44 2400.93 2395.23 2394.11 2392.22  2388.5 2384.53 2384.65 2384.26 2382.99
  2381.6 2380.56 2377.61 2376.07 2372.79 2370.47 2370.52 2370.31 2370.38 2370.17
 2370.15 2370.39 2370.68 2368.51    2368    2368    2368    2368  2369.8 2371.11
 2371.45 2371.23  2371.9 2371.18 2372.11 2372.15 2371.85 2372.05 2370.65 2370.67
  2371.4 2372.35 2372.77 2373.28 2373.41 2374.17 2374.78 2375.57 2375.86 2376.95
 2377.55 2385.55 2386.64 2389.19 2390.25 2391.65 2392.52 2393.89  2394.8 2396.39
      75      75      75      75      75      75      75      75      75      75
      75      75      75      75      75      75      75      75      75      75
      75      75      75      75      75    2367    2367      75      75      75
      75      75      75      75      75      75      75      75      75      75
      75      75      75      75      75      75      75      75      75      75
      75      75      75      75      75      75      75      75      75      75
  4681.5  4689.5  4717.5  4725.6  4732.1  4745.8  4754.8  4759.9  4773.6    4800
  4808.3  4819.1  4834.7  4842.1  4852.5    4863  4876.6  4894.6  4907.3  4920.4
  4933.2  4954.9  4965.4  4977.5  4989.5  4989.5  5010.5  5010.5  5023.9  5027.1
  5033.6  5044.2  5052.8  5057.5    5064  5065.5    5068  5071.7  5095.6  5096.7
    5100  5102.5  5123.3  5140.7  5154.4  5158.2  5181.2  5191.8  5195.7  5277.8
  5290.6  5315.7  5328.1  5339.9  5350.6  5361.2  5371.9  5386.1  5387.6  5419.4
 2402.44 2400.93 2395.23 2394.11 2392.22  2388.5 2384.53 2384.65 2384.26 2382.99
  2381.6 2380.56 2377.61 2376.07 2372.79 2370.47 2370.52 2370.31 2370.38 2370.17
 2370.15 2370.39 2370.68 2368.51    2368    2368    2368    2368  2369.8 2371.11
 2371.45 2371.23  2371.9 2371.18 2372.11 2372.15 2371.85 2372.05 2370.65 2370.67
  2371.4 2372.35 2372.77 2373.28 2373.41 2374.17 2375.86 2376.95 2377.55 2385.55
 2386.64 2389.19 2390.25 2391.65 2392.52 2393.89  2394.8 2396.27 2396.39 2394.73
      75      75      75      75      75      75      75      75      75      75
      75      75      75      75      75      75      75      75      75      75
      75      75      75      75      75    2367    2367      75      75      75
      75      75      75      75      75      75      75      75      75      75
      75      75      75      75      75      75      75      75      75      75
      75      75      75      75      75      75      75      75      75      75
BR Coef= 1 , 1 , 0 ,1.25, 0 ,,,0.8,0,2,0,
WSPro=,,,, 1 ,,,, 0 ,,,, 0 ,,,,-1 ,-1 ,-1 , 0 , 0 , 0 , 0 , 0
BC Design=,, 0 ,, 0 ,,,,,,
BC HTab HWMax=2408.94

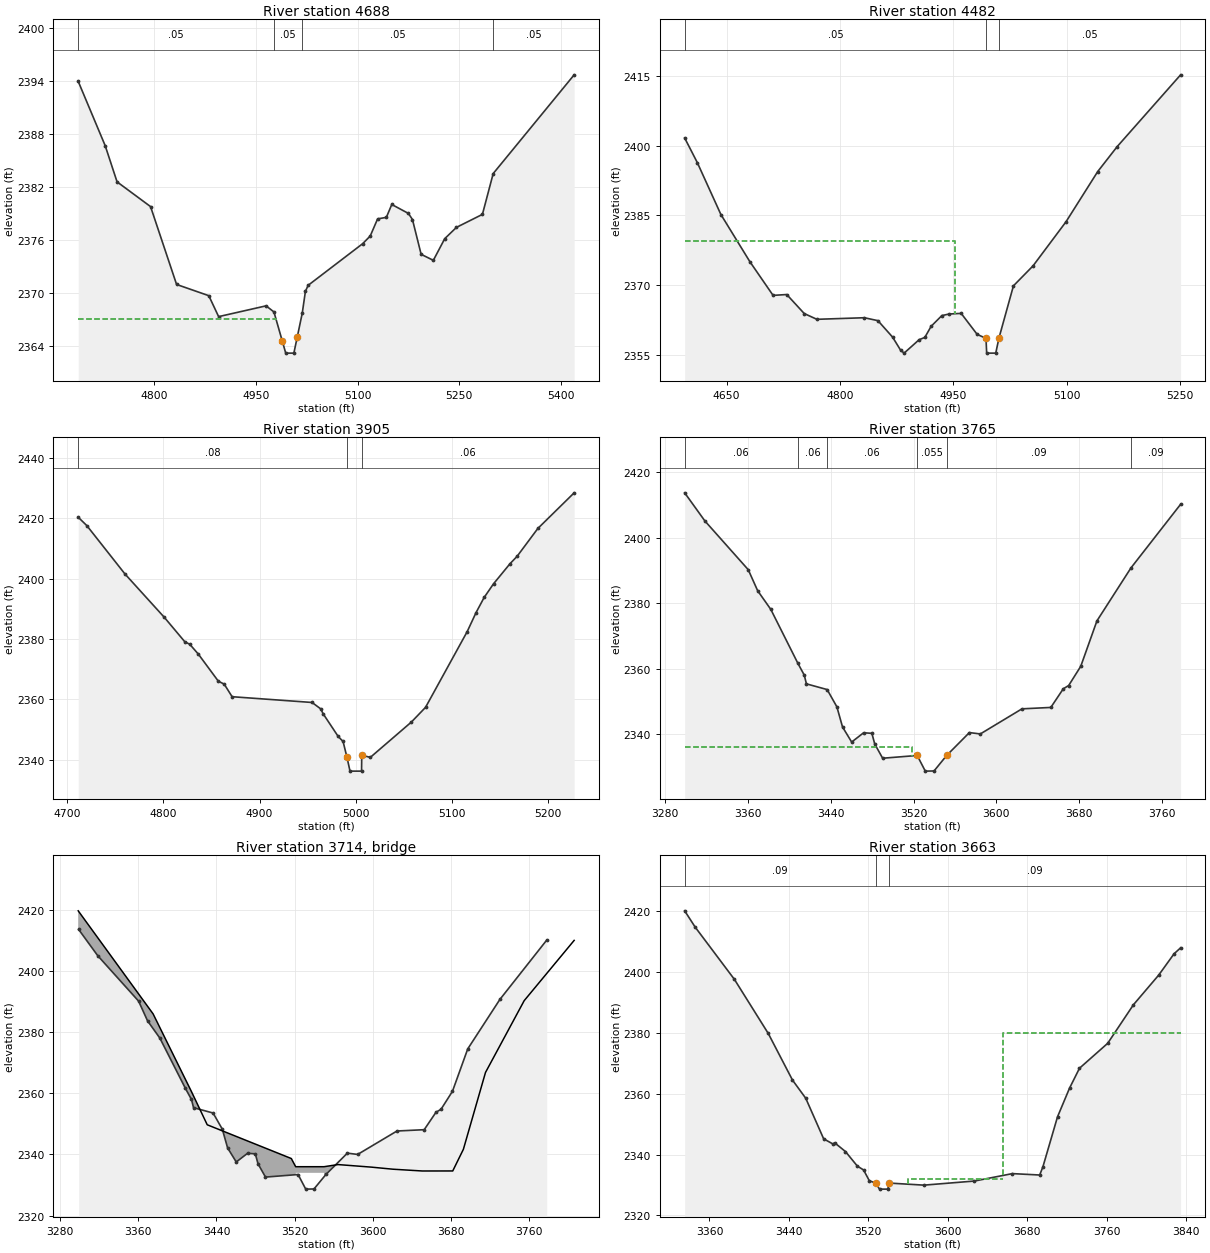
Type RM Length L Ch R = 1 ,4688    ,206,206,206
BEGIN DESCRIPTION:
Willow_Crk_XS15
END DESCRIPTION:
XS GIS Cut Line= 6
       864081.14        713943.2       864170.33        713890.8
       864272.93       713832.81       864366.25       713708.79
       864489.28       713564.05       864531.66       713404.55
#Sta/Elev= 30
  4687.9 2393.99  4727.7 2386.71  4745.2 2382.62  4794.6 2379.82    4833 2371.01
  4880.5 2369.74    4895 2367.37    4965 2368.59  4976.6  2367.9    49892364.579
    4994 2363.24    5006 2363.24    50112365.071  5018.4 2367.78    5023 2370.22
    5027 2370.91  5107.4 2375.62  5118.6 2376.49  5129.5 2378.43  5142.4  2378.6
  5150.4 2380.06  5174.9 2379.05  5180.9 2378.36  5193.7 2374.42  5211.7 2373.74
  5228.5 2376.19  5245.8 2377.47  5284.1 2378.94    5300 2383.56  5419.4 2394.73
#Mann= 4 ,-1 , 0
  4687.9     .05       0  4976.6     .05       0  5018.4     .05       0
    5300     .05       0
#XS Ineff= 2 , 0
       0    4980  2367.1    5020       0  2367.1
Permanent Ineff=
       F       F
Bank Sta=4989,5011
Exp/Cntr=0.5,0.3

Type RM Length L Ch R = 1 ,4482    ,577,577,577
BEGIN DESCRIPTION:
Willow_Crk_XS14
END DESCRIPTION:
XS GIS Cut Line= 6
       864040.27       714069.72       864228.85       714069.72
       864353.22       713981.13       864481.47       713907.53
       864563.99       713881.88        864643.2       713868.49
#Sta/Elev= 30
  4594.6 2401.64  4611.3 2396.36  4642.5 2385.21  4680.8 2375.09  4711.5 2367.85
  4729.6 2368.03  4752.7 2363.95  4769.4 2362.71  4832.2 2363.05  4850.2 2362.42
  4869.6 2358.88  4880.1  2356.1  4884.8 2355.45  4904.7 2358.34  4912.2 2358.82
  4920.5  2361.2  4934.7 2363.51  4944.5 2363.85  4960.3 2363.98  4981.4 2359.48
  4993.1 2358.62    4994 2355.45    5006 2355.45  5010.3 2358.72  5029.4  2369.9
  5055.3 2374.18    5099 2383.67  5140.9 2394.44  5166.6 2399.79  5250.5  2415.2
#Mann= 3 ,-1 , 0
  4594.6     .05       0  4993.1     .05       0  5010.3     .05       0
#XS Ineff= 2 , 0
         4951.93 2379.54
Permanent Ineff=
       F       F
Bank Sta=4993.1,5010.3
Exp/Cntr=0.3,0.1

Type RM Length L Ch R = 1 ,3905    ,140,140,140
BEGIN DESCRIPTION:
Willow_Crk_XS34
END DESCRIPTION:
XS GIS Cut Line= 4
       864115.69       714434.46       864255.09        714335.2
       864435.75       714393.19       864561.76       714303.98
#Sta/Elev= 30
  4711.6 2420.32  4720.6 2417.53  4760.1 2401.55  4801.2  2387.1  4822.4 2379.04
  4827.5 2378.23  4836.5 2374.93  4857.2 2365.99  4863.3 2365.02  4871.5 2360.85
  4954.6 2358.94  4963.6 2356.81    4966 2355.24  4981.7 2347.69  4986.8 2346.01
 4990.87 2340.75    4994 2336.19    5006 2336.19  5006.2 2341.48  5015.1 2340.74
  5057.8 2352.46  5072.5 2357.33  5115.8 2382.44    5125 2388.74  5133.4 2393.75
  5143.1 2398.25  5160.3 2404.94  5167.6 2407.36  5189.2 2416.61  5226.9 2428.41
#Mann= 3 , 0 , 0
  4711.6     .08       0 4990.87     .05       0  5006.2     .06       0
Bank Sta=4990.87,5006.2
Exp/Cntr=0.5,0.3

Type RM Length L Ch R = 1 ,3765    ,102,102,102
BEGIN DESCRIPTION:
Willow_Crk_XS13
END DESCRIPTION:
XS GIS Cut Line= 6
       864160.33       714452.28       864247.28       714407.69
       864364.38       714399.88       864407.87       714492.45
       864615.29       714573.85       864688.88       714459.01
#Sta/Elev= 30
3298.936 2413.693318.452  2405.13360.313 2390.213369.435 2383.773382.092 2378.09
3408.255 2361.613414.406 2358.013416.528 2355.323436.539 2353.583445.943  2348.3
3451.388 2342.153460.227 2337.543471.753 2340.383479.743 2340.213482.501 2336.95
3490.137  2332.63523.513 2333.44 3531.33 2328.663539.776 2328.713552.009 2333.46
 3573.93 2340.443584.466 2340.02  3624.7 2347.69 3652.56 2348.123664.581 2353.81
3669.813 2354.823681.481 2360.693697.108 2374.573729.988 2390.76 3777.93 2410.19
#Mann= 6 ,-1 , 0
3298.936     .06       03408.255     .06       03436.539     .06       0
3523.513    .055       03552.009     .09       03729.988     .09       0
#XS Ineff= 2 , 0
       0 3518.32    2336 3580.02       0    2336
Permanent Ineff=
       F       F
Bank Sta=3523.513,3552.009
Skew Angle= 45
Exp/Cntr=0.5,0.3

Type RM Length L Ch R = 3 ,3714    ,,,
BEGIN DESCRIPTION:
Willow_Crk_XS12
Structure ID: Willow Crk Rd SR 1394
Approximate Survey Structure
END DESCRIPTION:
Bridge Culvert--1,0,-1,-1, 0
Deck Dist Width WeirC Skew NumUp NumDn MinLoCord MaxHiCord MaxSubmerge Is_Ogee
43,24,3,45, 18, 19, , , , 0, 1,1,,
3298.5113375.1623414.5483430.5293516.5833521.0383521.038 3550.03 3550.033564.384
3598.1843620.6693650.6513681.7633692.6533715.2813754.8783806.002
 2419.78 2386.03 2360.49 2349.73 2338.68    2336    2336    2336    2336  2336.7
 2335.87 2335.18  2334.6 2334.61  2341.7 2366.86 2390.37  2410.1
    2303    2303    2303    2303    2303    2303    2334    2334    2303    2303
    2303    2303    2303    2303    2303    2303    2303    2303
3298.5113375.1623414.5483430.5293516.5833521.0383521.038 3550.03 3550.033564.384
3598.1843620.6693650.6513681.7633692.6533715.2813754.8783806.0023833.579
 2419.78 2386.03 2360.49 2349.73 2338.68    2336    2336    2336    2336  2336.7
 2335.87 2335.18  2334.6 2334.61  2341.7 2366.86 2390.37  2410.1 2407.58
    2303    2303    2303    2303    2303    2303    2334    2334    2303    2303
    2303    2303    2303    2303    2303    2303    2303    2303    2303
BR Coef= 1 , 1 , 0 ,1.25, 0 ,,,0.8,0,2,0,
WSPro=,,,, 1 ,,,, 0 ,,,, 0 ,,,,-1 ,-1 ,-1 , 0 , 0 , 0 , 0 , 0
BC Design=,, 0 ,, 0 ,,,,,,
BC HTab HWMax=2359.22

Type RM Length L Ch R = 1 ,3663    ,264,264,264
BEGIN DESCRIPTION:
Willow_Crk_XS11
END DESCRIPTION:
XS GIS Cut Line= 6
        864181.5        714562.7        864344.3       714545.97
       864513.81       714625.15       864656.56       714641.88
       864735.73       714568.28       864758.04       714466.77
#Sta/Elev= 30
3334.998 2420.153345.533 2414.813385.132  2397.63419.144 2379.87 3443.61 2364.51
3456.974 2358.533475.005  2345.23484.481 2343.483486.178 2343.883496.997 2341.01
3509.017 2336.21 3515.24 2334.963521.038 2331.413527.402 2330.663531.291 2328.66
3539.776 2328.663540.696 2330.663576.051 2329.973626.892 2331.323665.146 2333.76
3692.653  2333.33695.835 2335.923710.614 2352.423722.705 2361.843732.746  2368.4
3761.172  2376.63787.122 2389.283812.577 2399.033828.064 2406.04 3834.64 2407.99
#Mann= 3 ,-1 , 0
3334.998     .09       03527.402    .055       03540.696     .09       0
#XS Ineff= 3 ,-1
3377.354  3517.4  2332.1 3560.03 3655.87  2332.1  3655.9 3834.64    2380
Permanent Ineff=
       F       F       F
Bank Sta=3527.402,3540.696
Skew Angle= 45
Exp/Cntr=0.5,0.3