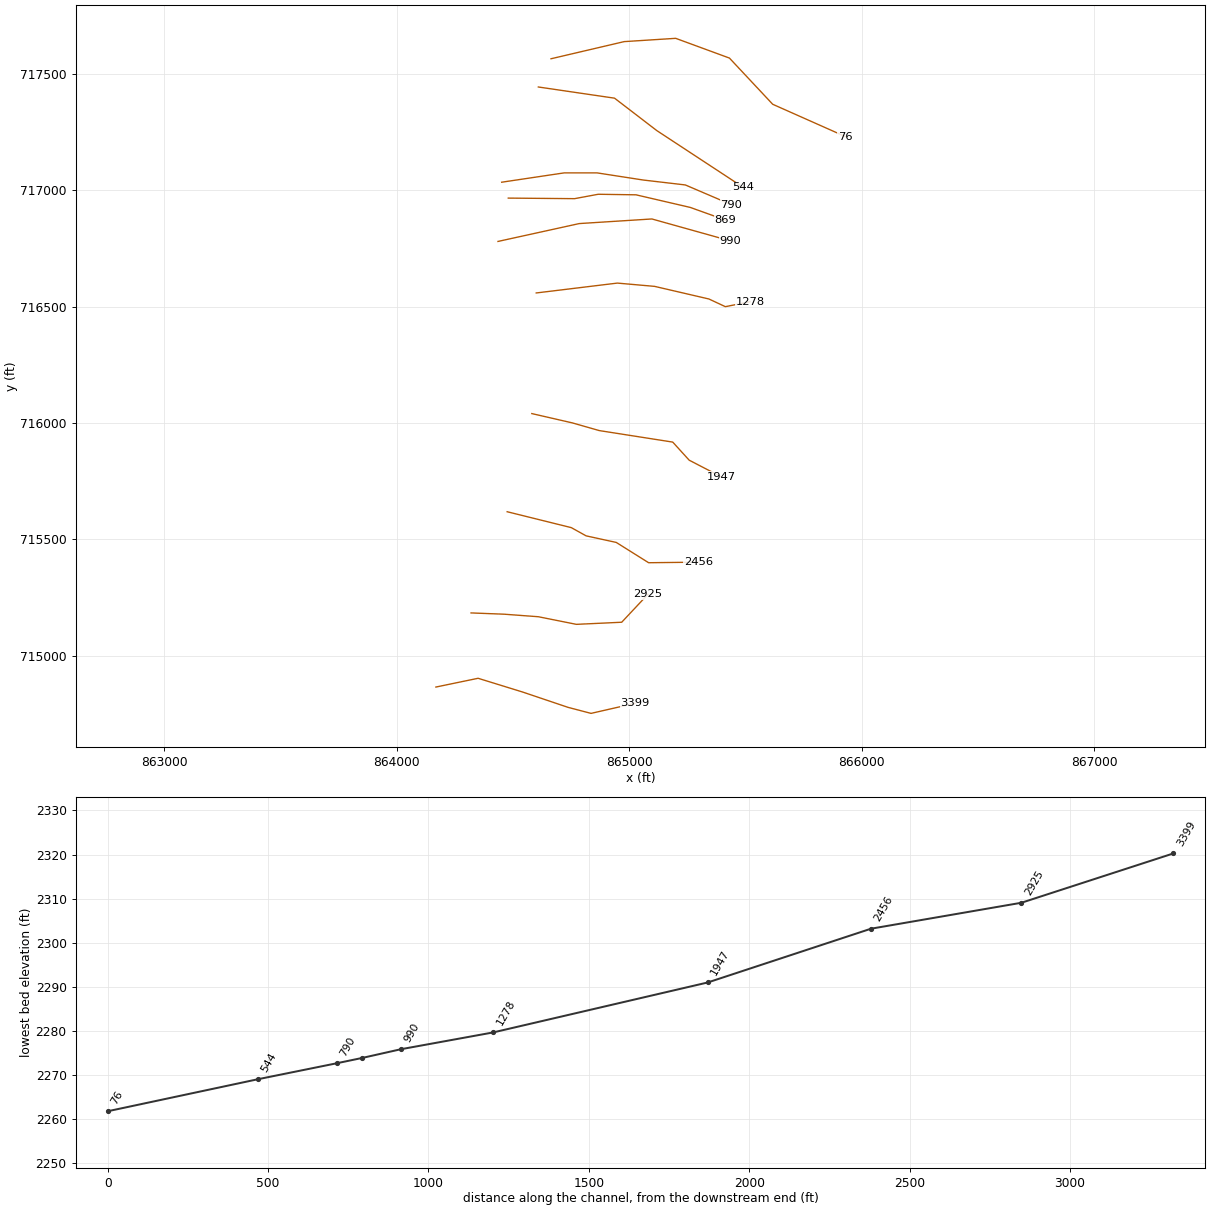
HEC-RAS study lds_willow _crk.prj: Willow Creek Limited Detail Study

--- lds_willow _crk.g01 (geometry) --- (continued)

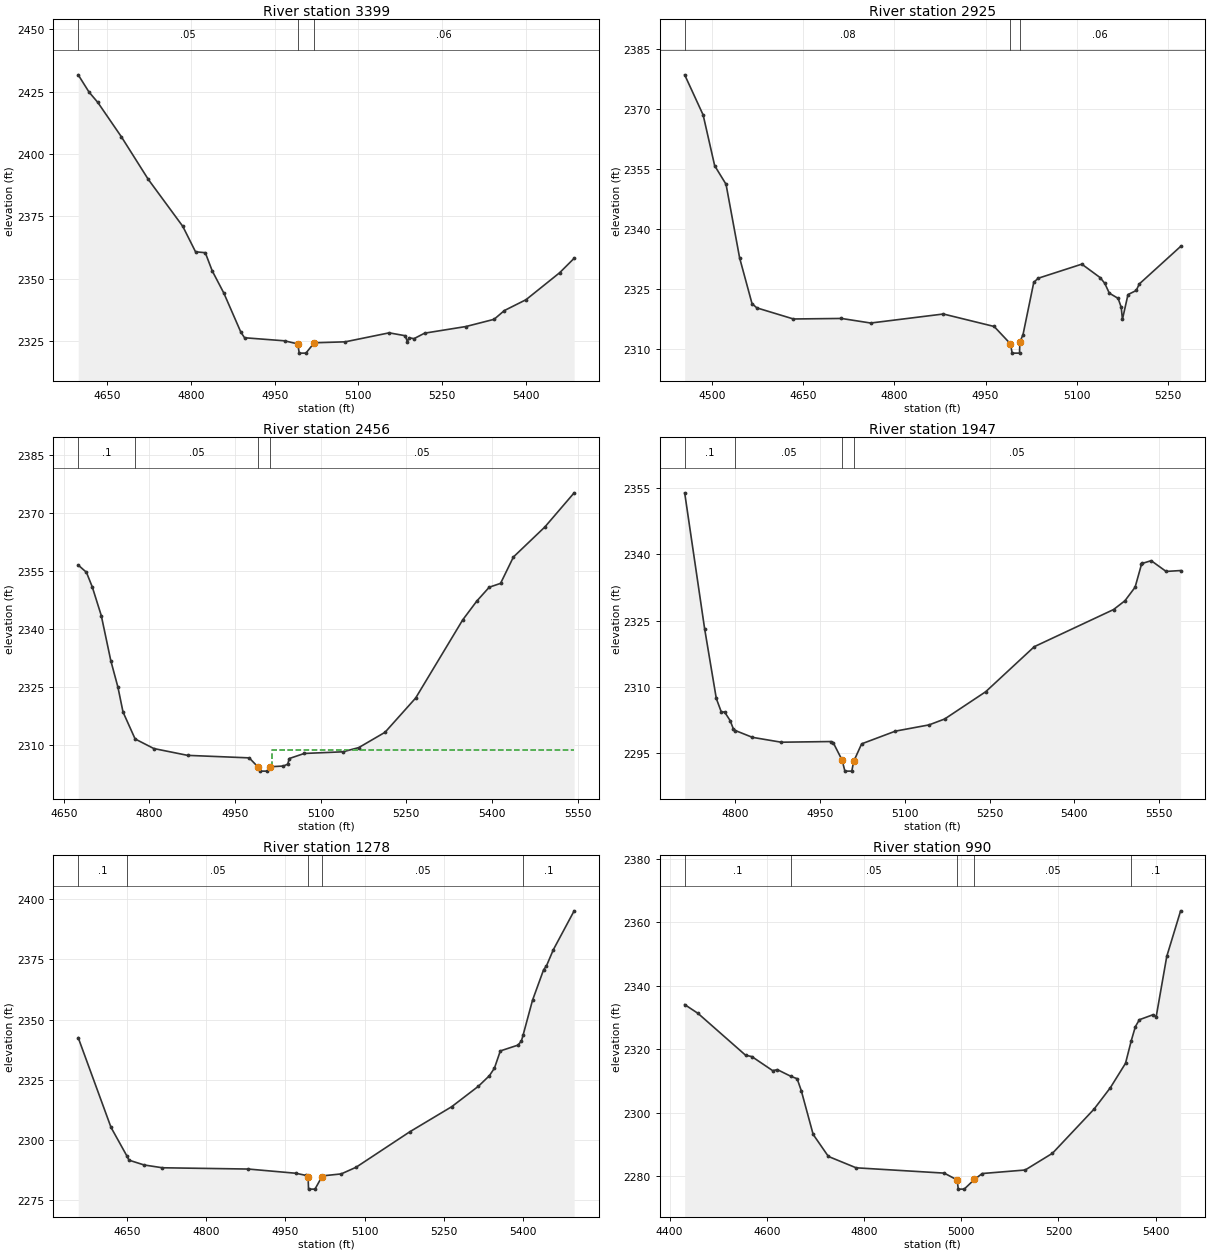
Type RM Length L Ch R = 1 ,3399    ,474,474,474
BEGIN DESCRIPTION:
Willow_Crk_XS10
END DESCRIPTION:
XS GIS Cut Line= 6
       864168.17       714864.66       864349.71       714902.38
       864540.69       714843.44       864736.39       714777.42
       864835.42       714751.48       865024.55       714794.66
#Sta/Elev= 30
  4598.2 2431.77  4617.5 2424.88  4633.3 2420.71  4675.6 2406.91  4723.7 2389.87
  4785.5 2371.05  4808.3 2360.86  4825.8 2360.49  4838.2 2353.22    4859 2344.31
  4889.4 2328.69  4896.1 2326.41  4967.9 2325.18  4991.5 2323.93    4994 2320.25
    5006 2320.25  5020.9 2324.39  5076.4 2324.78  5155.1 2328.38  5183.7 2327.23
  5187.7 2324.87  5190.8 2326.41  5199.6 2326.05  5218.6 2328.25  5292.6 2330.91
    5343  2333.8  5361.5 2337.32  5400.2 2341.66  5460.5 2352.48  5486.4 2358.26
#Mann= 3 ,-1 , 0
  4598.2     .05       0  4991.5     .05       0  5020.9     .06       0
Bank Sta=4991.5,5020.9
Exp/Cntr=0.3,0.1

Type RM Length L Ch R = 1 ,2925    ,469,469,469
BEGIN DESCRIPTION:
Willow_Crk_XS35
END DESCRIPTION:
XS GIS Cut Line= 6
       864319.38       715183.45       864461.34       715177.99
       864608.76       715167.07       864772.56       715134.31
        864967.3       715143.41       865080.14       715263.53
#Sta/Elev= 30
  4454.6  2378.5    4485 2368.49    4504 2355.82  4522.7  2351.2  4545.1 2332.81
  4565.5 2321.42  4573.4 2320.36  4633.7 2317.59  4712.7 2317.72  4760.9 2316.58
  4880.6 2318.83  4964.2 2315.72  4990.8 2311.43    4994 2309.07    5006 2309.07
  5006.6 2311.83  5011.8 2313.71  5029.5 2326.74  5036.7 2327.75  5108.6 2331.27
  5138.9  2327.9  5146.4 2326.48  5153.9 2324.03  5168.4 2322.73  5173.5  2320.5
  5175.5  2317.5  5184.6 2323.67  5198.2  2324.7  5203.2 2326.32  5271.3 2335.69
#Mann= 3 , 0 , 0
  4454.6     .08       0  4990.8     .05       0  5006.6     .06       0
Bank Sta=4990.8,5006.6
Exp/Cntr=0.3,0.1

Type RM Length L Ch R = 1 ,2456    ,509,509,509
BEGIN DESCRIPTION:
Willow_Crk_XS9
END DESCRIPTION:
XS GIS Cut Line= 6
       864474.75        715618.6       864750.57       715550.24
       864814.23       715514.87       864943.91       715486.58
       865083.02       715399.34       865297.55        715401.7
#Sta/Elev= 30
  4675.3 2356.49  4689.7 2354.62    4700 2350.81  4715.7 2343.43  4732.4 2331.76
  4744.9 2324.89  4753.8 2318.48    4775 2311.51  4807.8 2309.03  4866.9 2307.27
  4974.8 2306.62  4990.2 2304.28    4994 2303.19    5006 2303.19  5011.3 2304.32
  5034.9 2304.51  5042.3    2305  5045.1 2306.45  5071.3 2307.76  5139.1 2308.19
  5166.8 2309.28  5212.8 2313.24  5266.4 2322.09  5348.9 2342.32  5373.6 2347.19
  5395.3 2350.76  5415.2 2351.76  5437.7 2358.58  5492.8 2366.35  5544.1 2375.18
#Mann= 4 ,-1 , 0
  4675.3      .1       0    4775     .05       0  4990.2     .05       0
  5011.3     .05       0
#XS Ineff= 2 , 0
                         5014.39         2308.67
Permanent Ineff=
       F       F
Bank Sta=4990.2,5011.3
Exp/Cntr=0.3,0.1

Type RM Length L Ch R = 1 ,1947    ,669,669,669
BEGIN DESCRIPTION:
Willow_Crk_XS6
END DESCRIPTION:
XS GIS Cut Line= 6
       864580.77       716040.67       864755.28       716000.58
       864870.82       715967.57       865186.76       715918.06
        865257.5       715840.25       865394.22       715769.53
#Sta/Elev= 30
  4710.2 2353.85  4745.5 2323.18  4766.2 2307.41  4774.8 2304.45  4781.1 2304.32
  4790.7 2302.42  4796.2 2300.61    4800 2300.17  4830.1 2298.64  4881.1 2297.54
  4968.5 2297.69  4973.2 2297.44  4988.8 2293.53  4993.9 2291.01  5006.1 2291.01
  5009.4 2293.19  5023.5 2297.17  5083.3 2300.04  5142.9 2301.45  5170.5 2302.78
  5243.2 2308.94  5329.2 2319.11  5469.5 2327.49  5489.7 2329.48  5507.7 2332.54
    5519  2337.7  5520.6 2337.92  5536.2 2338.53  5562.6  2336.1  5588.3  2336.3
#Mann= 4 ,-1 , 0
  4710.2      .1       0    4800     .05       0  4988.8     .05       0
  5009.4     .05       0
Bank Sta=4988.8,5009.4
Exp/Cntr=0.3,0.1

Type RM Length L Ch R = 1 ,1278    ,288,288,288
BEGIN DESCRIPTION:
Willow_Crk_XS5
END DESCRIPTION:
XS GIS Cut Line= 6
       864599.67       716559.38       864948.63       716601.83
       865108.96       716587.68       865342.38       716533.45
       865413.12       716500.44       865519.19       716521.65
#Sta/Elev= 30
  4558.1 2342.52  4620.2 2305.29    4650 2293.53  4654.1 2291.71    4683  2289.7
  4717.5 2288.55  4880.1 2288.02  4969.7 2286.28  4989.2 2285.38  4993.1 2284.61
  4993.9 2279.69  5006.1 2279.69  5018.6 2284.61  5020.3 2285.19  5055.7    2286
  5083.8 2288.75  5185.6 2303.49  5264.8 2313.88  5315.4 2322.38  5336.2 2326.76
  5345.7  2329.9  5356.8 2337.02  5390.3 2339.44  5396.7 2341.16    5400 2343.68
  5417.7 2358.03  5438.7  2370.7  5444.1  2372.3    5457 2378.96  5496.5 2395.14
#Mann= 5 ,-1 , 0
  4558.1      .1       0    4650     .05       0  4993.1     .05       0
  5018.6     .05       0    5400      .1       0
Bank Sta=4993.1,5018.6
Exp/Cntr=0.3,0.1

Type RM Length L Ch R = 1 ,990     ,121,121,121
BEGIN DESCRIPTION:
Willow_Crk_XS36
END DESCRIPTION:
XS GIS Cut Line= 4
       864435.34       716780.95       864784.79       716857.78
       865097.04        716877.6       865434.06       716783.43
#Sta/Elev= 30
  4430.9 2334.07  4458.3  2331.3  4556.3 2318.09  4569.2 2317.67  4612.1 2313.23
  4621.6 2313.56    4650 2311.41  4662.3  2310.7  4670.8 2306.96  4695.3 2293.13
  4726.6 2286.19  4783.8  2282.6    4965 2280.93  4991.7 2278.77  4993.9 2275.88
  5006.1 2275.88  5027.2 2278.94  5043.3  2280.8  5131.6 2281.91  5187.8 2287.19
  5273.3  2301.1    5307 2307.88  5338.1 2315.55    5350 2322.72  5358.4 2327.12
  5366.7  2329.3  5394.7 2330.87  5401.2 2330.21    5423 2349.27  5451.5 2363.63
#Mann= 5 ,-1 , 0
  4430.9      .1       0    4650     .05       0  4991.7     .05       0
  5027.2     .05       0    5350      .1       0
Bank Sta=4991.7,5027.2
Exp/Cntr=0.5,0.3

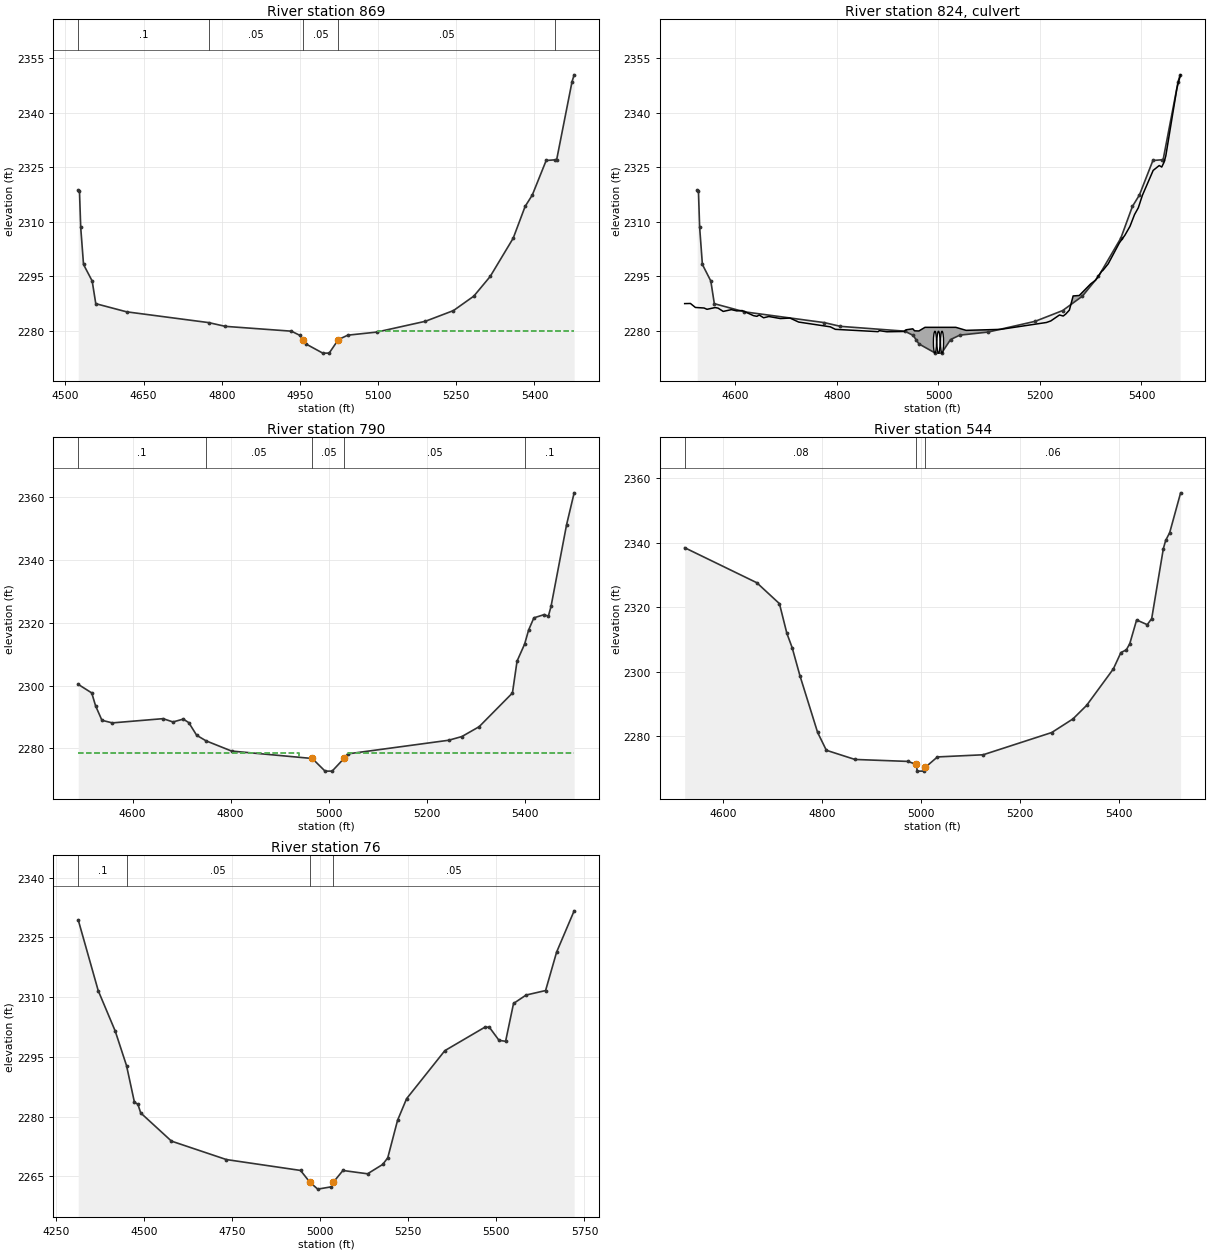
Type RM Length L Ch R = 1 ,869     ,79,79,79
BEGIN DESCRIPTION:
Willow_Crk_XS4
END DESCRIPTION:
XS GIS Cut Line= 6
       864479.45       716967.29       864764.72       716964.93
        864866.1       716983.79       865028.79       716981.43
       865262.21        716927.2       865413.14       716872.97
#Sta/Elev= 30
  4524.6 2318.67    4527 2318.59  4529.4 2308.49  4534.8  2298.3  4551.4 2293.75
  4558.3 2287.51  4617.4 2285.27    4775  2282.3  4806.8 2281.27  4933.7 2279.94
  4950.3 2278.76  4955.8 2277.58  4961.6 2276.42  4993.9  2273.9  5006.1  2273.9
  5023.8 2277.63  5041.8 2278.84  5097.5 2279.69  5190.6 2282.66  5244.6 2285.61
  5283.7 2289.59  5315.1    2295  5359.3 2305.55  5382.1 2314.27  5395.9 2317.42
  5422.5 2326.92    5440 2327.11  5442.7 2327.19  5472.2 2348.65  5476.2  2350.5
#Mann= 5 ,-1 , 0
  4524.6      .1       0    4775     .05       0  4955.8     .05       0
  5023.8     .05       0    5440      .1       0
#XS Ineff= 2 , 0
       0    4920    2280    5100       0    2280
Permanent Ineff=
       F       F
Bank Sta=4955.8,5023.8
Exp/Cntr=0.5,0.3

Type RM Length L Ch R = 2 ,824     ,,,
BEGIN DESCRIPTION:
Willow_Crk_XS3
Structure ID: Bee Branch Rd
Approximate Survey Structure
END DESCRIPTION:
Bridge Culvert--1,0,-1,-1, 0
Deck Dist Width WeirC Skew NumUp NumDn MinLoCord MaxHiCord MaxSubmerge Is_Ogee
30,30,3,0, 60, 60, , , , 0, 1,1,,
  4499.9  4511.2    4521    4538    4544  4559.8  4565.6  4575.8    4592  4602.6
  4613.2  4635.6  4642.2  4646.8  4655.4  4665.8  4688.4  4707.4  4724.5  4786.8
  4796.8  4880.9  4883.4  4898.3  4932.3  4936.4  4949.4  4952.9  4961.4  4973.4
  5034.2  5054.4  5122.3  5212.6  5221.3  5238.4  5245.8  5250.8  5257.9  5265.3
  5277.4  5299.8  5309.5  5322.3  5323.5  5334.5  5356.4  5367.2  5377.3  5386.3
  5393.8  5401.7    5423  5434.9  5439.9  5444.4  5447.9  5469.7  5472.4  5477.1
 2287.53 2287.57 2286.47 2286.32 2285.96 2286.44 2286.29 2285.38 2285.87 2285.52
 2285.62 2284.21 2284.03 2284.39 2283.63 2283.98 2283.42 2283.55 2282.45 2281.14
 2280.45 2279.81 2280.08 2279.78 2279.86 2280.33 2280.59 2280.04    2280    2281
    2281 2280.17 2280.44 2282.33 2282.76  2284.4 2284.11 2284.66 2285.74 2289.64
 2289.76 2292.95 2293.97 2296.59 2296.59  2298.5 2304.24 2306.33 2308.79 2312.04
 2313.92 2317.31 2324.19 2325.53 2325.12 2326.43 2328.19 2346.69 2348.31  2350.5
    2247    2247    2247    2247    2247    2247    2247    2247    2247    2247
    2247    2247    2247    2247    2247    2247    2247    2247    2247    2247
    2247    2247    2247    2247    2247    2247    2247    2247    2247    2247
    2247    2247    2247    2247    2247    2247    2247    2247    2247    2247
    2247    2247    2247    2247    2247    2247    2247    2247    2247    2247
    2247    2247    2247    2247    2247    2247    2247    2247    2247    2247
  4499.9  4511.2    4521    4538    4544  4559.8  4565.6  4575.8    4592  4602.6
  4613.2  4635.6  4642.2  4646.8  4655.4  4665.8  4688.4  4707.4  4724.5  4786.8
  4796.8  4880.9  4883.4  4898.3  4932.3  4936.4  4949.4  4952.9  4961.4  4973.4
  5034.2  5054.4  5122.3  5212.6  5221.3  5238.4  5245.8  5250.8  5257.9  5265.3
  5277.4  5299.8  5309.5  5322.3  5323.5  5334.5  5356.4  5367.2  5377.3  5386.3
  5393.8  5401.7    5423  5434.9  5439.9  5444.4  5447.9  5469.7  5472.4  5477.1
 2287.53 2287.57 2286.47 2286.32 2285.96 2286.44 2286.29 2285.38 2285.87 2285.52
 2285.62 2284.21 2284.03 2284.39 2283.63 2283.98 2283.42 2283.55 2282.45 2281.14
 2280.45 2279.81 2280.08 2279.78 2279.86 2280.33 2280.59 2280.04    2280    2281
    2281 2280.17 2280.44 2282.33 2282.76  2284.4 2284.11 2284.66 2285.74 2289.64
 2289.76 2292.95 2293.97 2296.59 2296.59  2298.5 2304.24 2306.33 2308.79 2312.04
 2313.92 2317.31 2324.19 2325.53 2325.12 2326.43 2328.19 2346.69 2348.31  2350.5
 2246.85 2246.85 2246.85 2246.85 2246.85 2246.85 2246.85 2246.85 2246.85 2246.85
 2246.85 2246.85 2246.85 2246.85 2246.85 2246.85 2246.85 2246.85 2246.85 2246.85
 2246.85 2246.85 2246.85 2246.85 2246.85 2246.85 2246.85 2246.85 2246.85 2246.85
 2246.85 2246.85 2246.85 2246.85 2246.85 2246.85 2246.85 2246.85 2246.85 2246.85
 2246.85 2246.85 2246.85 2246.85 2246.85 2246.85 2246.85 2246.85 2246.85 2246.85
 2246.85 2246.85 2246.85 2246.85 2246.85 2246.85 2246.85 2246.85 2246.85 2246.85
Culvert=1,6,,30,0.027,0.5,1,2,1,2273.9,4993,2272.7,4993,Culvert #1  , 0 ,30
Culvert Bottom n=0.027
Culvert=1,6,,30,0.027,0.5,1,2,1,2273.9,5000,2272.7,5000,Culvert #2  , 0 ,30
Culvert Bottom n=0.027
Culvert=1,6,,30,0.027,0.5,1,2,1,2273.9,5007,2272.7,5007,Culvert #3  , 0 ,30
Culvert Bottom n=0.027
BC Design=,, 0 ,, 0 ,,,,,,
BC HTab HWMax=2350.5

Type RM Length L Ch R = 1 ,790     ,246,246,246
BEGIN DESCRIPTION:
Willow_Crk_XS2
END DESCRIPTION:
XS GIS Cut Line= 6
       864451.13       717035.66       864719.92       717075.75
       864861.39       717075.75       865059.44       717045.09
       865240.99       717023.87       865439.04         716939.
#Sta/Elev= 30
  4489.1 2300.38  4516.7 2297.65  4524.5 2293.55  4537.5 2288.92  4558.7 2288.09
  4662.1 2289.44  4682.5 2288.39  4703.5  2289.3  4714.7 2288.17  4730.8 2284.14
    4750 2282.36  4802.1  2279.1  4966.7 2276.73  4992.8  2272.7  5007.2  2272.7
  5032.2 2276.88  5039.1  2278.2  5244.9 2282.55  5271.9 2283.73  5307.1 2286.87
  5375.1 2297.63  5384.5  2307.8    5400 2313.26  5408.1 2317.72  5418.8  2321.6
  5439.9 2322.64  5448.3  2322.1  5453.8 2325.23  5485.6 2351.35    5501 2361.49
#Mann= 5 ,-1 , 0
  4489.1      .1       0    4750     .05       0  4966.7     .05       0
  5032.2     .05       0    5400      .1       0
#XS Ineff= 2 , 0
       0    4940  2278.6    5040       0  2278.6
Permanent Ineff=
       F       F
Bank Sta=4966.7,5032.2
Exp/Cntr=0.5,0.3

Type RM Length L Ch R = 1 ,544     ,468,468,468
BEGIN DESCRIPTION:
Willow_Crk_XS37
END DESCRIPTION:
XS GIS Cut Line= 4
       864608.83       717445.11       864936.49       717397.05
       865118.45       717257.47       865488.59       717014.44
#Sta/Elev= 30
  4522.3 2338.49  4668.2 2327.61    4714 2321.11    4729  2311.9  4739.8 2307.41
  4755.4 2298.76  4791.2 2281.12  4808.9 2275.56  4866.7 2272.71  4973.5  2272.1
  4990.6  2271.2  4992.8 2269.08  5007.2 2269.08 5009.45  2270.3  5033.6 2273.49
  5126.1 2274.16  5264.8 2281.07  5307.8  2285.3  5335.3 2289.48  5389.5 2300.83
  5404.8 2305.92  5415.7 2306.75  5422.7 2308.66  5436.6 2316.04  5458.1 2314.58
  5467.1 2316.47  5490.7 2338.23  5495.4 2340.76  5503.5 2343.17  5525.6 2355.54
#Mann= 3 , 0 , 0
  4522.3     .08       0  4990.6     .05       0 5009.45     .06       0
Bank Sta=4990.6,5009.45
Exp/Cntr=0.3,0.1

Type RM Length L Ch R = 1 ,76      ,0,0,0
BEGIN DESCRIPTION:
Willow_Crk_XS1
END DESCRIPTION:
XS GIS Cut Line= 6
       864663.32       717566.53       864977.88       717640.21
       865199.52       717654.35       865430.58       717569.47
       865616.72       717370.76       865928.99       717231.98
#Sta/Elev= 30
  4312.8 2329.42  4369.6 2311.65  4417.8 2301.52    4450 2292.82  4472.4 2283.64
  4482.2 2283.13  4490.2 2280.96  4577.5 2273.88  4733.5 2269.25    4944 2266.52
  4970.5 2263.56  4992.8 2261.83  5031.4 2262.41  5036.8 2263.54  5064.3 2266.51
  5134.2 2265.68  5177.2 2268.03  5191.5 2269.68  5219.4 2279.11    5245 2284.53
  5353.6 2296.59    5468 2302.52  5480.1 2302.45  5507.4 2299.18  5526.1 2298.94
  5548.6 2308.43  5584.3 2310.55  5639.6 2311.68    5671 2321.35  5720.7 2331.69
#Mann= 4 ,-1 , 0
  4312.8      .1       0    4450     .05       0  4970.5     .05       0
  5036.8     .05       0
#XS Ineff= 2 , 0
       0                    5050       0
Permanent Ineff=
       F       T
Bank Sta=4970.5,5036.8
Exp/Cntr=0.3,0.1

Chan Stop Cuts=-1
Use User Specified Reach Order=0
User Specified Reach Order=Willow Creek    ,Reach-1