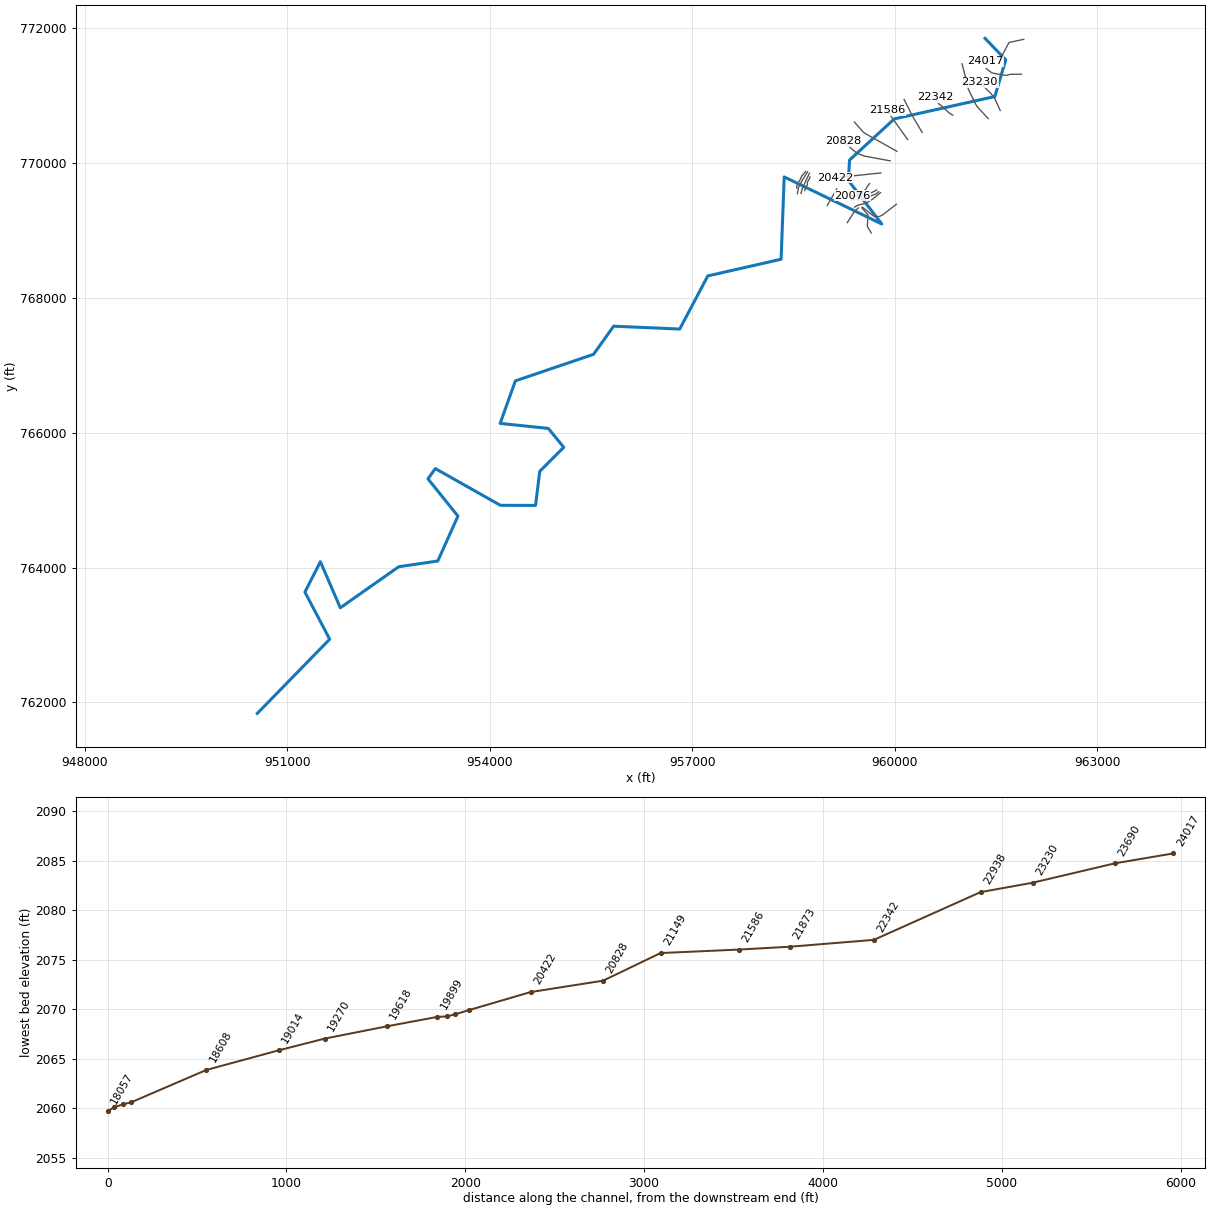
--- dtl_little_ivy_crk.prj (project) ---

Proj Title=dtl_Little_Ivy_Crk
Current Plan=p01
Default Exp/Contr=0.3,0.1
English Units
Geom File=g01
Flow File=f01
Plan File=p01
Y Axis Title=Elevation
X Axis Title(PF)=Main Channel Distance
X Axis Title(XS)=Station
BEGIN DESCRIPTION:
END DESCRIPTION:
DSS Export Rating Curves= 0
DSS Export Rating Curve Sorted= 0
DSS Export Volume Flow Curves= 0
DXF OffsetX= 0
DXF OffsetY= 0
DXF ScaleX= 1
DXF ScaleY= 10

--- dtl_little_ivy_crk.p01 (plan) ---

Plan Title=dtl_Little_Ivy_crk
Program Version=3.13
Short Identifier=all profiles
Geom File=g01
Flow File=f01
Subcritical Flow
K Sum by GR= 0
Std Step Tol= 0.01
Critical Tol= 0.01
Num of Std Step Trials= 20
Max Error Tol= 0.3
Flow Tol Ratio= 0.001
Split Flow NTrial= 30
Split Flow Tol= 0.02
Split Flow Ratio= 0.02
Log Output Level= 0
Friction Slope Method= 0
Unsteady Friction Slope Method= 2
Unsteady Bridges Friction Slope Method= 1
Parabolic Critical Depth
Global Vel Dist= 0 , 0 , 0
Global Log Level= 0
CheckData=True
Encroach Param=-1 ,0,0, 2
Encroach River=Little_Ivy_crk
Encroach Reach=reach one
Encroach Node=24017
       1   268.5  532.28
Encroach Node=23690
       1  160.25  376.57
Encroach Node=23230
       1   186.5  375.65
Encroach Node=22938
       1   253.4  329.17
Encroach Node=22342
       1  166.45     280
Encroach Node=21873
       1   188.7   434.3
Encroach Node=21586
       1     215  429.22
Encroach Node=21149
       1     350     501
Encroach Node=20828
       1     310  570.03
Encroach Node=20422
       1  251.56  570.96
Encroach Node=20076
       1   52.72     279
Encroach Node=20002
       1     110     214
Encroach Node=19956
       1  123.15  216.28
Encroach Node=19899
       1  139.04     302
Encroach Node=19618
       1     155     417
Encroach Node=19270
       1   113.8     242
Encroach Node=19014
       1   117.9     228
Encroach Node=18608
       1  133.45     206
Encroach Node=18188
       1    53.5   167.5
Encroach Node=18145
       1   113.5     208
Encroach Node=18092
       1  140.84   217.5
Encroach Node=18057
       1    73.8  158.26
Encroach Node=17825
       1     101     339
Encroach Node=17467
       1     143  326.25
Encroach Node=17113
       1   85.09  244.68
Encroach Node=16882
       1     113  208.85
Encroach Node=16610
       1  150.06     225
Encroach Node=16129
       1     230   367.1
Encroach Node=15610
       1  384.37   595.8
Encroach Node=15366
       1  283.28  504.54
Encroach Node=14994
       1   465.5  588.17
Encroach Node=14678
       1  423.51  533.38
Encroach Node=14614
       1  188.79  301.11
Encroach Node=14565
       1  176.85  248.56
Encroach Node=14522
       1   52.15     166
Encroach Node=14073
       1  240.84  399.08
Encroach Node=13540
       1  450.48     609
Encroach Node=13033
       1  185.87  305.42
Encroach Node=12491
       1  265.05     523
Encroach Node=11892
       1   283.4     756
Encroach Node=11454
       1     354   725.5
Encroach Node=10947
       1  496.52   921.4
Encroach Node=10333
       1  162.89     380
Encroach Node=10281
       1  143.84  262.69
Encroach Node=10244
       1  108.15   200.1
Encroach Node=10170
       1     135  292.59
Encroach Node=9944
       1  310.24  542.61
Encroach Node=9617
       1     551  869.97
Encroach Node=9270
       1  142.12  268.36
Encroach Node=8914
       1   263.9  339.13
Encroach Node=8862
       1   244.9   380.5
Encroach Node=8832
       1     264     396
Encroach Node=8799
       1   44.08  211.73
Encroach Node=8544
       1      74  195.48
Encroach Node=8494
       1    74.6   164.4
Encroach Node=8459
       1   89.07     178
Encroach Node=8407
       1   66.05   153.8
Encroach Node=8246
       1   45.08  126.62
Encroach Node=7886
       1   90.21  155.78
Encroach Node=7529
       1    60.8  146.83
Encroach Node=7462
       1   60.68     165
Encroach Node=7412
       1   76.96  146.89
Encroach Node=7371
       1      64  135.85
Encroach Node=7145
       1   54.25  143.89
Encroach Node=6776
       1      71     300
Encroach Node=6492
       1      84  275.54
Encroach Node=6185
       1     160  276.52
Encroach Node=5865
       1  181.18  285.01
Encroach Node=5445
       1  238.74  420.26
Encroach Node=5091
       1  193.75  346.76
Encroach Node=4647
       1   280.9   349.6
Encroach Node=4321
       1   119.9  194.15
Encroach Node=3969
       1     152  211.15
Encroach Node=3851
       1     116   196.6
Encroach Node=3742
       1   90.61     168
Encroach Node=3716
       1   98.09     184
Encroach Node=3355
       1  109.95     200
Encroach Node=2943
       1    77.3   169.5
Encroach Node=2482
       1   163.8     219
Encroach Node=2112
       4       1
Encroach Node=1879
       4       1
Encroach Node=1731
       1  202.35   285.6
Encroach Node=1622
       1   172.1  235.27
Encroach Node=1248
       1   160.9  241.07
Encroach Node=945
       1   169.4   267.7
Encroach Node=688
       1  175.98  338.76
Encroach Node=280
       1  110.56     348
Encroach Node=225
       1   227.6     415
Encroach Node=188
       1   220.8     422
Encroach Node=163
       1     239     401
Encroach Node=62
       1  156.97     351
Computation Interval=1HOUR
Output Interval=1HOUR
Run HTab= 0
Run UNet= 0
Run PostProcess= 0
UNET Theta= 1
UNET Theta Warmup= 1
UNET ZTol= 0.02
UNET ZSATol= 0.05
UNET MxIter= 20
UNET MaxInSteps= 0
UNET DtIC= 0
UNET DtMin= 0
UNET MaxCRTS= 20
UNET WFStab= 2
UNET SFStab= 1
UNET WFX= 1
UNET SFX= 1
UNET DSS MLevel= 4
UNET DZMax Abort= 100
UNET Convert EG Bridges=-1
UNET Use Existing IB Tables=-1
UNET Froude Reduction=False
UNET Froude Limit= 1
UNET Froude Power= 10
Instantaneous Interval=1HOUR
Write IC File= 0
Echo Input=False
Echo Output=False
Write Detailed= 0
Detailed Automatic Start=False, 10

--- dtl_little_ivy_crk.f01 (steady flow) ---

Flow Title=dtl_Little_Ivy_crk
Program Version=3.13
Number of Profiles= 5
Profile Names=100-YR,FW,10-YR,50-YR,500-YR
River Rch & RM=Little_Ivy_crk,reach one       ,24017
    7340    7340    3770    6150   10620
River Rch & RM=Little_Ivy_crk,reach one       ,19270
    7640    7640    3930    6400   11040
River Rch & RM=Little_Ivy_crk,reach one       ,18188
    7730    7730    3980    6490   11170
River Rch & RM=Little_Ivy_crk,reach one       ,12491
    7810    7810    4020    6550   11280
River Rch & RM=Little_Ivy_crk,reach one       ,6776
    8210    8210    4240    6890   11830
Boundary for River Rch & Prof#=Little_Ivy_crk,reach one       , 1
Up Type= 0
Dn Type= 3
Dn Slope=0.002
Boundary for River Rch & Prof#=Little_Ivy_crk,reach one       , 2
Up Type= 0
Dn Type= 3
Dn Slope=0.002
Boundary for River Rch & Prof#=Little_Ivy_crk,reach one       , 3
Up Type= 0
Dn Type= 3
Dn Slope=0.002
Boundary for River Rch & Prof#=Little_Ivy_crk,reach one       , 4
Up Type= 0
Dn Type= 3
Dn Slope=0.002
Boundary for River Rch & Prof#=Little_Ivy_crk,reach one       , 5
Up Type= 0
Dn Type= 3
Dn Slope=0.002
DSS Import GetInterval= 0
DSS Import GetPeak= 0
DSS Import FillOption= 0

--- dtl_little_ivy_crk.g01 (geometry) ---

Geom Title=dtl_Little_Ivy_crk
Program Version=3.13

River Reach=Little_Ivy_crk  ,reach one
Reach XY= 30
  961340.5365347  771847.0469994  961647.3282015  771527.6094993
  961485.5573681   770984.234499  959996.0365341  770652.3594989
  959333.1823671  770042.4844986  959315.1302837  769739.3594985
  959809.8594506  769094.3386648  958364.1927833  769791.8282485
  958318.4011166  768571.0990813  957232.3073661  768324.3907478
  956816.2240326  767536.0678308  955836.9740321  767578.5261641
  955538.8698653  767161.3490806  954380.5990314  766767.4949137
  954154.9427813  766137.1407468  954869.3906983  766062.2032467
  955097.5469484  765782.4219966  954741.9844483  765426.0261631
  954679.5365316  764920.5782462  954158.2761147  764922.2449129
  953194.8490309  765466.8282465  953085.3594475  765314.8907464
   953529.380281  764762.1407461  953230.7761142  764096.3490792
   952652.651114  764011.2761625  951786.3281969  763402.7657455
  951491.1927801  764085.9324125  951262.0261133   763635.411579
  951629.2136135   762936.619912  950556.7969463  761836.8386614

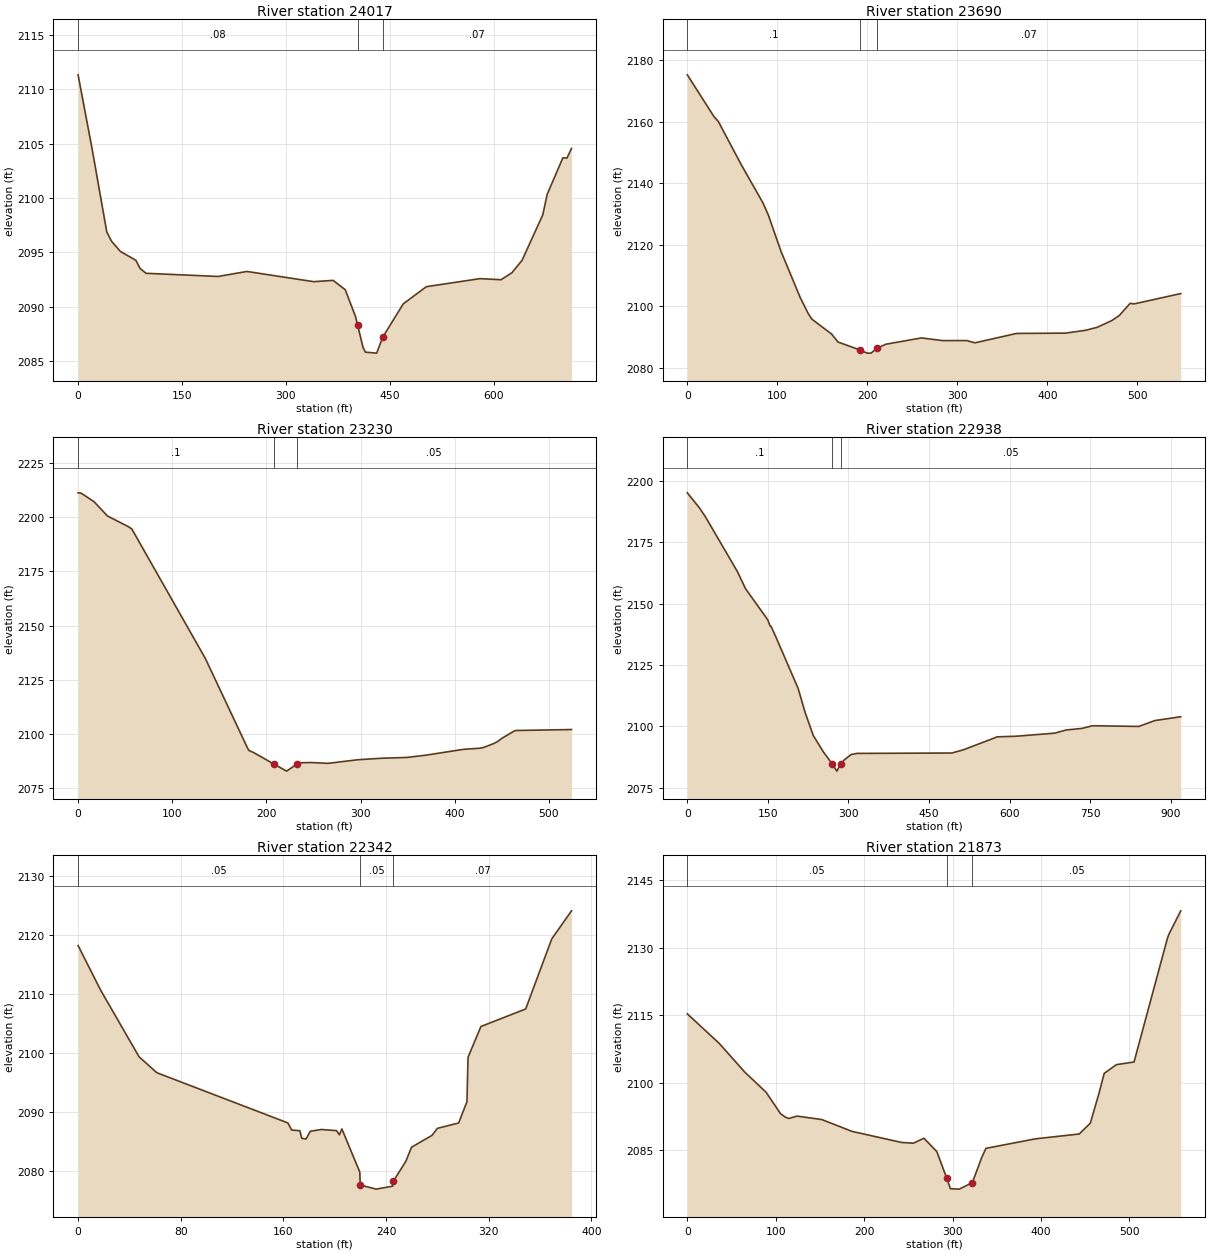
Type RM Length L Ch R = 1 ,24017   ,341.27,327.19,313.23
XS GIS Cut Line= 6
  961914.1779169  771832.2333804  961696.1877726  771785.3239403
  961590.5068764   771589.039524  961579.1691484   771577.701796
  961417.1979482  771516.1532519  961341.0717401  771504.8155239
#Sta/Elev= 30
       0 2111.32   19.95 2104.61   41.44 2096.87    48.3 2096.02   61.05 2095.08
   83.33 2094.27   89.55 2093.51   98.12 2093.07  202.12 2092.78  243.67 2093.24
  340.03  2092.3   368.1 2092.42  385.64 2091.56  400.53 2089.08  403.46 2088.31
  411.27 2086.26  414.72 2085.82  430.94 2085.73  439.74  2087.2  469.34 2090.26
  502.66 2091.84  580.24 2092.58  610.51 2092.48   626.1 2093.12   640.8 2094.26
  670.75 2098.45  677.12 2100.34  699.74 2103.69  705.56 2103.66  712.19 2104.55
#Mann= 3 ,-1 , 0
       0     .08       0  403.46    .055       0  439.74     .07       0
Bank Sta=403.46,439.74
Exp/Cntr=0.3,0.1

Type RM Length L Ch R = 1 ,23690   ,474.02,460.27,450.19
XS GIS Cut Line= 6
  961879.1284448  771314.9259877  961712.2891486  771313.4626917
  961658.1390045  771297.3633636  961535.2047324  771314.9259877
  961443.0047962  771333.9508837  961358.7859161  771398.6594918
#Sta/Elev= 30
       0  2175.2   29.57 2161.64   34.58 2159.97    59.9 2145.99   83.92 2133.63
   89.99 2129.63  103.98 2117.88  125.59 2102.68  134.49 2097.49  138.32 2095.78
  160.25 2090.94  167.42 2088.33  191.39  2085.8  199.79 2084.73  204.19 2084.73
  210.41 2086.31  220.67 2087.63  259.99 2089.67  283.87  2088.8  310.44 2088.81
  319.46 2088.08  365.71 2091.13  419.77 2091.23  441.87 2092.12  455.14 2093.11
  471.67 2095.34  479.93 2096.99  491.89 2100.93  496.27 2100.73  548.08 2104.09
#Mann= 3 ,-1 , 0
       0      .1       0  191.39    .055       0  210.41     .07       0
Bank Sta=191.39,210.41
Exp/Cntr=0.3,0.1

Type RM Length L Ch R = 1 ,23230   ,293.57,291.51,288.65
XS GIS Cut Line= 6
  961565.9390684  770776.3562589  961478.1290203  770968.0756832
  961422.5155802  771035.3965153  961347.8772441  771107.1082594
  961324.4604121  771134.9149794   961262.993788  771194.9183075
#Sta/Elev= 30
       0 2211.32    1.62 2211.34    3.99 2210.99   17.04  2207.2   31.15 2200.66
      54 2195.57   57.14 2194.59  135.22 2134.76  179.89 2093.49  181.29 2092.37
  186.51 2091.33  208.08 2086.01  221.43 2082.77  232.15 2085.93  234.38 2086.62
  247.85 2086.74  265.29 2086.36  297.06 2088.03  321.97 2088.72  349.17 2089.09
   369.4 2090.14  408.79 2092.81  427.06 2093.38  430.85 2093.74   441.6 2095.53
  446.48 2096.74  449.61  2097.8  463.38 2101.36  464.68 2101.54     524 2101.98
#Mann= 3 ,-1 , 0
       0      .1       0  208.08    .055       0  232.15     .05       0
Bank Sta=208.08,232.15
Exp/Cntr=0.3,0.1

Type RM Length L Ch R = 1 ,22938   ,591.46,596.72,603.22
XS GIS Cut Line= 6
  961387.3913562  770656.3496027  961217.6254679   770842.214819
  961194.2086359  770884.6555231  961094.6911957  771089.5466593
  961040.5410517  771311.9983717  960999.5636436  771468.5935719
#Sta/Elev= 30
       0 2195.08   22.13 2189.09   33.98 2185.24   93.03 2163.12  108.37 2156.08
  149.84 2143.39  154.23 2140.86  156.02  2140.7  164.44 2136.67  206.49 2115.41
  219.58 2105.56  234.63  2096.3  253.44 2089.63  269.23 2084.92  278.42 2081.82
  285.92 2084.82  291.86 2086.31  304.97 2088.57  315.84 2089.03  492.58 2089.19
  514.45 2090.52  577.31 2095.78  611.29 2096.01  684.07 2097.27  706.03 2098.59
  734.72 2099.19   754.7 2100.29  840.92 2100.01  870.76  2102.4  918.89 2103.96
#Mann= 3 ,-1 , 0
       0      .1       0  269.23    .055       0  285.92     .05       0
#Block Obstruct= 2 , 0
       0                     338       0    2100
Bank Sta=269.23,285.92
Exp/Cntr=0.3,0.1

Type RM Length L Ch R = 1 ,22342   ,477.12,468.82,454.72
XS GIS Cut Line= 6
  960862.7930834  770706.9055068  960806.3686353  770742.6676829
  960690.3002832   770850.800035  960665.1999951   770864.500131
  960623.3736911  770921.3874271  960605.1679951  770976.7950432
#Sta/Elev= 30
       0 2118.25   17.55 2110.71   47.53 2099.41   61.41 2096.71  163.49 2088.21
  166.45    2087  172.83  2086.9  174.33  2085.6  177.64  2085.5  180.95  2086.8
  189.63  2087.1  201.36 2086.91  203.63  2086.2  205.55  2087.2  219.51  2079.9
  219.86  2077.7  232.31    2077  245.08  2077.5  245.54  2078.3  255.38  2081.7
  259.84  2084.1  275.76  2086.1  280.07  2087.3  296.56  2088.2  303.02  2091.8
  303.86 2099.32  313.91 2104.54  348.79 2107.51   369.1 2119.37   384.5 2124.13
#Mann= 3 ,-1 , 0
       0     .05       0  219.86     .05       0  245.54     .07       0
Bank Sta=219.86,245.54
Exp/Cntr=0.3,0.1

Type RM Length L Ch R = 1 ,21873   ,284.04,287.26,287.8
XS GIS Cut Line= 5
  960408.7658188  770452.0790105  960279.9845066  770669.0994268
  960237.0574026  770746.6059869  960216.7862985  770794.3028829
  960140.4716744  770940.9693791
#Sta/Elev= 30
       0 2115.26   36.08  2108.7   65.01 2102.31   89.08 2097.84  105.43 2093.08
  110.89  2092.3   115.1 2092.01  124.07 2092.54  152.13 2091.77  186.29 2089.14
  242.43 2086.68  255.82 2086.52  267.64 2087.62  282.26 2084.64  293.23 2078.84
  297.63  2076.4  307.62 2076.31  322.42 2077.76  332.96 2083.31  337.75 2085.37
  393.91 2087.49   443.3 2088.56  455.83 2090.97  465.61 2097.56   471.5 2102.02
  485.26 2103.97  505.29 2104.56  542.82 2131.88  544.51 2132.85  558.12 2138.15
#Mann= 3 ,-1 , 0
       0     .05       0  293.23     .05       0  322.42     .05       0
Bank Sta=293.23,322.42
Exp/Cntr=0.3,0.1

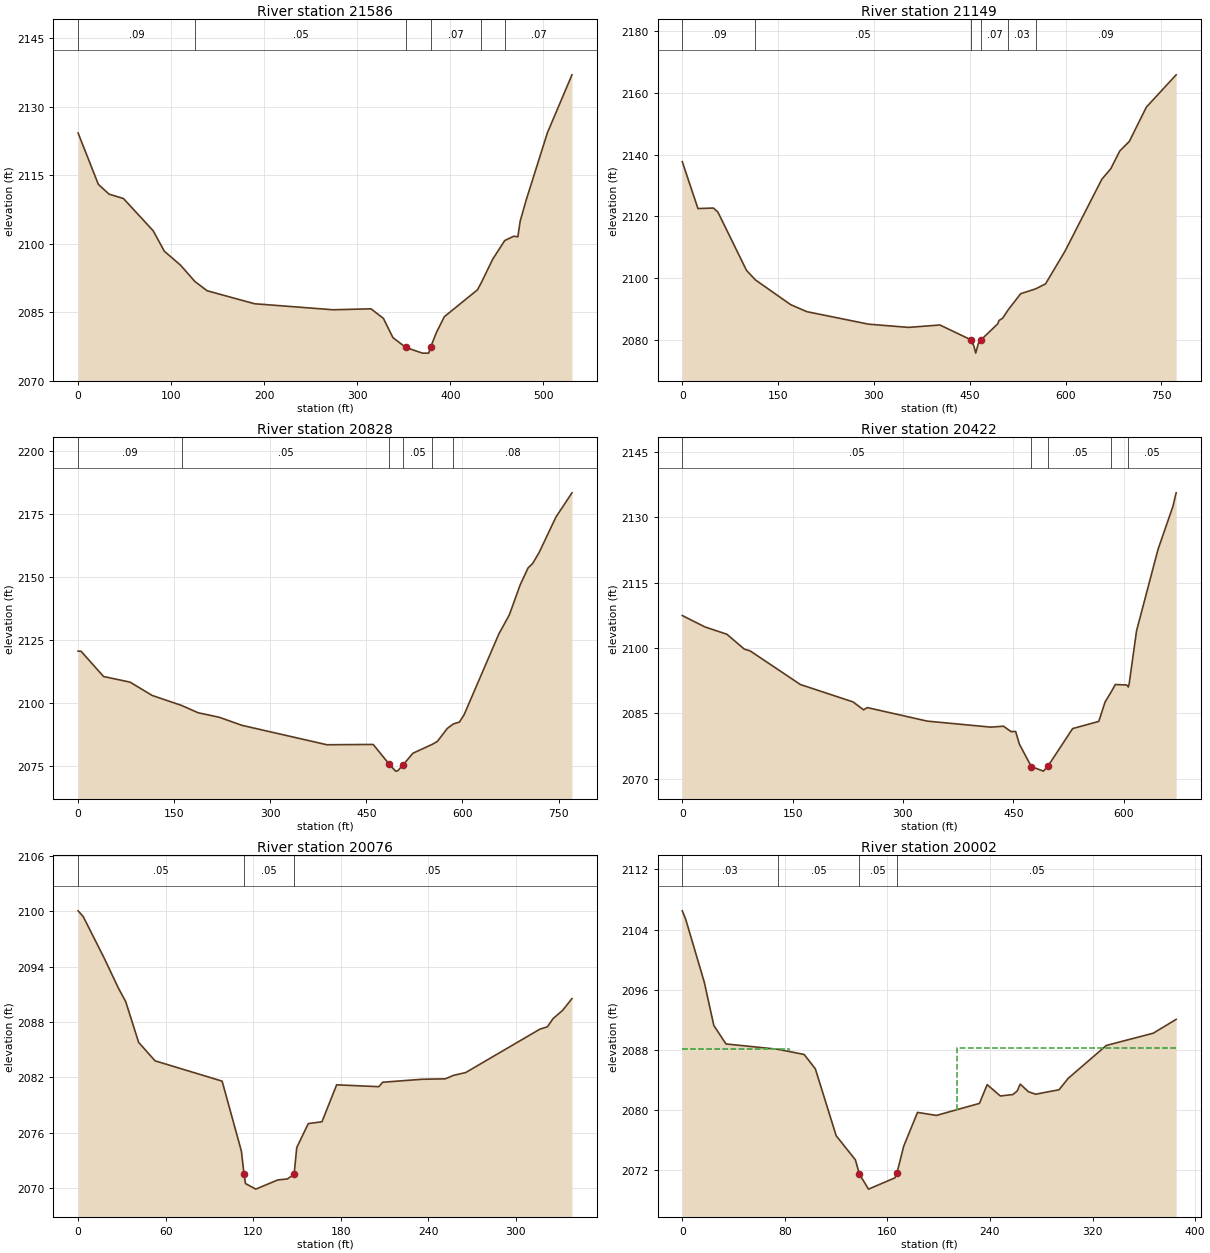
Type RM Length L Ch R = 1 ,21586   ,428.68,436.37,443.29
XS GIS Cut Line= 2
  960194.1302985  770345.9536983  959885.2949701  770777.6086109
#Sta/Elev= 30
       0 2124.25   21.76    2113    33.3 2110.85   48.73  2109.9   80.77 2102.81
   92.67 2098.35  110.17 2095.28  125.39 2091.74  138.61 2089.69  189.65 2086.84
  274.11 2085.52  314.76 2085.73  328.12 2083.63  338.38 2079.41  352.27 2077.26
  370.02 2076.02  376.79 2076.02  379.01  2077.4     385 2080.51  393.59    2084
  429.22  2089.9  433.46 2091.51  445.52 2096.58  458.51 2100.69  468.01 2101.62
  472.61 2101.52  475.12 2104.96  481.88 2109.78  504.34 2124.29  530.76    2137
#Mann= 6 ,-1 , 0
       0     .09       0  125.39     .05       0  352.27     .05       0
  379.01     .07       0  433.46     .03       0  458.51     .07       0
Bank Sta=352.27,379.01
Exp/Cntr=0.3,0.1

Type RM Length L Ch R = 1 ,21149   ,319.83,321.67,324.24
XS GIS Cut Line= 6
  960034.3463623  770171.8614101  959676.6222018  770372.1865303
  959577.8205376  770428.3959384  959557.0620096  770441.6065624
  959538.1896896  770454.8161625  959404.1992894  770605.7916507
#Sta/Elev= 30
       0 2137.71   24.54 2122.52   48.66 2122.69   55.68 2121.42  100.48 2102.51
  114.53 2099.39  169.62 2091.39  194.77 2089.12  291.77 2085.05  354.24 2084.01
  403.33 2084.79   451.7    2080  456.46 2078.03   459.4 2075.67  463.81 2079.03
  467.81    2080  493.77 2085.14  495.86 2086.25  501.38 2086.96  510.36 2089.75
  529.79 2094.93  553.11 2096.49  568.67 2098.11  599.23 2108.73  656.74 2131.99
  670.82 2135.42  684.84 2141.16  699.89 2144.29  726.53 2155.39  773.17 2165.86
#Mann= 6 ,-1 , 0
       0     .09       0  114.53     .05       0   451.7     .05       0
  467.81     .07       0  510.36     .03       0  553.11     .09       0
Bank Sta=451.7,467.81
Exp/Cntr=0.3,0.1

Type RM Length L Ch R = 1 ,20828   ,398.01,405.49,411.12
XS GIS Cut Line= 6
  959934.4991941  770030.1992019  959557.0620096   770100.025762
  959477.8003135   770128.333218  959426.8460734   770156.640674
  959375.8918333  770198.1587541  959245.6758972  770320.8267863
#Sta/Elev= 30
       0 2120.47    4.62 2120.42   39.76  2110.4   81.19 2108.16  115.63 2102.89
  161.51 2098.93   187.3 2096.04  220.53 2094.22  256.07 2091.02  388.45 2083.34
  460.65 2083.46  485.78 2075.62  495.56 2072.88  498.77 2072.95  507.85  2075.5
  522.65 2079.97  552.69 2083.48  560.75 2084.64  576.38 2089.82  586.01 2091.62
  595.25 2092.33  602.42 2095.15  656.93 2127.32  673.31 2134.91  690.01 2146.67
  702.47 2153.48  709.52 2155.19  719.74 2159.59  745.87  2173.6  770.98 2183.24
#Mann= 6 ,-1 , 0
       0     .09       0  161.51     .05       0  485.78     .05       0
  507.85     .05       0  552.69     .03       0  586.01     .08       0
Bank Sta=485.78,507.85
Exp/Cntr=0.3,0.1

Type RM Length L Ch R = 1 ,20422   ,342.49,346.34,355.4
XS GIS Cut Line= 2
  959795.8639299  769851.1016016   959128.110457  769780.7487055
#Sta/Elev= 30
       0 2107.46   30.58 2104.86   60.65 2103.16    84.4 2099.74   92.19 2099.35
  160.55 2091.62  232.25 2087.62   246.5  2085.8  251.56 2086.32  333.15 2083.21
  419.72 2081.83  436.66 2082.05  447.12  2080.8  453.24 2080.84  458.28 2077.94
  474.57 2072.77  490.96 2071.73  497.68 2073.01  530.68  2081.5  566.28 2083.15
  574.84 2087.61  583.28 2089.96  588.78 2091.62  604.28 2091.51  606.45 2091.05
  607.64 2091.87  617.62 2103.95  646.77 2122.62  667.16 2132.58  671.45 2135.64
#Mann= 5 ,-1 , 0
       0     .05       0  474.57     .05       0  497.68     .05       0
  583.28     .03       0  606.45     .05       0
Bank Sta=474.57,497.68
Exp/Cntr=0.3,0.1

Type RM Length L Ch R = 1 ,20076   ,75.97,73.51,61.68
XS GIS Cut Line= 6
  959628.7522497  769693.5827534  959596.5996737  769651.8004813
  959575.5001536  769611.0002253  959537.4995136  769578.2998092
  959503.7003455  769533.6001612  959373.1546813  769513.2594251
#Sta/Elev= 30
       0 2100.05    3.49 2099.43    17.8 2094.95   27.57 2091.69    32.6 2090.22
   41.48  2085.8   52.72  2083.8   98.67  2081.6   111.9    2074  113.69  2071.5
   114.7  2070.5  121.74  2069.9  136.87  2070.9  143.33    2071     148  2071.5
  149.79  2074.4  157.71    2077  167.08  2077.2  177.13  2081.2  206.03    2081
  208.68 2081.48   235.5  2081.8  251.64 2081.85  257.09 2082.22  265.56 2082.53
  316.26 2087.22  321.57 2087.49  325.38 2088.37  331.91 2089.26  338.36 2090.54
#Mann= 3 ,-1 , 0
       0     .05       0  113.69     .05       0     148     .05       0
Bank Sta=113.69,148
Exp/Cntr=0.5,0.3

Type RM Length L Ch R = 1 ,20002   ,46.26,45.96,48.97
XS GIS Cut Line= 6
  959734.7495618  769600.0106573  959706.2004418  769581.4004812
  959598.8002497  769532.4000332  959523.7000896  769509.8003531
  959457.2373695  769502.7163211  959370.6243773  769503.1412811
#Sta/Elev= 30
       0  2106.5     2.7 2105.36    17.1 2097.05   24.62 2091.25   34.09  2088.8
   74.35  2088.1   95.07  2087.4  103.78  2085.5  120.04  2076.6  135.02  2073.4
  138.14  2071.5  145.27  2069.5  165.88    2071  167.38  2071.6   172.7  2075.2
  183.48  2079.7  198.24  2079.3  231.79  2080.9  237.82 2083.39  248.14 2081.88
  257.97 2082.08  261.29 2082.56  263.59 2083.46  269.99 2082.45  275.61 2082.12
  293.84 2082.71  301.04 2084.23  330.73  2088.6  367.35 2090.23  385.22 2092.07
#Mann= 4 ,-1 , 0
       0     .03       0   74.35     .05       0  138.14     .05       0
  167.38     .05       0
#XS Ineff= 2 , 0
       0      83 2088.09     214       0 2088.29
Permanent Ineff=
       F       F
Bank Sta=138.14,167.38
Exp/Cntr=0.5,0.3

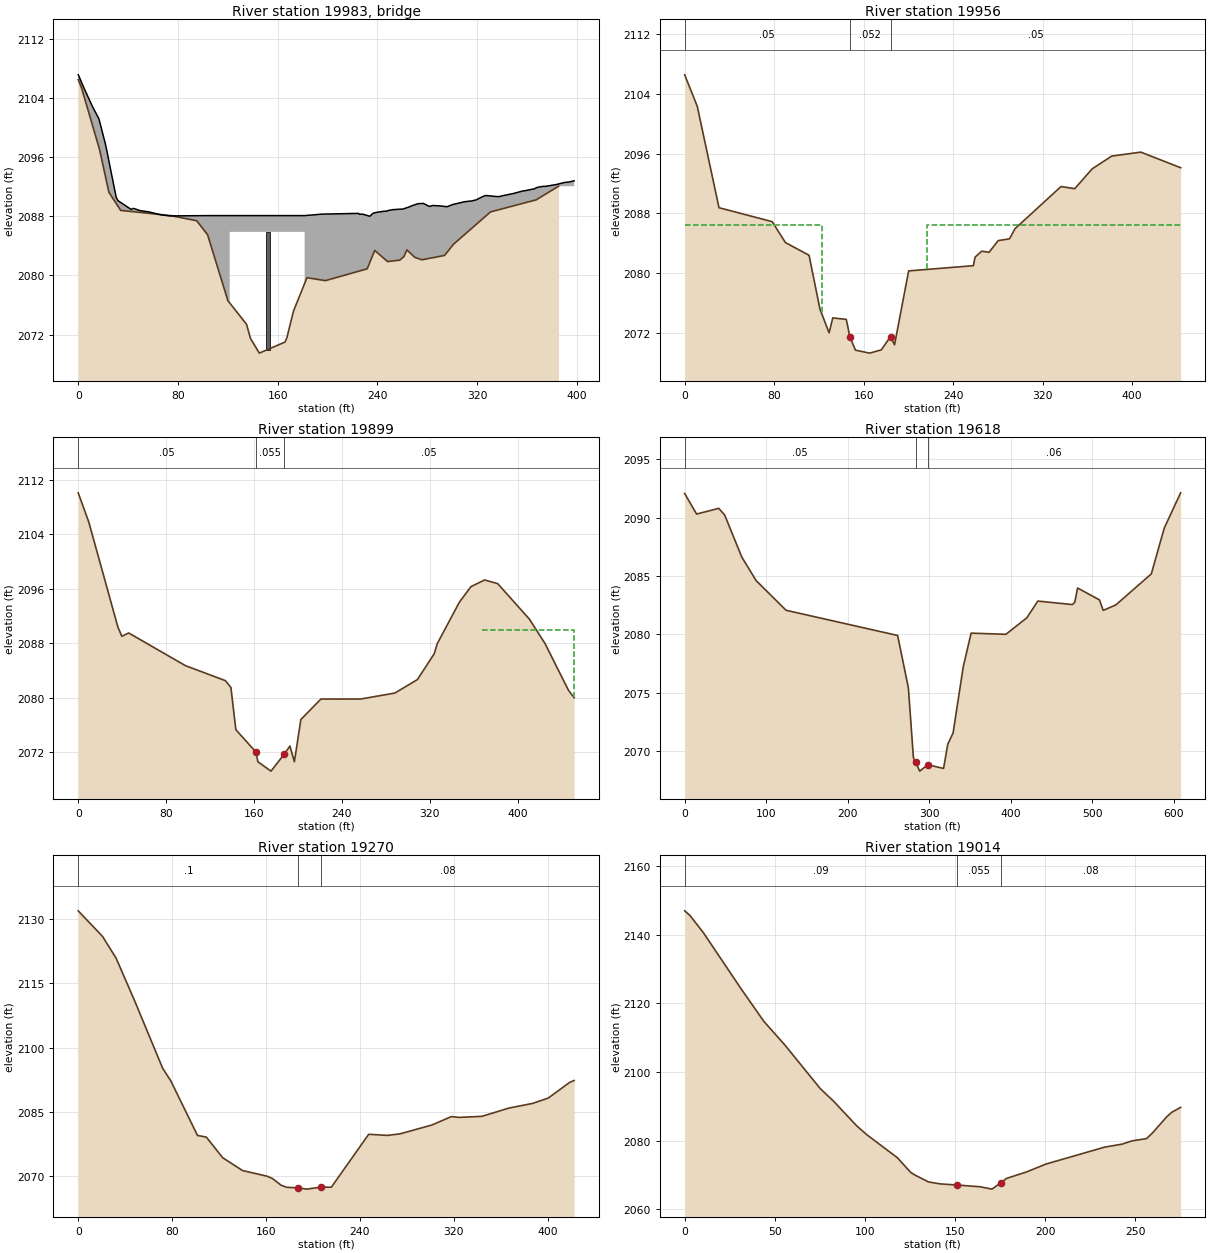
Type RM Length L Ch R = 3 ,19983   ,,,
Bridge Culvert--1,0,-1,-1, 0
Deck Dist Width WeirC Skew NumUp NumDn MinLoCord MaxHiCord MaxSubmerge Is_Ogee
18,19.3,2.6,0, 68, 61, , , 0.95, 0, 0,0,,
       0     .54    3.21    6.27   11.58   16.61   21.67   23.16   30.49   31.89
    42.5   44.08    45.9   49.23   50.58   57.31   60.04   66.11   73.31  105.34
   121.5   181.6  195.57  224.95  225.41  228.04   232.7  233.87  236.37  239.29
  245.77  247.37  248.53  252.67  260.55  260.81  266.06  266.92  272.51  276.82
  281.68  284.49  290.87  295.78   300.4  306.76  309.63  315.48  319.05   325.1
  327.19  335.29  337.82  339.53  348.57  357.06  358.76  366.25   367.4   368.3
  372.93   374.6  383.97  384.13  384.19  390.22   393.1  397.77
 2107.14 2106.97 2105.89 2104.74  2102.8 2101.19 2097.88 2096.71 2090.55 2090.12
 2088.93 2089.08 2088.99 2088.79 2088.75 2088.58 2088.46 2088.21 2088.06  2088.1
  2088.1  2088.1  2088.3  2088.4 2088.28  2088.3 2088.07 2088.01 2088.41 2088.54
  2088.7 2088.69 2088.79 2088.91 2088.99 2089.01 2089.31 2089.39 2089.71 2089.75
 2089.34 2089.47  2089.4  2089.3  2089.6 2089.85 2089.97 2090.08 2090.22 2090.73
 2090.82 2090.68 2090.67 2090.76 2091.07 2091.45 2091.48 2091.74 2091.87 2091.92
 2092.06 2092.05 2092.32 2092.32 2092.33 2092.59 2092.63  2092.8
                                                                                
                                                                                
  2085.9  2085.9
                                                                                
                                                                                
                                                                                
                                                                
       0     .54    3.21    6.27   11.58   16.61   21.67   23.16   30.49   31.89
    42.5   44.08    45.9   49.23   50.58   57.31   60.04   66.11   73.31  120.43
   134.5   194.6  211.12  245.98  247.37  248.53  252.67  260.55  260.81  266.06
  266.92  272.51  276.82  281.68  284.49  290.87  295.78   300.4  306.76  309.63
  315.48  319.05   325.1  327.19  335.29  337.82  339.53  348.57  357.06  358.76
  366.25   367.4   368.3  372.93   374.6  383.97  384.13  384.19  390.22   393.1
  397.77
 2107.14 2106.97 2105.89 2104.74  2102.8 2101.19 2097.88 2096.71 2090.55 2090.12
 2088.93 2089.08 2088.99 2088.79 2088.75 2088.58 2088.46 2088.21 2088.06  2088.1
  2088.1  2088.1  2088.3  2088.4 2088.69 2088.79 2088.91 2088.99 2089.01 2089.31
 2089.39 2089.71 2089.75 2089.34 2089.47  2089.4  2089.3  2089.6 2089.85 2089.97
 2090.08 2090.22 2090.73 2090.82 2090.68 2090.67 2090.76 2091.07 2091.45 2091.48
 2091.74 2091.87 2091.92 2092.06 2092.05 2092.32 2092.32 2092.33 2092.59 2092.63
  2092.8
                                                                                
                                                                                
  2085.9  2085.9
                                                                                
                                                                                
                                                                                
        
Pier Skew, UpSta & Num, DnSta & Num=  ,152, 6 ,165, 6 , 5 , 5 , 0 ,,
     3.2     3.2     2.8     1.5       2       2
    2069    2071    2071    2085  2085.1  2085.9
     3.2     3.2     2.8     1.5       2       2
    2069    2071    2071    2085  2085.1  2085.9
BR Coef=-1 , 0 , 0 ,, 0 ,,,0.8,0,,0,
WSPro=,,,, 1 ,,,, 0 ,,,, 0 ,,,,-1 ,-1 ,-1 , 0 , 0 , 0 , 0 , 0
BC Design=,, 0 ,, 0 ,,,,,,

Type RM Length L Ch R = 1 ,19956   ,53.56,57.14,59.63
XS GIS Cut Line= 6
  959763.7768899  769573.2432972  959726.0005058  769540.7999052
  959649.8998977  769510.4004171  959639.0004417  769501.1004491
  959540.4005056  769453.6994891  959355.0862013  769452.5515851
#Sta/Elev= 30
       0 2106.58   11.26 2102.36   30.68 2088.77   78.26  2086.9   90.06  2084.1
  111.21  2082.4  120.92  2075.2  129.12    2072   132.4    2074  144.51  2073.8
  147.66  2071.5  152.68 2069.68  165.38 2069.28  175.82 2069.72  184.02  2071.5
  187.65  2070.4  200.25  2080.3  258.11    2081  259.66 2082.14  265.54 2082.94
  272.19  2082.8  280.29 2084.36  290.48  2084.6   295.3 2085.95   336.5 2091.61
  348.76 2091.32  364.35 2093.98  381.83 2095.69  407.81 2096.22  443.41 2094.13
#Mann= 3 ,-1 , 0
       0     .05       0  147.66    .052       0  184.02     .05       0
#XS Ineff= 2 , 0
       0  123.15  2086.4  216.28       0  2086.4
Permanent Ineff=
       F       F
Bank Sta=147.66,184.02
Exp/Cntr=0.5,0.3

Type RM Length L Ch R = 1 ,19899   ,283.64,281.5,273.53
XS GIS Cut Line= 6
  959792.6803139  769559.5882572  959664.3997378  769453.9995211
  959640.2998977   769445.099937  959590.9000896   769405.499809
  959453.7475775  769371.0002249  959407.3972414  769345.0438729
#Sta/Elev= 30
       0 2110.07    9.61 2105.79   36.14 2090.36   39.74 2089.01   45.96  2089.5
   97.54 2084.71  134.04  2082.5  139.04  2081.5  143.55  2075.3  161.93    2072
  163.56  2070.6  175.55 2069.22  187.44 2071.68  192.77  2072.9  196.84  2070.6
  202.75  2076.8  220.99  2079.8  257.03  2079.8  288.35 2080.68  308.86 2082.66
  324.09 2086.43  326.94 2087.93  347.11 2094.03   357.6  2096.3  370.03 2097.28
  381.98 2096.74  411.02 2091.49  425.19 2087.91   446.3 2081.12  451.57 2079.99
#Mann= 3 ,-1 , 0
       0     .05       0  161.93    .055       0  187.44     .05       0
#XS Ineff= 2 , 0
       0                  367.58       0    2090
Permanent Ineff=
       F       F
Bank Sta=161.93,187.44
Exp/Cntr=0.3,0.1

Type RM Length L Ch R = 1 ,19618   ,376.85,347.18,301.02
XS GIS Cut Line= 6
  960025.4887623   769385.372065   959826.504058  769231.3501768
  959779.6273859  769206.4772167  959745.1882179  769203.6069447
  959693.5284418  769208.3900487  959522.7068096  769342.9876809
#Sta/Elev= 30
       0 2092.07   14.64 2090.31   41.86  2090.8   49.08 2090.23   70.06 2086.63
   87.76  2084.6  124.47 2082.06  261.39  2079.9  274.58 2075.41  280.75 2069.43
  283.36 2069.02  288.57 2068.27  298.38 2068.82  317.76  2068.5  322.89 2070.57
  329.44 2071.54  341.93 2077.22  351.57  2080.1  394.26    2080  420.03 2081.42
  433.45 2082.85  475.88 2082.55  478.86 2082.76  482.23 2083.97  509.15 2082.95
  513.67 2082.05   529.2 2082.52  572.76 2085.18   588.6  2089.1  608.72 2092.13
#Mann= 3 , 0 , 0
       0     .05       0  283.36     .05       0  298.38     .06       0
Bank Sta=283.36,298.38
Exp/Cntr=0.3,0.1

Type RM Length L Ch R = 1 ,19270   ,263.4,256.85,244.53
XS GIS Cut Line= 6
  959655.2625857  768961.5722564  959600.7325377  769047.6712005
  959596.9058497  769081.1549765  959603.6028097  769186.3873607
  959607.9875777  769225.8523207  959515.4937535  769333.3702729
#Sta/Elev= 30
       0 2131.83   20.74 2125.87   32.32 2120.79   48.12 2110.86   71.97 2095.16
   78.83 2092.27  101.66 2079.52  109.17 2079.15  123.07 2074.35  140.01 2071.36
  161.07 2070.03  165.58 2069.49  172.98 2067.93  177.87 2067.45  187.57 2067.32
  194.81 2067.03  206.91 2067.49  215.71 2067.48  247.55  2079.8  263.53 2079.54
  274.28  2079.9   301.6 2081.98  318.01 2083.93  324.56 2083.73  344.09 2083.98
  366.82 2085.89  387.36    2087  400.54 2088.23  418.62 2091.86   422.6 2092.32
#Mann= 3 , 0 , 0
       0      .1       0  187.57    .055       0  206.91     .08       0
Bank Sta=187.57,206.91
Exp/Cntr=0.3,0.1

Type RM Length L Ch R = 1 ,19014   ,405.52,405.88,408.11
XS GIS Cut Line= 3
  959299.3846972  769114.6377286  959406.5309374  769280.1396808
  959463.9302335  769332.7558729
#Sta/Elev= 30
       0 2146.92    2.97 2145.54   10.42 2140.52   30.84 2124.55   43.88 2114.74
   55.69 2107.76   75.11 2095.18   82.49 2091.51   95.48 2084.24  100.98 2081.71
  117.99 2074.99  125.33 2070.73  127.56 2069.99  135.16 2067.96  141.55 2067.38
  151.03 2067.05  163.91 2066.53  170.42 2065.85   175.3 2067.69  178.48 2068.97
  189.33 2070.81  200.53 2073.18  232.92 2078.09  242.54 2078.95  248.06 2079.91
  256.09 2080.56  259.41 2082.21  267.34 2086.92  270.09 2088.22  275.03 2089.67
#Mann= 3 , 0 , 0
       0     .09       0  151.03    .055       0   175.3     .08       0
Bank Sta=151.03,175.3
Exp/Cntr=0.3,0.1

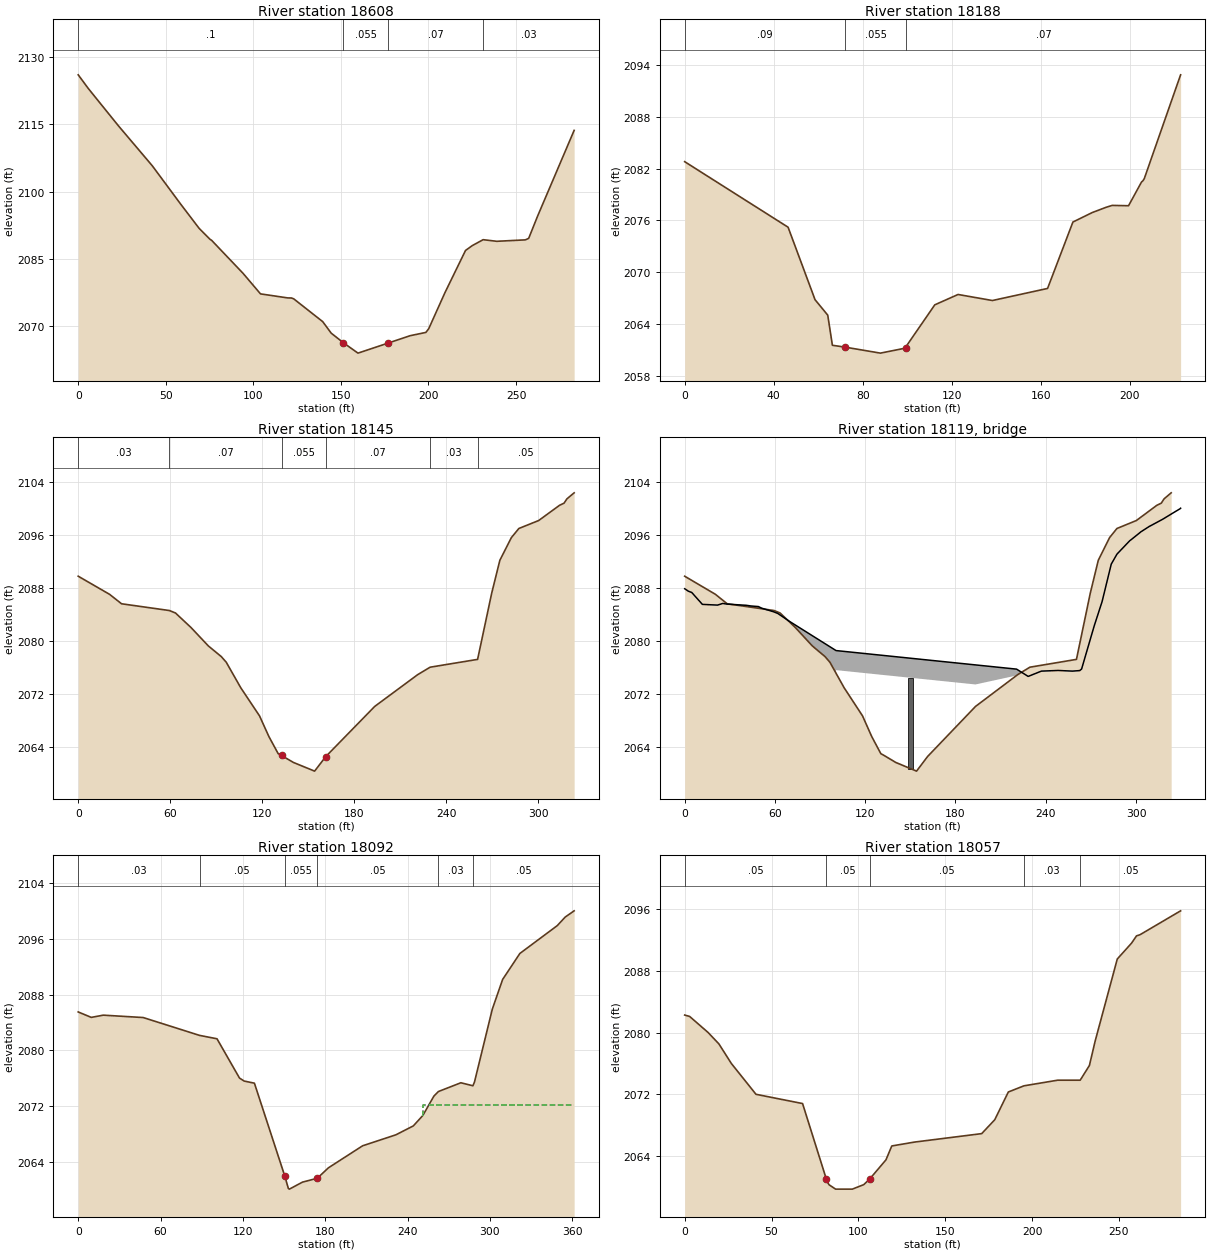
Type RM Length L Ch R = 1 ,18608   ,423.58,419.46,424.62
XS GIS Cut Line= 3
  959001.5973048  769367.3936969  959075.4860729  769495.8606411
   959142.315385  769613.1393613
#Sta/Elev= 30
       0  2126.1    5.81 2123.02   23.02 2114.67   42.32 2105.75   58.42 2097.23
   69.06 2091.76   75.28 2089.31   76.15  2089.1   94.19 2081.68  104.09 2077.11
  119.61 2076.21  121.77 2076.19  123.07    2076  139.65 2070.89  144.43 2068.34
  151.48 2066.16  159.76 2063.86  176.91  2066.1  189.55 2067.76  198.52 2068.49
  200.16 2069.33  209.43  2077.4  221.16 2086.82  225.06 2087.92  231.22 2089.23
  239.02 2088.87  255.34 2089.19  257.23 2089.53  262.36 2094.54  283.19 2113.68
#Mann= 4 ,-1 , 0
       0      .1       0  151.48    .055       0  176.91     .07       0
  231.22     .03       0
Bank Sta=151.48,176.91
Exp/Cntr=0.3,0.1

Type RM Length L Ch R = 1 ,18188   ,39.97,42.92,39
XS GIS Cut Line= 6
  958669.4004404  769589.0999373  958680.8999604  769634.0996173
  958708.4998324  769677.6001614  958708.4005044  769715.8004814
  958732.5003444  769753.0996815  958748.1634485  769789.5663695
#Sta/Elev= 23
       0  2082.8   46.45  2075.2   58.55  2066.8   64.27    2065   66.35 2061.51
   71.93  2061.3   87.93  2060.6   99.54  2061.2   99.54  2061.4  112.35  2066.2
   122.8  2067.4  138.23  2066.7  163.01  2068.1  174.39  2075.8  183.08  2076.9
   189.3 2077.51  192.04 2077.73  199.38 2077.69  205.21 2080.44  205.87 2080.59
  206.46 2080.84  220.26 2091.03  222.77 2092.87
#Mann= 3 ,-1 , 0
       0     .09       0   71.93    .055       0   99.54     .07       0
Bank Sta=71.93,99.54
Exp/Cntr=0.5,0.3

Type RM Length L Ch R = 1 ,18145   ,55.1,53.63,52.12
XS GIS Cut Line= 4
  958613.6272563  769547.4804812  958629.4122163  769609.6280653
  958674.6033844  769712.5318734  958738.3054005  769844.8367696
#Sta/Elev= 30
       0 2089.82   20.41 2087.09   28.26 2085.66   59.46 2084.64   63.42 2084.27
   73.53 2082.08   84.89 2079.29   93.24  2077.7   96.52 2076.84  105.98 2072.99
  118.23 2068.74  124.32 2065.63  130.37 2063.05  132.57 2062.77  140.31 2061.72
  154.13 2060.41  161.43 2062.61  193.31 2070.17  221.36 2074.97  229.44 2076.09
   260.4 2077.27  269.58 2087.25  274.91 2092.22  282.41 2095.64  287.31 2097.02
  300.21 2098.22  313.84 2100.52  316.77 2100.84  318.64 2101.49  323.35  2102.4
#Mann= 6 ,-1 , 0
       0     .03       0   59.46     .07       0  132.57    .055       0
  161.43     .07       0  229.44     .03       0   260.4     .05       0
#XS Ineff= 2 , 0
       0    67.3  2078.5   230.4       0  2075.8
Permanent Ineff=
       F       F
Bank Sta=132.57,161.43
Exp/Cntr=0.5,0.3

Type RM Length L Ch R = 3 ,18119   ,,,
Bridge Culvert--1,0,-1,-1, 0
Deck Dist Width WeirC Skew NumUp NumDn MinLoCord MaxHiCord MaxSubmerge Is_Ogee
19.6,11.6,2.6,0, 39, 32, , , 0.95, 0, 0,0,,
       0    2.44    4.72   11.76   21.82   25.33   28.09   41.02   41.91   43.96
   48.96   51.15   58.96   59.13    61.9    69.7   100.6   220.6   228.3   237.1
   248.2   257.7  262.55  262.59  263.82  272.18  277.45  283.52  287.32  295.89
   296.8  297.47  303.25  308.66   314.9  317.76  325.88  329.21  329.63
 2087.93 2087.56 2087.36 2085.57 2085.46 2085.71 2085.61 2085.43  2085.4 2085.33
 2085.24    2085 2084.46 2084.45  2084.2    2083  2078.6  2075.8  2074.7  2075.5
  2075.6  2075.5 2075.58 2075.58 2075.82 2082.31    2086 2091.64 2093.15 2095.19
 2095.34 2095.46 2096.52 2097.31 2098.07 2098.42 2099.54 2099.99 2100.08
                                                                                
                                                 2075.65 2072.85
                                                                                
                                                                        
       0    2.44    4.72   11.76   21.82   25.33   28.09   41.02   41.91   43.96
   48.96   51.15   58.96   59.13    66.9    81.5     120     240   256.4   266.9
   278.8   287.7  295.89   296.8  297.47  303.25  308.66   314.9  317.76  325.88
  329.21  329.63
 2087.93 2087.56 2087.36 2085.57 2085.46 2085.71 2085.61 2085.43  2085.4 2085.33
 2085.24    2085 2084.46 2084.45  2084.2    2083  2078.6  2075.8  2074.7  2075.5
  2075.6  2075.5 2095.19 2095.34 2095.46 2096.52 2097.31 2098.07 2098.42 2099.54
 2099.99 2100.08
                                                                                
                                                 2075.65 2072.85
                                                                                
                
Pier Skew, UpSta & Num, DnSta & Num=  ,150, 2 ,165, 2 , 0 , 0 , 0 ,,
     3.5     3.5
    2073 2075.65
     3.5     3.5
    2073 2075.65
BR Coef=-1 , 0 , 0 ,, 0 ,,,0.8,0,,0,
WSPro=,,,, 1 ,,,, 0 ,,,, 0 ,,,,-1 ,-1 ,-1 , 0 , 0 , 0 , 0 , 0
BC Design=,, 0 ,, 0 ,,,,,,

Type RM Length L Ch R = 1 ,18092   ,37.51,34.8,34.51
XS GIS Cut Line= 4
  958560.1242802  769543.8841932  958574.7470002  769631.0480973
  958628.5029043  769734.7967055  958710.7495604  769867.5736656
#Sta/Elev= 30
       0 2085.51    9.54 2084.73   18.26 2085.05   47.33 2084.71   88.39 2082.15
  101.15 2081.66  117.53 2076.03  120.87  2075.6  128.41 2075.29  150.43 2062.03
  153.14 2060.19  153.89 2060.09  163.39 2061.09  174.23 2061.65  182.36 2063.15
  207.29 2066.31  231.48 2067.88  244.21 2069.16  251.13 2070.65  259.19 2073.43
  262.47 2074.09  278.87 2075.35  287.63 2074.92  288.78 2075.45  301.79 2085.92
  309.29 2090.17  321.85  2093.9  349.13  2097.9  354.94 2099.13  361.42 2100.02
#Mann= 6 ,-1 , 0
       0     .03       0   88.39     .05       0  150.43    .055       0
  174.23     .05       0  262.47     .03       0  287.63     .05       0
#XS Ineff= 2 , 0
       0  104.15 2077.24     251       0  2072.1
Permanent Ineff=
       F       F
Bank Sta=150.43,174.23
Exp/Cntr=0.5,0.3

Type RM Length L Ch R = 1 ,18057   ,221.62,231.48,240.09
XS GIS Cut Line= 6
  958551.0946482  769628.8976973  958548.9995442  769655.6998733
  958569.3003442  769703.9999054  958598.4003763  769746.3996495
  958624.5000883  769803.6996176  958681.9024564  769873.2896336
#Sta/Elev= 30
       0 2082.28    2.85  2082.1   13.43 2080.03    19.7 2078.54   26.87    2076
   41.06    2072   67.88  2070.8   81.62 2060.96   82.22 2060.58   83.17 2060.26
    86.9  2059.7   96.52  2059.7  103.09 2060.28  106.44 2060.99  115.91  2063.5
  119.25  2065.3  132.24  2065.8  171.02  2066.9  178.53  2068.7  186.35  2072.3
  195.35  2073.1  214.75 2073.83  227.73 2073.83  233.04 2075.74  236.35 2078.91
  249.08 2089.55  257.31 2091.61  260.15 2092.55  262.16  2092.7  285.55  2095.8
#Mann= 5 ,-1 , 0
       0     .05       0   81.62     .05       0  106.44     .05       0
  195.35     .03       0  227.73     .05       0
Bank Sta=81.62,106.44
Exp/Cntr=0.3,0.1