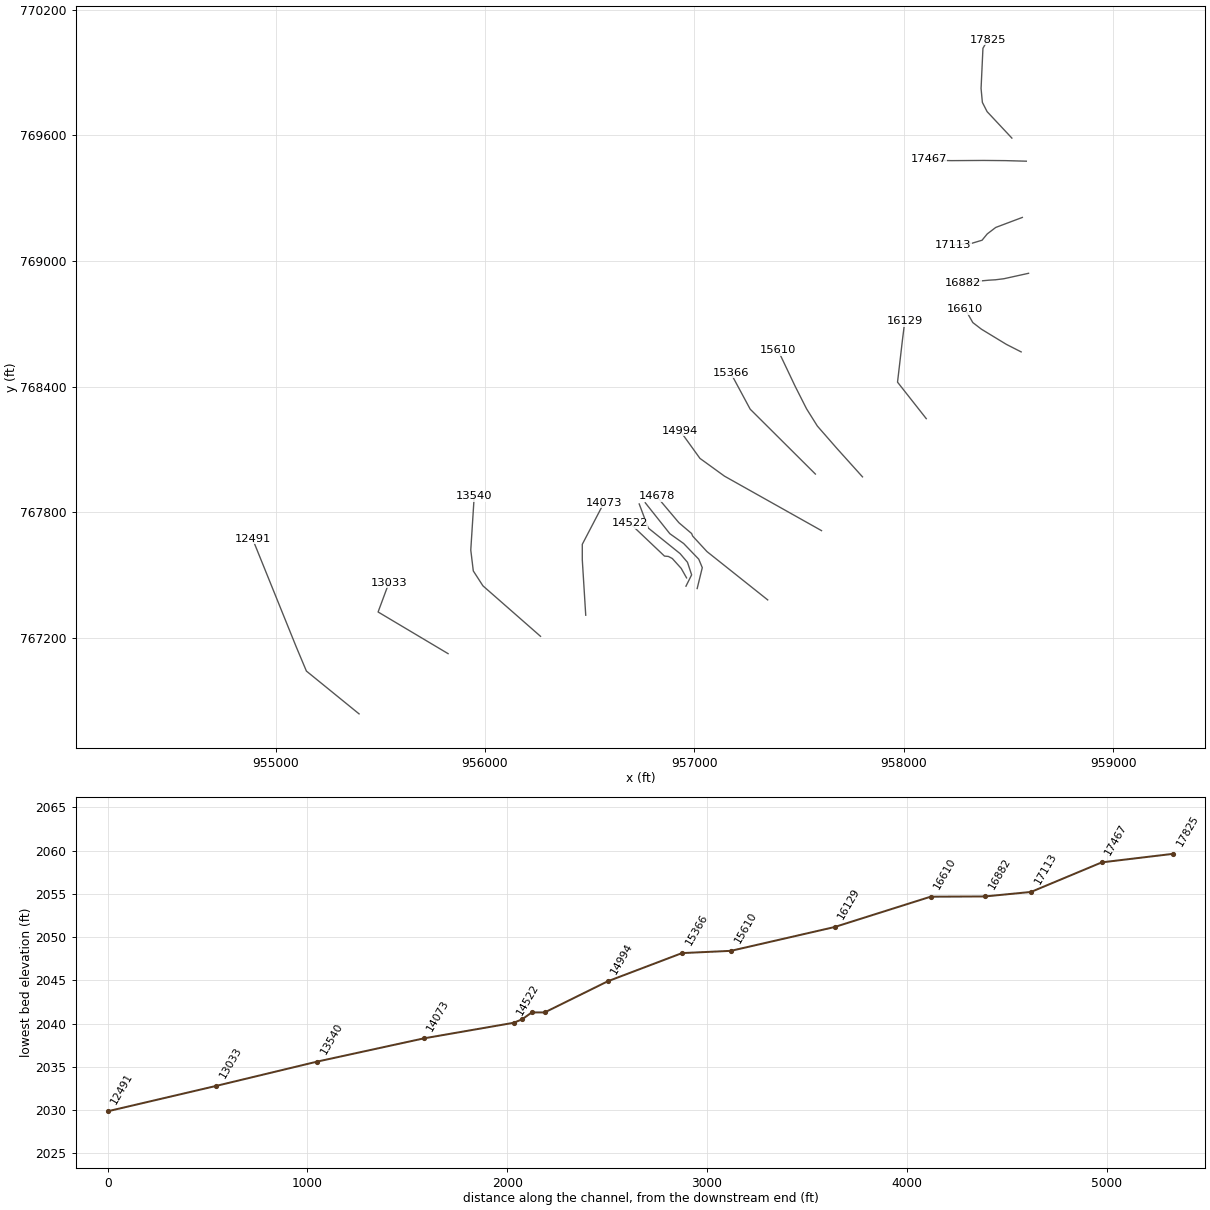
HEC-RAS study dtl_little_ivy_crk.prj: dtl_Little_Ivy_Crk

--- dtl_little_ivy_crk.g01 (geometry) --- (continued)

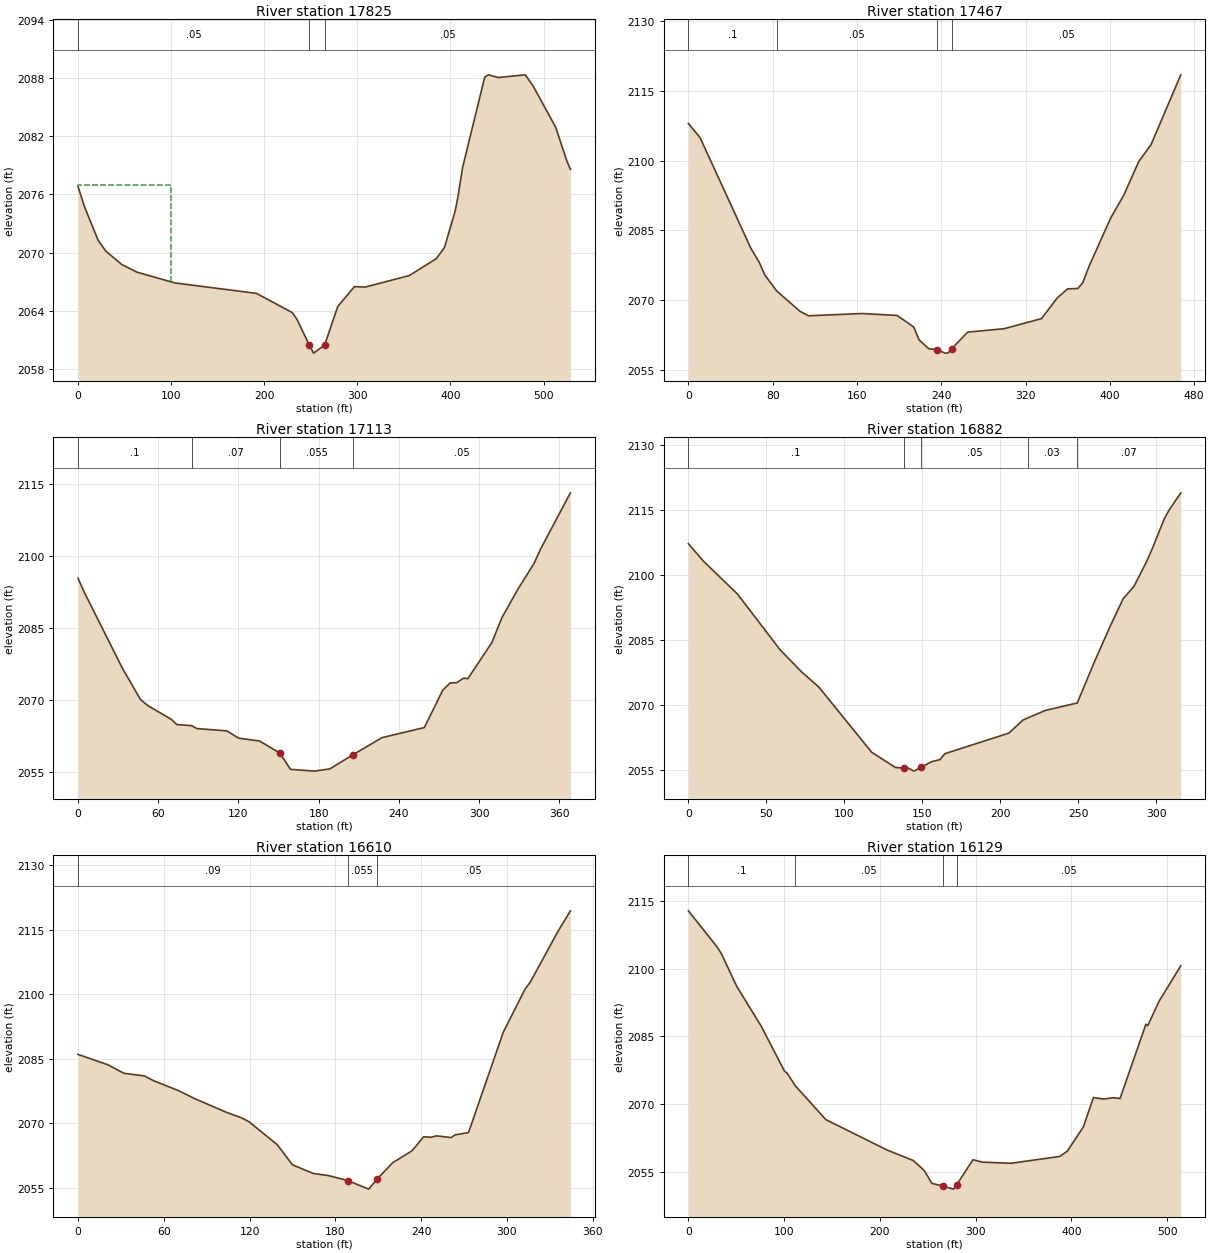
Type RM Length L Ch R = 1 ,17825   ,328.98,358.55,383.46
XS GIS Cut Line= 6
  958515.7656241  769586.4477772   958397.388152  769712.8964174
  958374.9676719  769756.8403535  958368.6905519  769823.2027216
   958377.658744  770015.1177298   958400.975224  770056.3705939
#Sta/Elev= 30
       0 2076.82    7.05 2074.71   21.54 2071.29   29.74 2070.17   46.92 2068.78
   63.31 2067.99  104.02 2066.88   191.7  2065.8  230.14 2063.82   235.1 2063.14
  248.19 2060.51  253.01 2059.64  264.85 2060.47  278.97 2064.45  296.91  2066.5
  308.39 2066.45  355.79 2067.64  384.75 2069.38  393.58 2070.53  405.06 2074.29
  407.73 2075.59  413.11 2078.81  436.82  2088.1  440.87 2088.34  451.19 2088.06
  480.36 2088.34  488.97 2087.16  513.08 2082.92   525.2 2079.41  528.86  2078.6
#Mann= 3 , 0 , 0
       0     .05       0  248.19     .05       0  264.85     .05       0
#XS Ineff= 2 , 0
       0     100    2077               0
Permanent Ineff=
       F       F
Bank Sta=248.19,264.85
Exp/Cntr=0.3,0.1

Type RM Length L Ch R = 1 ,17467   ,338.78,354.3,367.38
XS GIS Cut Line= 6
  958584.8190642  769476.1414731  958485.2739761  769478.8325451
   958381.245816  769479.7295691  958228.7896237  769478.8325451
  958162.4272557  769479.7295691  958118.4843436  769488.6967371
#Sta/Elev= 30
       0 2107.98   11.05 2104.95   59.23  2081.2   67.43 2078.05   72.57 2075.41
   84.01 2071.95  105.98 2067.62  113.96 2066.67  164.56 2067.16  198.07 2066.74
   213.8 2064.27  218.96 2061.47  228.14 2059.59  235.98  2059.4  243.46 2058.65
  246.32 2058.65  250.02 2059.62  265.01 2063.16  299.78  2063.9  335.14 2066.07
  349.88 2070.47  359.84 2072.45  369.62 2072.54  374.37 2073.81  380.32 2077.35
  400.59 2087.59  413.26 2092.63  427.49 2099.85  439.09 2103.44  467.29 2118.43
#Mann= 4 ,-1 , 0
       0      .1       0   84.01     .05       0  235.98     .05       0
  250.02     .05       0
Bank Sta=235.98,250.02
Exp/Cntr=0.3,0.1

Type RM Length L Ch R = 1 ,17113   ,244.38,230.22,217.63
XS GIS Cut Line= 6
  958565.7818802  769207.6537927   958438.700408  769159.8002247
   958398.200184  769128.9000006  958373.3999279  769098.7995206
  958324.7998639  769084.2003525  958235.2930478  769075.2055365
#Sta/Elev= 30
       0 2095.38    4.42 2092.62   32.89  2076.8   46.78 2070.11   52.23 2068.87
   70.03 2065.97   73.82 2064.93   85.09 2064.69   88.74  2064.1  111.47  2063.6
  120.09  2062.1  135.81  2061.5  150.88    2059  158.98  2055.6  176.95 2055.23
  188.38  2055.7  205.97 2058.69  227.39  2062.2  259.07  2064.3  272.88  2072.1
  278.41  2073.6  283.33 2073.65   288.5  2074.6  291.58 2074.46  309.51 2081.96
  317.19 2087.22  329.23 2093.18  341.17 2098.49  346.02 2101.46  368.36 2113.17
#Mann= 4 ,-1 , 0
       0      .1       0   85.09     .07       0  150.88    .055       0
  205.97     .05       0
Bank Sta=150.88,205.97
Exp/Cntr=0.3,0.1

Type RM Length L Ch R = 1 ,16882   ,282.7,272.32,260.83
XS GIS Cut Line= 5
  958595.4256563  768940.8659523  958478.1141681  768915.0068803
   958437.749112  768909.9606083   958406.844792  768908.0692803
  958283.2264878  768896.7161923
#Sta/Elev= 30
       0  2107.2    9.56  2103.2   31.58 2095.54   58.89 2082.69   72.58 2077.63
   83.62 2074.14  117.56 2059.07  132.83 2055.55  138.25 2055.42  141.32 2055.37
  144.74 2054.71  149.34 2055.61  155.98 2056.88  161.43 2057.37  164.54 2058.73
  205.53 2063.47  214.57 2066.47   217.7 2066.99  229.11 2068.73  249.13 2070.41
  249.47 2070.42  260.76 2080.16  270.65 2088.17  278.86 2094.44  285.86 2097.36
  293.84 2102.99  297.42 2105.86  305.32 2112.96  308.73 2115.14  315.91 2118.94
#Mann= 5 ,-1 , 0
       0      .1       0  138.25    .055       0  149.34     .05       0
   217.7     .03       0  249.13     .07       0
Bank Sta=138.25,149.34
Exp/Cntr=0.3,0.1

Type RM Length L Ch R = 1 ,16610   ,496.95,481.13,459.32
XS GIS Cut Line= 5
  958560.1058482  768565.5965758  958489.4672561  768601.5471679
  958370.2634159   768674.078112  958329.2675759   768705.613216
  958292.6872238  768769.9449921
#Sta/Elev= 30
       0 2086.02   20.86 2083.62   32.04 2081.64   46.47 2081.02    52.7 2079.92
   70.24 2077.61    81.8 2075.71  104.23  2072.5  114.16  2071.3   119.5 2070.39
  139.37 2065.03  150.06 2060.34  164.56 2058.33  175.43 2057.82  188.62 2056.68
  203.39 2054.68  209.19    2057  220.27 2060.85  233.65 2063.58  241.83 2066.87
   246.7 2066.75  250.95 2067.07  261.05 2066.68  263.99 2067.32  273.23 2067.84
  297.49 2091.14  312.72 2101.17  316.57 2102.91  335.78 2114.63  344.53 2119.43
#Mann= 3 , 0 , 0
       0     .09       0  188.62    .055       0  209.19     .05       0
Bank Sta=188.62,209.19
Exp/Cntr=0.3,0.1

Type RM Length L Ch R = 1 ,16129   ,511.27,518.57,526.27
XS GIS Cut Line= 4
  958107.0114476  768246.9052474  957969.7974954  768421.1316796
  957993.4549674  768624.2052159  958004.4445354   768711.508384
#Sta/Elev= 30
       0 2112.85    29.4    2105    34.4 2103.38   50.36 2096.16   76.07 2087.27
  100.37 2077.32  103.13 2076.88  111.46 2074.12  143.49 2066.58  207.74 2059.81
  234.82 2057.51  246.28  2055.3  254.28 2052.45  265.59 2051.85  276.93 2051.17
  280.26 2052.18  297.19 2057.69  307.03 2057.15  337.02  2056.9  387.71 2058.41
  395.66 2059.58  412.45 2064.94  422.95 2071.47  433.68 2071.13   443.5 2071.43
  450.78 2071.26  477.84 2087.74   479.7 2087.39  491.45 2092.79  514.21 2100.68
#Mann= 4 ,-1 , 0
       0      .1       0  111.46     .05       0  265.59    .055       0
  280.26     .05       0
Bank Sta=265.59,280.26
Exp/Cntr=0.3,0.1

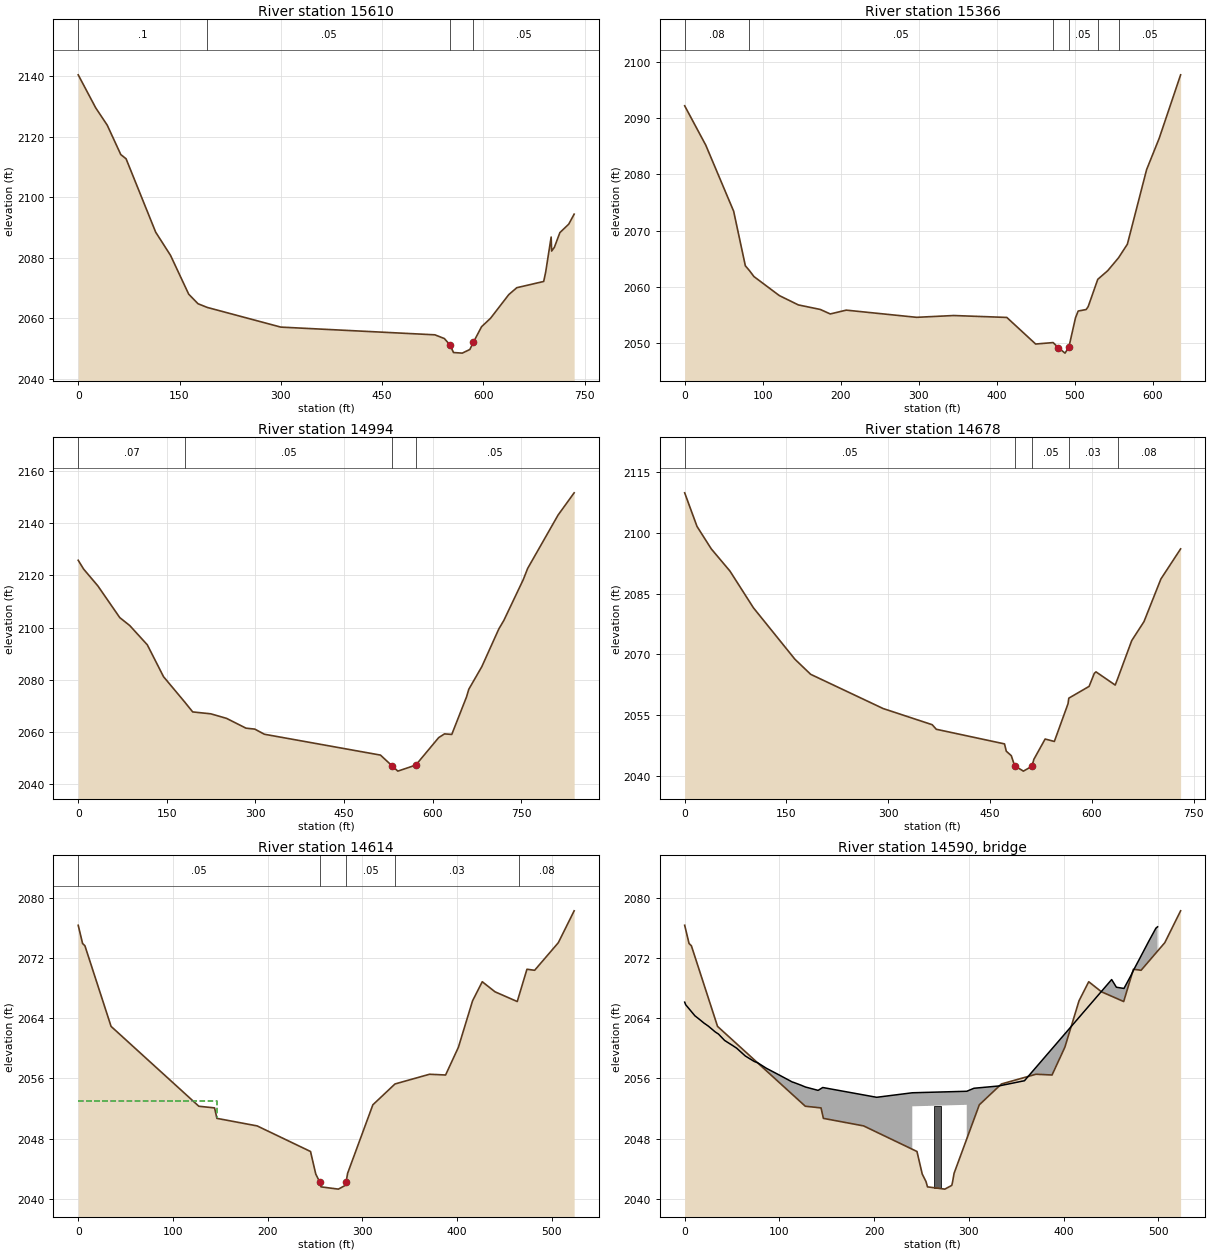
Type RM Length L Ch R = 1 ,15610   ,244.45,244.73,244.04
XS GIS Cut Line= 6
  957802.5137832   767968.920991   957680.561527  768104.4238392
  957586.9413028  768211.5946553  957535.2037028  768294.1280314
  957481.0023587  768401.2978236  957398.4689826  768574.9887038
#Sta/Elev= 30
       0 2140.38   25.94 2129.46      43 2123.74   63.05 2114.03   70.87 2112.65
  114.73 2088.39  136.66 2080.74   163.6 2067.91  177.42 2064.74  191.12 2063.52
  299.98 2057.02  528.17 2054.47  542.21 2053.24   550.5 2051.14  555.76 2048.62
  568.67 2048.42  579.95 2049.62  585.15 2051.99  597.31 2057.15  610.64 2059.95
  637.66 2067.77  649.48 2070.04  689.31  2072.1  692.29 2075.25  700.36 2086.78
  701.08 2082.15  705.11 2083.38  713.29 2088.25   726.4 2091.04  734.41 2094.34
#Mann= 4 ,-1 , 0
       0      .1       0  191.12     .05       0   550.5    .055       0
  585.15     .05       0
Bank Sta=550.5,585.15
Exp/Cntr=0.3,0.1

Type RM Length L Ch R = 1 ,15366   ,364.5,371.79,378.87
XS GIS Cut Line= 3
  957577.5409828   767982.323103  957266.1773984  768292.1609274
  957173.0732703  768465.3951037
#Sta/Elev= 30
       0 2092.23   27.11  2085.2   62.79 2073.45   77.81 2063.72   83.01 2062.87
   88.84  2061.8  121.42 2058.41   145.8 2056.75  173.96 2055.94  186.66 2055.14
  207.13 2055.82  297.38 2054.54  344.97 2054.86  413.04 2054.52  450.04 2049.78
  472.42 2050.04   479.3 2049.11  487.67 2048.16  492.58  2049.2  501.11 2054.45
  504.54 2055.66  514.84 2055.93  517.42 2056.46  529.68 2061.31  542.44 2062.85
  556.28 2065.14  567.63 2067.57  592.28 2080.85  608.57 2086.49  635.91 2097.75
#Mann= 6 ,-1 , 0
       0     .08       0   83.01     .05       0  472.42     .05       0
  492.58     .05       0  529.68     .03       0  556.28     .05       0
Bank Sta=479.3,492.58
Exp/Cntr=0.3,0.1

Type RM Length L Ch R = 1 ,14994   ,318.4,315.66,313.54
XS GIS Cut Line= 5
  957606.8642469  767712.1755186  957143.3823902   767972.402591
  957081.7908381  768017.0571831  957026.3576221  768057.0925111
  956930.8901019  768189.5151673
#Sta/Elev= 30
       0  2125.8    9.19 2122.41   33.23 2115.98   70.34  2103.8   87.19 2100.76
  116.92 2093.37  144.37 2081.14  179.98 2071.48  193.75 2067.62  224.51 2066.88
  251.03 2065.14  283.85 2061.39  298.78 2061.02  315.11 2059.05  511.52 2051.05
  531.54 2046.84  540.89  2044.9  571.25 2047.22  609.97 2057.75  619.82 2059.19
  632.16 2058.98  657.11 2073.37   660.9 2076.29   682.9 2084.94  711.78 2099.46
  720.23 2102.71  753.11 2118.38  760.58 2122.68  812.13 2143.18  839.24 2151.68
#Mann= 4 ,-1 , 0
       0     .07       0  179.98     .05       0  531.54     .05       0
  571.25     .05       0
Bank Sta=531.54,571.25
Exp/Cntr=0.3,0.1

Type RM Length L Ch R = 1 ,14678   ,60.63,64.49,65.17
XS GIS Cut Line= 6
  957349.9037345  767381.4603822  957059.8004381  767612.2003505
   956991.700342  767686.0000306   956986.599798  767698.3003186
  956926.0998299  767749.6999987  956819.1245978  767876.4476469
#Sta/Elev= 30
       0 2109.77   18.16 2101.51   39.14 2095.99   66.72 2090.52  101.22  2081.5
  162.42 2068.83  185.61 2065.12  292.36  2056.7  364.69 2052.72  370.68  2051.6
  471.22    2048  473.85  2046.2  481.23  2045.1   486.2  2042.6  499.06  2041.3
   511.7  2042.5  514.48  2044.2  531.07  2049.2  544.66  2048.6  564.83  2057.9
  565.95 2059.25  595.86 2062.15  603.51 2065.35  606.01 2065.72  634.29 2062.48
  637.75 2063.96  658.61  2073.4  676.73 2078.09  701.63 2088.57  730.69 2095.98
#Mann= 5 ,-1 , 0
       0     .05       0   486.2     .05       0   511.7     .05       0
  565.95     .03       0  637.75     .08       0
Bank Sta=486.2,511.7
Exp/Cntr=0.5,0.3

Type RM Length L Ch R = 1 ,14614   ,50.08,48.72,45.4
XS GIS Cut Line= 6
   957013.055862  767435.7344302  957037.4936221  767535.4658864
  957020.7000221  767575.8002224   956948.400502  767650.8000305
  956882.4999579  767697.5999026  956765.1608217  767845.3375028
#Sta/Elev= 30
       0 2076.35    4.62 2073.93    7.08 2073.63   34.68 2062.92  127.31 2052.31
  143.89 2052.09  146.39  2050.7  188.79  2049.7  245.16  2046.3  250.71  2043.3
  254.68  2042.3  256.25  2041.6  274.57  2041.3   281.9  2041.8  282.79  2042.3
  284.31  2043.4  310.95  2052.5  334.31 2055.27  370.74 2056.56  387.71 2056.46
  401.25 2060.15  416.19 2066.32  426.41 2068.85  439.92 2067.51  463.34 2066.22
   464.8 2066.84  473.58 2070.51  481.68 2070.37   506.7 2074.04  523.39 2078.27
#Mann= 5 ,-1 , 0
       0     .05       0  254.68     .05       0  282.79     .05       0
  334.31     .03       0   464.8     .08       0
#XS Ineff= 2 , 0
       0  146.39    2053     346       0  2054.9
Permanent Ineff=
       F       F
Bank Sta=254.68,282.79
Exp/Cntr=0.5,0.3

Type RM Length L Ch R = 3 ,14590   ,,,
Bridge Culvert--1,0,-1,-1, 0
Deck Dist Width WeirC Skew NumUp NumDn MinLoCord MaxHiCord MaxSubmerge Is_Ogee
15,14,2.6,0, 43, 44, , , 0.95, 0, 0,0,,
       0    1.04   10.83   14.91   20.23   24.92   32.27   35.56   42.16   51.03
    54.9   64.11   64.56    73.4   76.94   77.49   85.65   86.44   99.79  100.52
  113.89  114.59   123.6  125.04  127.81  129.16  140.79   145.7   202.6   240.2
   297.7   305.3   331.2   358.6   450.6  455.61  463.59   470.9  474.07   479.9
  489.95  497.34   499.1
 2066.14  2065.8 2064.32 2063.92 2063.37 2062.96 2062.18 2061.91 2061.05 2060.34
 2060.02 2058.97 2058.94 2058.26 2058.09 2058.05  2057.4 2057.34 2056.46 2056.41
 2055.51  2055.5 2055.07 2054.99 2054.85 2054.81 2054.42  2054.8  2053.5  2054.1
  2054.3  2054.7    2055  2055.7 2069.14 2068.12 2067.96 2069.66 2070.48 2071.86
 2074.27 2075.97 2076.15
                                                                                
                                                                                
                                                                          2052.3
  2052.5
                        
       0    1.04   10.83   14.91   20.23   24.92   32.27   35.56   42.16   51.03
    54.9   64.11   64.56    73.4   76.94   77.49   85.65   86.44   99.79  100.52
  113.89  114.59  115.43   160.6   186.2   242.7     256   283.7   309.3   414.2
  421.47  421.52  427.97  435.45  441.78  449.63  455.61  463.59   470.9  474.07
   479.9  489.95  497.34   499.1
 2066.14  2065.8 2064.32 2063.92 2063.37 2062.96 2062.18 2061.91 2061.05 2060.34
 2060.02 2058.97 2058.94 2058.26 2058.09 2058.05  2057.4 2057.34 2056.46 2056.41
 2055.51  2055.5  2054.8  2053.5  2054.1  2054.3  2054.7    2055  2055.7 2069.14
 2069.91  2069.9 2069.59 2069.18 2069.13 2068.76 2068.12 2067.96 2069.66 2070.48
 2071.86 2074.27 2075.97 2076.15
                                                                                
                                                                                
                                  2052.3  2052.5
                                                                                
                                
Pier Skew, UpSta & Num, DnSta & Num=  ,267, 4 ,212, 4 , 0 , 0 , 0 ,,
       7       7       3       3
    2042  2043.5  2043.5  2052.6
       7       7       3       3
    2042  2043.5  2043.5  2052.6
BR Coef=-1 , 0 , 0 ,, 0 ,,,0.8,0,,0,
WSPro=,,,, 1 ,,,, 0 ,,,, 0 ,,,,-1 ,-1 ,-1 , 0 , 0 , 0 , 0 , 0
BC Design=,, 0 ,, 0 ,,,,,,

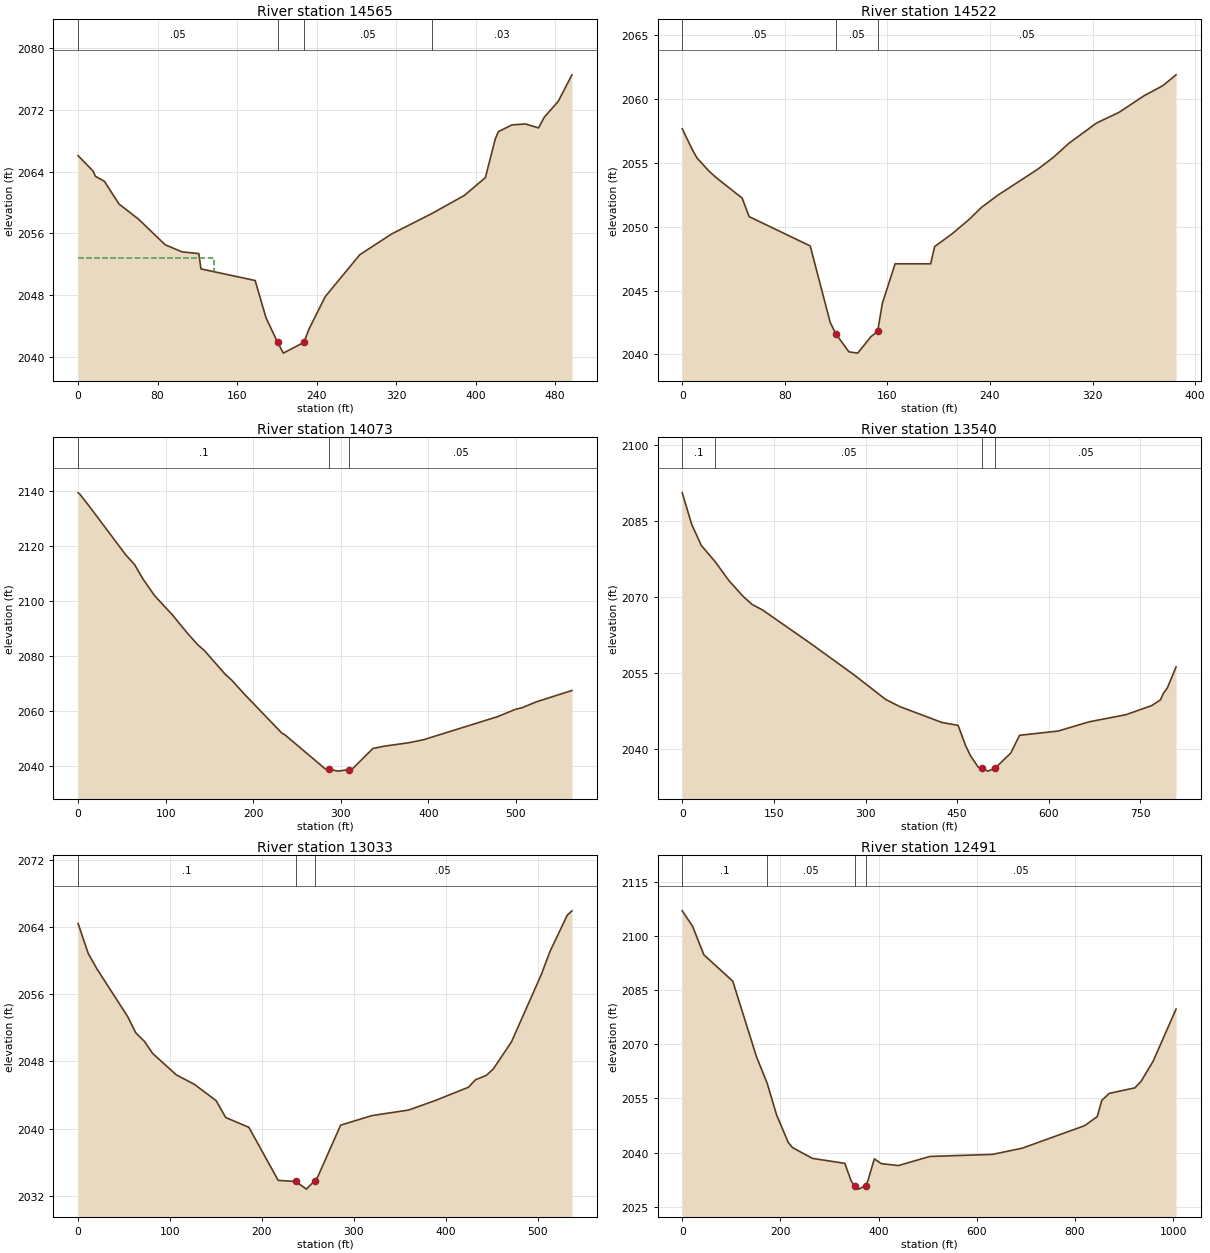
Type RM Length L Ch R = 1 ,14565   ,39.86,42.62,56.02
XS GIS Cut Line= 6
   956959.558006  767446.9625903   956986.636662  767501.1209263
   956966.799734  767561.0003504  956931.5004059  767602.4999985
  956779.5961497  767724.6570546  956736.3126937  767839.5795508
#Sta/Elev= 30
       0 2066.06   15.02 2064.07   17.44 2063.39   26.43 2062.74    41.2 2059.79
   60.55 2057.87   87.54 2054.53  104.45 2053.61  121.45 2053.38  123.61  2051.4
  178.11  2049.9  188.99  2045.1  200.67  2041.9  206.48  2040.5  227.25  2041.9
  232.22  2043.6  248.56  2047.8  283.49 2053.25  315.54 2055.93  356.08 2058.58
  388.75 2060.92  409.75 2063.22  419.67  2068.2  422.83 2069.17  436.57 2070.04
     450 2070.16  463.28 2069.65  468.97 2071.03  483.02 2073.08  496.83 2076.52
#Mann= 4 ,-1 , 0
       0     .05       0  200.67    .055       0  227.25     .05       0
  356.08     .03       0
#XS Ineff= 2 , 0
       0   136.4 2052.75  283.49       0    2053
Permanent Ineff=
       F       F
Bank Sta=200.67,227.25
Exp/Cntr=0.5,0.3

Type RM Length L Ch R = 1 ,14522   ,468.3,449.35,424.43
XS GIS Cut Line= 6
   956962.427254  767486.6016303  956936.7996059  767531.9996464
  956894.3998619  767579.0002224  956875.7999259  767588.9002545
  956856.8999578  767590.7004465  956690.8296856  767748.2326067
#Sta/Elev= 30
       0 2057.68    7.84 2056.05   11.47  2055.4    20.9 2054.36   26.65 2053.84
   46.73 2052.25   52.15  2050.8    99.8  2048.5  115.43  2042.5   119.9  2041.6
  129.99  2040.2  136.85  2040.1  147.25  2041.4  152.41  2041.8  156.07    2044
     166  2047.1  193.77  2047.1  196.86 2048.45  210.71 2049.47  224.36 2050.63
  233.25 2051.51  246.35 2052.49  276.96 2054.49  289.58 2055.45  301.54 2056.54
   323.1 2058.13  340.68 2058.97  360.17 2060.27  374.84 2061.06  385.16 2061.91
#Mann= 3 , 0 , 0
       0     .05       0   119.9     .05       0  152.41     .05       0
Bank Sta=119.9,152.41
Exp/Cntr=0.3,0.1

Type RM Length L Ch R = 1 ,14073   ,529.97,532.53,534.95
XS GIS Cut Line= 4
  956480.9455253  767308.3447341  956464.5113493  767573.4880304
  956464.5113493  767646.8955185  956568.5958294  767846.3000628
#Sta/Elev= 30
       0 2139.25    2.16 2138.71   12.94 2134.31    54.4 2116.75   64.57 2113.19
    73.6 2108.23   87.26 2101.98   107.7 2094.98  124.63 2088.41  136.45 2084.22
  144.47 2081.97  167.54  2073.6  175.21 2071.36   189.8 2066.26  232.86 2052.04
  236.59 2051.37  281.93  2039.2   286.9 2038.95  296.88  2038.3  309.45 2038.86
  312.86 2038.99  336.62  2046.5  348.92 2047.31     378 2048.62  394.19 2049.66
  478.97 2058.05  499.71 2060.74  506.98 2061.29  523.19 2063.42  563.99 2067.55
#Mann= 3 , 0 , 0
       0      .1       0   286.9    .055       0  309.45     .05       0
Bank Sta=286.9,309.45
Exp/Cntr=0.3,0.1

Type RM Length L Ch R = 1 ,13540   ,488.62,507.59,518.78
XS GIS Cut Line= 5
   956265.105781  767207.5462699  955990.1023886  767448.5856303
  955944.0858766  767519.8017584  955932.0333965  767619.5045425
  955948.4419726  767876.3534389
#Sta/Elev= 30
       0 2090.49   15.48 2084.27   31.21 2080.11   53.93 2076.91   76.56 2073.16
   99.39 2070.11  114.03 2068.51  131.58 2067.38  210.25 2060.78  280.75 2054.64
  332.92 2049.76  356.14 2048.34  424.91 2045.22  451.53 2044.64  463.95 2040.61
  471.88 2038.63  484.55 2036.39  489.85 2036.14  500.61 2035.62  511.99 2036.21
  537.62 2039.16  552.04 2042.68  615.51 2043.53  665.93 2045.34  726.05 2046.74
  768.33 2048.54  782.73 2049.67   787.2 2050.88  794.47 2052.15  808.28 2056.16
#Mann= 4 ,-1 , 0
       0      .1       0   53.93     .05       0  489.85     .05       0
  511.99     .05       0
Bank Sta=489.85,511.99
Exp/Cntr=0.3,0.1

Type RM Length L Ch R = 1 ,13033   ,553.93,542.16,529.34
XS GIS Cut Line= 3
  955823.6061324  767124.9094698  955489.4657159  767323.8020141
   955541.177716  767463.0271023
#Sta/Elev= 30
       0  2064.4   11.02 2060.84   20.52    2059    54.1  2053.3   62.62 2051.42
   72.16 2050.38   81.12 2048.94  106.94 2046.39  126.62 2045.26  150.11 2043.34
  160.67 2041.32  185.87 2040.15  217.74 2033.84   236.9 2033.71  248.46  2032.8
   257.4  2033.8  260.71 2034.25  285.67 2040.41  319.82 2041.55   359.7 2042.21
  388.86 2043.35   424.7 2044.92  432.43 2045.81   444.2 2046.33  451.77 2047.09
   471.6 2050.32  504.17 2058.36  513.31 2061.03  532.23 2065.38  537.38 2065.91
#Mann= 3 , 0 , 0
       0      .1       0   236.9    .055       0   257.4     .05       0
Bank Sta=236.9,257.4
Exp/Cntr=0.3,0.1

Type RM Length L Ch R = 1 ,12491   ,596.84,598.58,598.13
XS GIS Cut Line= 4
  955398.5939078  766837.2934694  955147.1763074  767041.5917097
  955099.0073474  767156.1404459  954889.9055231  767673.0945586
#Sta/Elev= 30
       0 2106.97      21  2102.7   44.04 2094.79  102.95 2087.47   151.2 2066.56
  172.88 2059.25  192.14 2050.46  216.02 2042.77  224.65 2041.37  265.05 2038.39
  331.14 2037.01  343.88 2032.21  351.08 2030.72  359.31 2029.87   373.5 2030.86
  378.15  2032.2   391.3 2038.26  405.45 2036.93  440.28  2036.4  504.32 2038.92
  632.24  2039.5  692.58 2041.22  819.55 2047.44  845.29 2049.96   854.6 2054.45
  869.88  2056.4  921.93 2057.92  934.56 2059.72  958.99 2065.26 1005.88 2079.76
#Mann= 4 ,-1 , 0
       0      .1       0  172.88     .05       0  351.08     .05       0
   373.5     .05       0
Bank Sta=351.08,373.5
Exp/Cntr=0.3,0.1