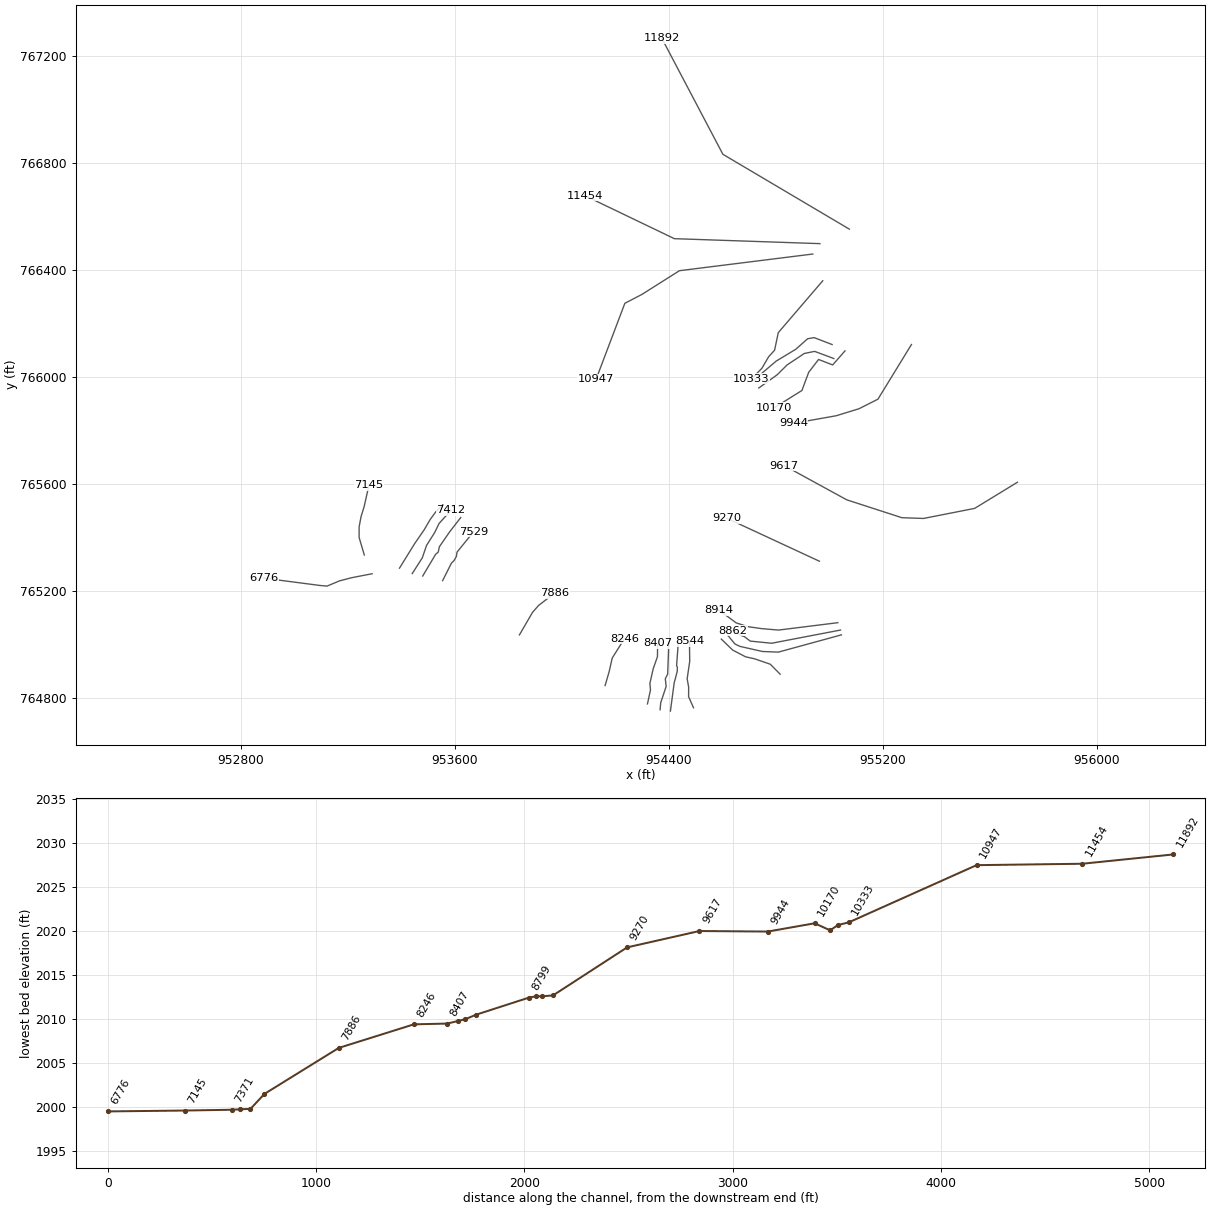
HEC-RAS study dtl_little_ivy_crk.prj: dtl_Little_Ivy_Crk

--- dtl_little_ivy_crk.g01 (geometry) --- (continued)

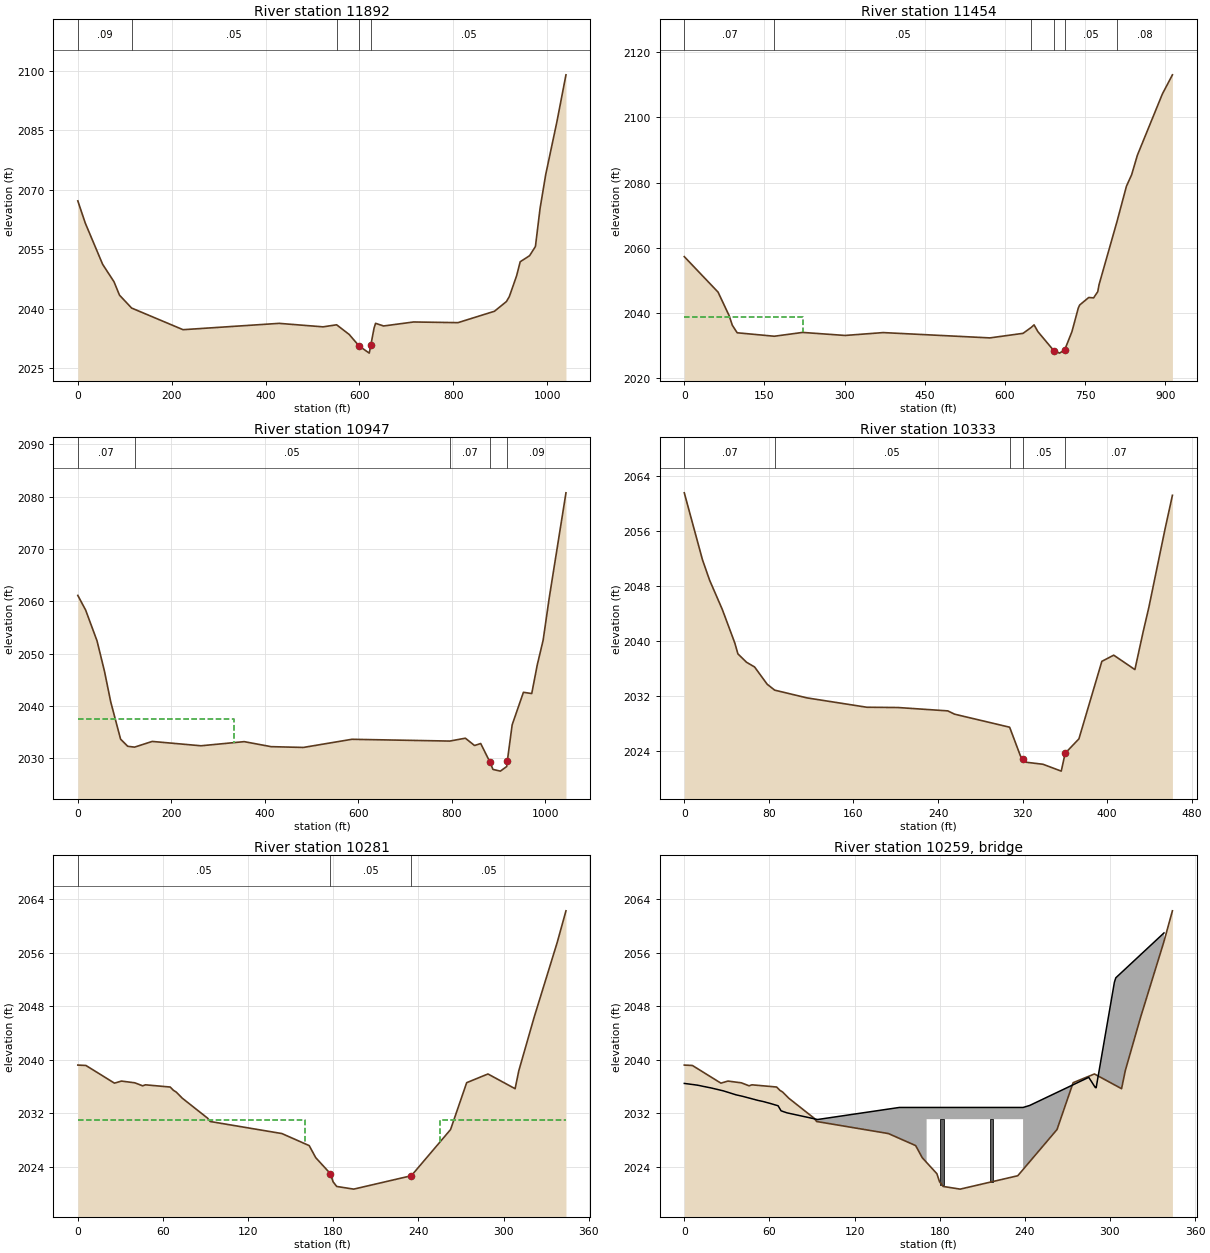
Type RM Length L Ch R = 1 ,11892   ,427.63,438.16,448.17
XS GIS Cut Line= 3
  955074.0739713   766552.120733  954601.4191227  766832.0004134
  954372.9452664   767266.100638
#Sta/Elev= 30
       0 2067.19   15.94 2061.56    52.9 2051.16   77.02 2046.77   88.81 2043.37
  114.59 2040.12  224.16 2034.65  428.89 2036.25  522.36 2035.37  551.32 2035.89
  578.13 2033.44  599.06 2030.55  620.85 2028.73  624.33 2030.84  631.04 2035.04
   634.3 2036.26  651.38 2035.59  715.32  2036.6   809.8 2036.43  887.57 2039.31
  913.01 2041.76  919.19 2043.01  934.64 2048.24  942.37 2051.81  962.41 2053.35
  974.83 2055.68  984.67 2065.26  996.76 2073.87 1020.65 2087.24 1039.86 2099.04
#Mann= 5 ,-1 , 0
       0     .09       0  114.59     .05       0  551.32     .07       0
  599.06    .055       0  624.33     .05       0
Bank Sta=599.06,624.33
Exp/Cntr=0.3,0.1

Type RM Length L Ch R = 1 ,11454   ,478.71,506.89,537.63
XS GIS Cut Line= 3
  954964.1209472  766497.8589729  954420.0687224   766516.422045
   954087.353714  766676.3534372
#Sta/Elev= 30
       0 2057.26   63.27 2046.37   83.85 2039.19   89.88 2036.23   98.96 2033.91
  168.52 2032.85  221.38 2034.02  300.95 2033.09  372.24 2033.97  571.87 2032.34
  633.99 2033.74  649.33 2035.56  654.59 2036.34  661.88 2034.23  691.82 2028.38
  702.35 2027.67  712.06 2028.72   725.5 2034.27  737.42 2041.54  740.01 2042.44
  756.85 2044.73     766 2044.62  773.78 2046.52  776.21 2048.68   809.6 2067.92
  827.41 2078.84   837.2 2082.39  847.93 2088.37  894.77 2107.18  913.53 2113.03
#Mann= 6 ,-1 , 0
       0     .07       0  168.52     .05       0  649.33     .07       0
  691.82    .055       0  712.06     .05       0   809.6     .08       0
#XS Ineff= 2 , 0
       0     222  2038.6               0
Permanent Ineff=
       F       F
Bank Sta=691.82,712.06
Exp/Cntr=0.3,0.1

Type RM Length L Ch R = 1 ,10947   ,619.9,613.88,609.02
XS GIS Cut Line= 5
  954937.5983231  766459.0043169  954439.0393465  766396.6847008
  954298.4892023  766307.8455327  954234.8435062  766274.6966046
   954127.441266  765990.9431322
#Sta/Elev= 30
       0 2061.12   16.69 2058.33   41.07 2052.43   56.95 2046.64   70.37 2040.75
   91.47 2033.63  106.74 2032.26  121.31  2032.1  159.11 2033.19  263.34 2032.36
  355.76 2033.15  413.44 2032.19  482.28 2032.04  586.13  2033.6  795.45 2033.26
  828.75 2033.81  848.37 2032.41  861.55 2032.79  881.57  2029.2  887.73 2027.84
  903.59 2027.51  917.27  2028.4  918.51 2029.47  928.83 2036.37  952.91 2042.59
  970.68 2042.35  982.44 2047.81  995.07 2052.56 1008.02 2060.61 1043.88 2080.75
#Mann= 5 ,-1 , 0
       0     .07       0  121.31     .05       0  795.45     .07       0
  881.57    .055       0  918.51     .09       0
#XS Ineff= 2 , 0
       0     334  2037.5               0
Permanent Ineff=
       F       F
Bank Sta=881.57,918.51
Exp/Cntr=0.3,0.1

Type RM Length L Ch R = 1 ,10333   ,60.44,51.92,28.22
XS GIS Cut Line= 6
  954974.9057152  766359.0701087   954808.499571  766164.9995805
  954794.7001469  766099.2997404  954772.1997949  766074.5005083
  954747.3002109  766031.7003803  954708.2940028  765992.3286042
#Sta/Elev= 30
       0 2061.56   17.22 2051.79   23.94 2048.83   35.96 2044.56   47.77 2039.68
   50.71 2038.09   58.84 2036.87   66.48 2036.18   78.48 2033.65   85.55  2032.8
  116.15 2031.67  172.64 2030.31  202.09 2030.27  249.21 2029.78  255.63  2029.3
  307.71  2027.4  317.96  2023.2  320.54  2022.8  322.99  2022.3  339.24    2022
  356.51    2021   360.2  2023.6  373.22  2025.7  394.92    2037  406.14  2037.9
  426.17  2035.8  433.91 2041.26  439.33 2044.84  454.81 2056.38  461.67  2061.2
#Mann= 5 ,-1 , 0
       0     .07       0   85.55     .05       0  307.71     .07       0
  320.54     .05       0   360.2     .07       0
Bank Sta=320.54,360.2
Exp/Cntr=0.5,0.3

Type RM Length L Ch R = 1 ,10281   ,33.4,36.74,50.66
XS GIS Cut Line= 6
  955009.7442432  766120.5323804  954942.6886272  766146.3228444
  954918.3000191  766142.2002204  954873.9997311  766102.7997724
   954800.800115  766058.7001883  954715.0247548  765985.6869402
#Sta/Elev= 29
       0 2039.23   5.709 2039.17  25.819 2036.53  30.765 2036.84  40.183 2036.58
  45.688 2036.13  47.649 2036.28  65.094 2035.95  67.383 2035.46  69.392 2035.19
  73.642 2034.28  91.454  2031.3  93.299  2030.8 143.836    2029 163.068  2027.2
 167.675  2025.4  178.03    2023 179.894  2021.8 182.434  2021.1 194.441  2020.7
 235.039  2022.7 262.693  2029.6 274.052  2036.6 289.044  2037.9 308.179  2035.7
 310.796 2038.39 321.634  2046.4 337.833 2057.53 344.024 2062.27
#Mann= 3 ,-1 , 0
       0     .05       0  178.03     .05       0 235.039     .05       0
#XS Ineff= 2 , 0
       0     160    2031     255       0    2031
Permanent Ineff=
       F       F
Bank Sta=178.03,235.039
Skew Angle= 15
Exp/Cntr=0.5,0.3

Type RM Length L Ch R = 3 ,10259   ,,,
Bridge Culvert--1,0,-1,-1, 0
Deck Dist Width WeirC Skew NumUp NumDn MinLoCord MaxHiCord MaxSubmerge Is_Ogee
15,12,2.6,15, 30, 39, , , 0.95, 0, 0,0,,
       0   6.462   8.519   9.225  17.522  18.353  27.703  27.954  36.406  41.313
  46.683   51.59  55.676  60.399  66.118  68.194  72.251  93.936 151.554 170.776
 238.777 243.413 285.045 289.642  290.27 299.485 303.117 303.407 304.131 338.074
 2036.49 2036.31 2036.25 2036.23 2035.87 2035.84 2035.37 2035.35 2034.79 2034.55
 2034.25 2033.97 2033.78 2033.51 2033.15  2032.4  2032.1  2031.1  2032.9  2032.9
  2032.9  2033.2  2037.4 2035.88 2035.85 2047.14  2051.6  2051.8 2052.27 2058.97
                                                                                
                                                                         2031.15
 2031.15
       0   6.462   8.519   9.225  17.522  18.353  27.703  27.954  36.406  41.313
  46.683   51.59  55.676  60.399  66.118  69.634   71.45  72.541  74.666  89.638
 123.445 191.446 201.202 223.254 263.601 267.281 268.238 269.049 269.831 276.689
  279.51 283.354 289.642  290.27 299.485 303.117 303.407 304.131 317.171
 2036.49 2036.31 2036.25 2036.23 2035.87 2035.84 2035.37 2035.35 2034.79 2034.55
 2034.25 2033.97 2033.78 2033.51 2033.15 2032.88  2032.7  2032.4  2032.1  2031.1
  2032.9  2032.9  2032.9  2033.2  2037.4 2037.57 2037.69 2037.74 2037.71 2037.03
 2036.81  2036.6 2035.88 2035.85 2047.14  2051.6  2051.8 2052.27 2058.97
                                                                                
                                                                                
 2031.15 2031.15
                                                                        
Pier Skew, UpSta & Num, DnSta & Num=  ,181.594, 4 ,141.025, 4 , 0 , 0 , 0 ,,
       3       3       2       2
    2020    2022    2022  2032.9
       3       3       2       2
    2020    2022    2022  2032.9
Pier Skew, UpSta & Num, DnSta & Num=  ,216.367, 2 ,170.003, 2 , 0 , 0 , 0 ,,
       2       2
    2031 2031.15
       2       2
    2031 2031.15
BR Coef=-1 , 0 , 0 ,, 0 ,,,0.8,0,,0,
WSPro=,,,, 1 ,,,, 0 ,,,, 0 ,,,,-1 ,-1 ,-1 , 0 , 0 , 0 , 0 , 0
BC Design=,, 0 ,, 0 ,,,,,,

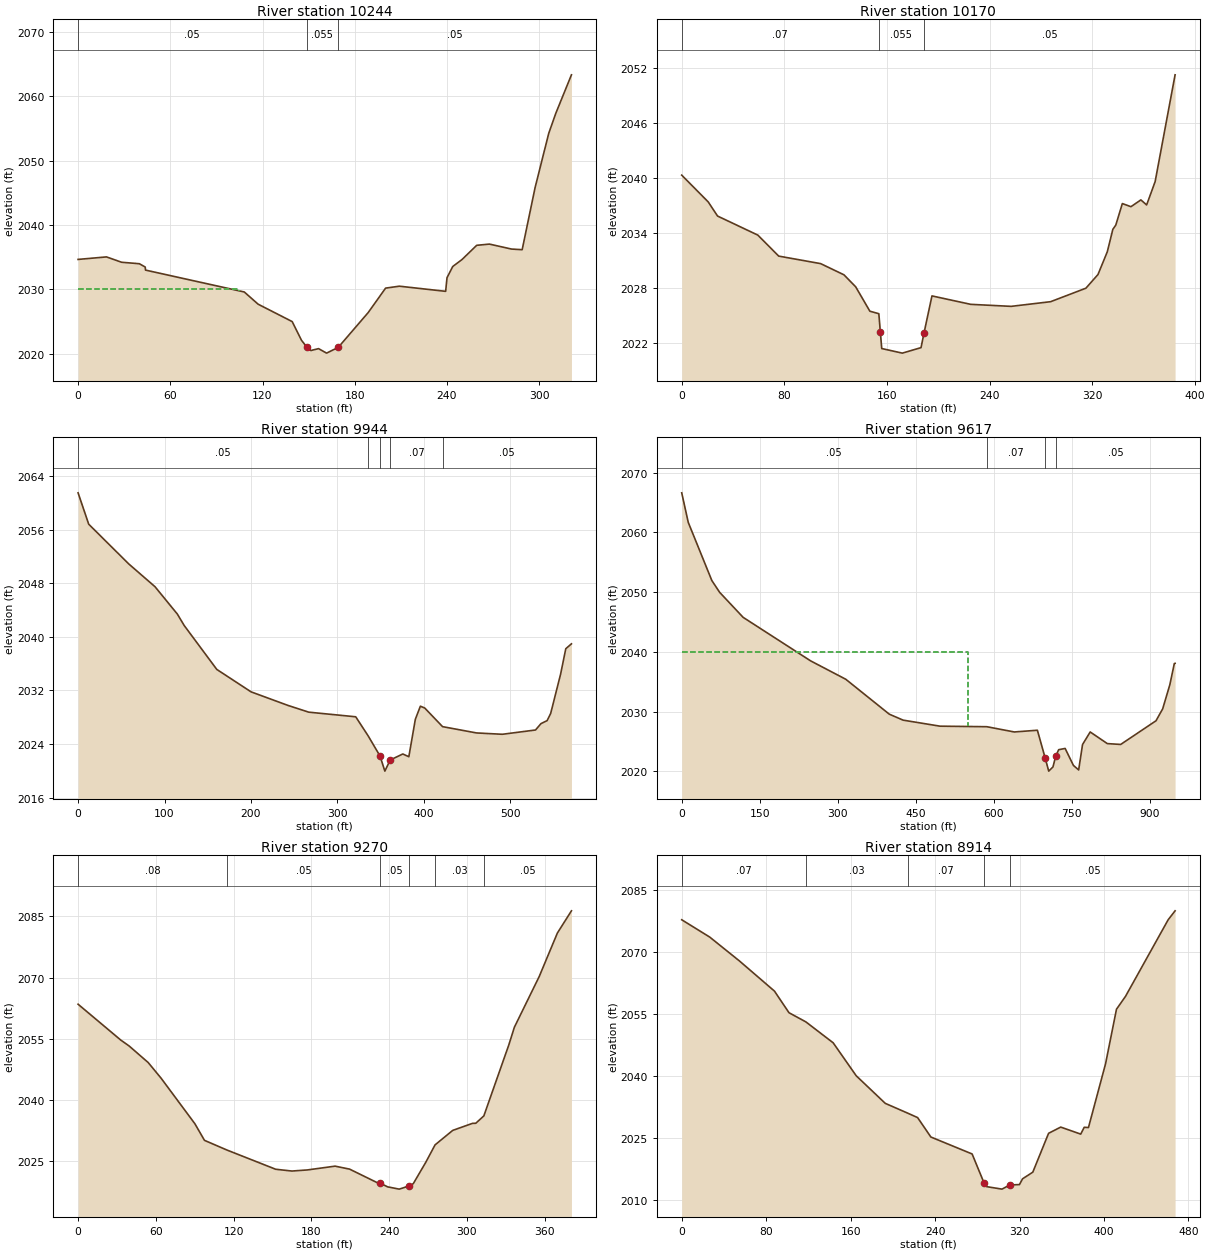
Type RM Length L Ch R = 1 ,10244   ,66.96,74.79,84.65
XS GIS Cut Line= 6
  955016.1606273  766068.2008603  954944.3956352  766094.9108764
  954905.9004031  766087.0998044   954841.500019  766044.2996763
   954804.499827  766007.5001882  954735.6716669  765958.0389402
#Sta/Elev= 30
       0 2034.66  18.488 2035.05  28.302 2034.22  39.873 2033.99   43.67 2033.48
  43.882    2033 108.155  2029.6 117.176  2027.7 139.325    2025 145.362  2022.1
 148.637  2021.1 151.428  2020.5  156.47  2020.8 161.706  2020.1 169.317    2021
 188.771  2026.4 200.101  2030.2 209.055  2030.5 239.173  2029.7 240.071 2031.82
   243.8 2033.56 249.769 2034.63  259.38 2036.85 267.658 2037.04 282.031 2036.27
 288.966 2036.17  297.38 2045.82 306.247 2054.24 310.854 2057.36 321.035 2063.34
#Mann= 3 ,-1 , 0
       0     .05       0 148.637    .055       0 169.317     .05       0
#XS Ineff= 2 , 0
       0  104.96    2030  209.05       0    2030
Permanent Ineff=
       F       F
Bank Sta=148.637,169.317
Skew Angle= 15
Exp/Cntr=0.5,0.3

Type RM Length L Ch R = 1 ,10170   ,237.49,225.25,213.35
XS GIS Cut Line= 6
  955057.8998913  766096.7192604  955011.8188673  766044.2239003
  954959.1002752  766064.6998043  954922.2997631  766016.8001563
  954896.8226431  765948.6140442  954792.3306109  765883.2388121
#Sta/Elev= 30
       0 2040.31   20.65 2037.39   27.92 2035.85   59.32 2033.77   75.59 2031.48
  108.26 2030.66  126.41 2029.44  135.56 2028.13  146.61 2025.47  153.58  2025.2
  154.782023.182  155.84  2021.4   171.9  2020.9  186.46  2021.5  188.79  2023.1
  194.98 2027.14  225.21 2026.22  256.67    2026  287.45 2026.51  314.91 2027.98
  324.32 2029.47  331.59 2031.95  335.91  2034.4  338.21 2034.86  343.31 2037.21
  350.02 2036.87  357.76 2037.61  362.24 2037.06  368.88 2039.61  384.41 2051.25
#Mann= 3 ,-1 , 0
       0     .07       0  153.58    .055       0  188.79     .05       0
Bank Sta=154.78,188.79
Exp/Cntr=0.3,0.1

Type RM Length L Ch R = 1 ,9944    ,340.22,327.57,310.81
XS GIS Cut Line= 6
  955306.3693957  766120.5293084  955181.1690115  765916.2556441
  955110.5672834  765880.4842521  955024.9045633   765854.126492
  954908.1767551   765833.417116   954864.999795   765825.849756
#Sta/Elev= 30
       0  2061.5   12.29 2056.82    58.6 2050.89   88.97 2047.49  114.86  2043.4
  122.79 2041.69  160.47 2035.14  200.16 2031.79  242.98 2029.76  266.88 2028.76
  321.19 2028.07  335.74 2025.19  349.35  2022.2  354.89 2019.96  361.07 2021.62
  375.67 2022.52  382.64 2022.11  390.18 2027.71  395.98 2029.65  401.02 2029.38
  421.64  2026.6  460.92 2025.66  490.84 2025.46  529.19  2026.1  535.49 2027.05
  542.61  2027.5  546.72 2028.57  558.23 2034.45  564.19 2038.23  570.75 2038.96
#Mann= 5 ,-1 , 0
       0     .05       0  335.74     .07       0  349.35    .055       0
  361.07     .07       0  421.64     .05       0
Bank Sta=349.35,361.07
Exp/Cntr=0.3,0.1

Type RM Length L Ch R = 1 ,9617    ,342.67,347.34,346.61
XS GIS Cut Line= 6
  955702.5918602  765605.4614037   955542.649204  765507.7083155
  955351.5544197  765470.0537875  955270.5980036  765472.8779795
  955064.4412033  765539.7144596   954830.963059  765667.5465238
#Sta/Elev= 30
       0 2066.64   12.56 2061.69   57.88 2051.95   72.91 2049.97  118.07 2045.78
  247.81 2038.49  315.36 2035.41  399.03 2029.56  425.65 2028.56  496.58 2027.55
  586.65 2027.46  639.33 2026.58  683.71 2026.87  698.79 2022.19  705.52 2020.02
  713.63 2020.72     719 2022.52  724.59 2023.61  737.06 2023.82  753.05 2020.97
  763.06 2020.22  770.53 2024.48  785.23 2026.58  818.17 2024.63  843.87 2024.49
  911.79 2028.46  924.59 2030.46  938.37 2034.51  946.93 2038.04  948.42 2038.08
#Mann= 4 ,-1 , 0
       0     .05       0  586.65     .07       0  698.79     .05       0
     719     .05       0
#XS Ineff= 2 , 0
       0     550    2040               0
Permanent Ineff=
       F       F
Bank Sta=698.79,719
Exp/Cntr=0.3,0.1

Type RM Length L Ch R = 1 ,9270    ,353.71,355.41,362.7
XS GIS Cut Line= 2
  954962.3299712  765310.0394513  954617.0177147  765470.3630355
#Sta/Elev= 30
       0 2063.46   33.05 2054.65   39.47 2053.21    54.1 2049.17   64.03 2045.35
   90.11 2034.19   97.54 2030.11  114.77 2027.75  152.49 2023.03     165 2022.59
  176.96 2022.86   198.3 2023.79  209.53 2023.06  231.31 2019.67  233.04 2019.64
  238.84 2018.72  247.79 2018.16  255.62 2018.95  258.67  2019.5  268.36 2024.76
  275.47    2029  289.11 2032.55  304.42 2034.28  306.87 2034.29  313.12  2036.1
  332.46 2053.56  336.68 2057.82  355.88 2070.27  369.87  2080.9  380.72 2086.34
#Mann= 6 ,-1 , 0
       0     .08       0  114.77     .05       0  233.04     .05       0
  255.62     .05       0  275.47     .03       0  313.12     .05       0
Bank Sta=233.04,255.62
Exp/Cntr=0.3,0.1

Type RM Length L Ch R = 1 ,8914    ,50.8,51.82,45.69
XS GIS Cut Line= 6
  955031.0116993   765080.181147   954809.300339  765052.5997069
  954747.4998909  765057.8999309  954695.3997948  765065.2000269
  954651.0554747   765079.509403  954585.9382907   765127.843227
#Sta/Elev= 30
       0 2077.83   26.49 2073.65   54.68 2067.87   87.84 2060.58  101.62 2055.35
  117.58 2053.14  143.45 2048.08  165.28 2040.11  192.79 2033.44  213.96 2031.08
  223.42    2030     236  2025.3  275.06  2021.2  286.19  2014.3   288.8  2013.3
  303.34  2012.7  310.67  2013.7  319.88  2013.8  322.87  2015.2  332.54  2016.8
   347.5  2026.2  358.99  2027.7  377.92    2026  381.25 2027.65  385.26 2027.59
  401.47 2043.03   411.8  2056.2  420.35 2059.31   460.8 2077.85  467.31 2079.99
#Mann= 5 ,-1 , 0
       0     .07       0  117.58     .03       0  213.96     .07       0
  286.19    .055       0  310.67     .05       0
Bank Sta=286.19,310.67
Exp/Cntr=0.5,0.3

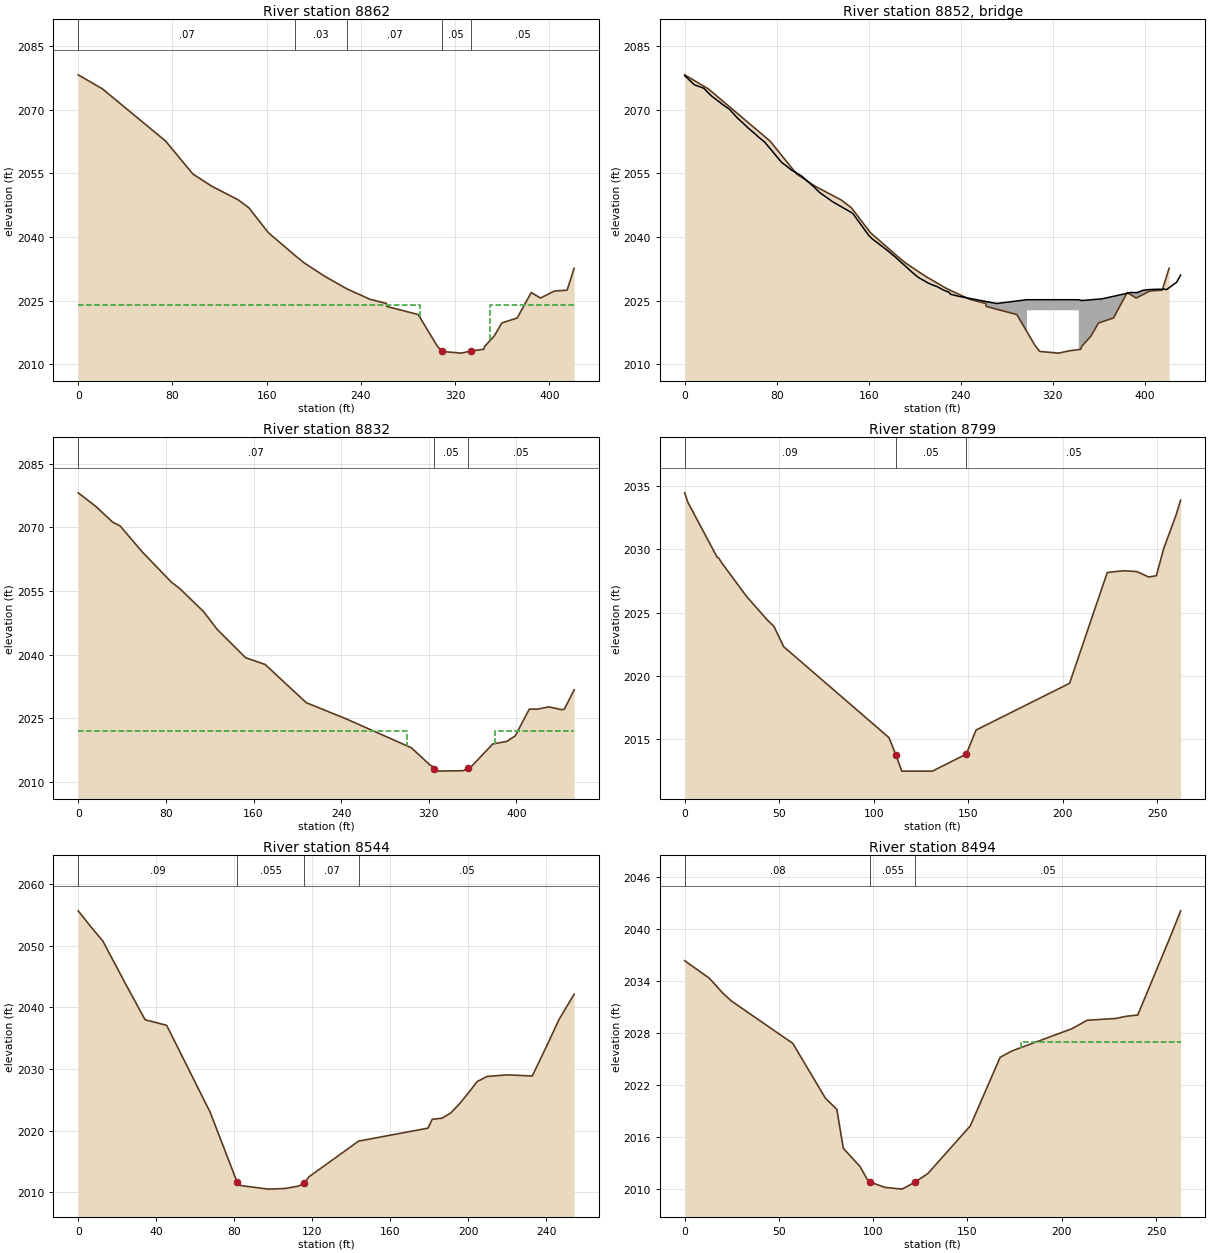
Type RM Length L Ch R = 1 ,8862    ,31.67,29.84,34.21
XS GIS Cut Line= 6
  955041.0817153  765052.6570509  954783.5999869  765003.3002508
  954703.5999868  765011.4000909  954681.1999868  765028.4998669
  954669.9001468  765032.1002509  954638.7265147  765050.9510669
#Sta/Elev= 30
       0 2078.23   20.64  2074.9   74.21 2062.61    97.4 2054.83  113.47 2051.95
  135.73 2048.77  144.89 2046.88  161.37 2041.03  184.31 2035.58  192.16 2033.82
  209.68 2030.66  228.38 2027.72  247.76 2025.29  261.72 2024.31  262.15  2023.6
  288.68  2021.7   304.3  2014.5  308.55    2013  325.22  2012.6  333.27  2013.1
  344.17  2013.5  345.14  2014.2   353.1  2016.6  359.67  2019.7  372.76  2020.9
  384.64  2026.9  392.44 2025.59  404.28 2027.24  415.09 2027.45  421.06 2032.62
#Mann= 5 ,-1 , 0
       0     .07       0  184.31     .03       0  228.38     .07       0
  308.55     .05       0  333.27     .05       0
#XS Ineff= 2 , 0
       0     290    2024     350       0    2024
Permanent Ineff=
       F       F
Bank Sta=308.55,333.27
Exp/Cntr=0.5,0.3

Type RM Length L Ch R = 3 ,8852    ,,,
Bridge Culvert--1,0,-1,-1, 0
Deck Dist Width WeirC Skew NumUp NumDn MinLoCord MaxHiCord MaxSubmerge Is_Ogee
10.5,12.9,2.6,0, 67, 66, , , 0.95, 0, 0,0,,
       0    1.15    7.71    8.25    8.78   16.37   18.78    23.5   31.07   32.45
   38.87      46   47.14   52.04   54.56   55.83   61.21   64.63   69.78   82.73
   84.72   86.91   93.12   98.38  102.25  112.67  115.98  116.46  128.74  144.89
  146.27   147.8  160.11  163.06  176.02   177.7  178.84   180.3   182.9  199.13
  203.24  208.27  210.68  214.48  219.53  224.39  226.88  229.92  229.99   230.9
   238.2   271.1   297.5   342.5   345.1   362.6   387.8  393.36  394.11  398.36
  402.69  407.77  415.47  417.43  418.69  427.58  431.05
 2077.97 2077.75 2076.06 2075.96 2075.84 2075.09 2074.47 2073.19 2071.65 2071.33
 2070.12    2068 2067.74  2066.5 2065.84 2065.55 2064.29 2063.45  2062.3 2058.07
 2057.46 2057.05  2055.7 2054.92 2054.24 2051.71 2050.82 2050.65 2048.28 2045.76
 2045.48 2044.91 2040.31 2039.54 2036.85 2036.47 2036.22 2035.87  2035.3 2031.32
 2030.44 2029.65 2029.26 2028.78 2028.27 2027.55 2027.26 2026.93 2026.92  2026.5
    2026  2024.3  2025.2  2025.2    2025  2025.4  2026.9 2026.87 2026.96 2027.42
 2027.57 2027.64 2027.67 2027.68 2027.56 2029.31    2031
                                                                                
                                                                                
                                                                                
                                                                                
                                                                                
                  2022.7  2022.7
                                                        
       0    1.15    7.71    8.25    8.78   16.37   18.78    23.5   31.07   32.45
   38.87      46   47.14   52.04   54.56   55.83   61.21   64.63   69.78   82.73
   84.72   86.91   93.12   98.38  102.25  112.67  115.98  116.46  128.74  144.89
  146.27   147.8  160.11  163.06  176.02   177.7  178.84   180.3   182.9  199.13
  203.24  208.27  210.68  214.48  219.53  224.39  226.88  229.92  229.99   230.9
   238.2   271.1   301.5   317.5   362.6   387.8  393.36  394.11  398.36  402.69
  407.77  415.47  417.43  418.69  427.58  431.05
 2077.97 2077.75 2076.06 2075.96 2075.84 2075.09 2074.47 2073.19 2071.65 2071.33
 2070.12    2068 2067.74  2066.5 2065.84 2065.55 2064.29 2063.45  2062.3 2058.07
 2057.46 2057.05  2055.7 2054.92 2054.24 2051.71 2050.82 2050.65 2048.28 2045.76
 2045.48 2044.91 2040.31 2039.54 2036.85 2036.47 2036.22 2035.87  2035.3 2031.32
 2030.44 2029.65 2029.26 2028.78 2028.27 2027.55 2027.26 2026.93 2026.92  2026.5
    2026  2024.3  2025.2    2025  2025.4  2026.9 2026.87 2026.96 2027.42 2027.57
 2027.64 2027.67 2027.68 2027.56 2029.31    2031
                                                                                
                                                                                
                                                                                
                                                                                
                                                                                
                          2022.5  2022.9
                                                
BR Coef=-1 , 0 , 0 ,, 0 ,,,0.8,0,,0,
WSPro=,,,, 1 ,,,, 0 ,,,, 0 ,,,,-1 ,-1 ,-1 , 0 , 0 , 0 , 0 , 0
BC Design=,, 0 ,, 0 ,,,,,,

Type RM Length L Ch R = 1 ,8832    ,36.09,33.93,29.94
XS GIS Cut Line= 6
  955044.5735553  765034.6745869   954808.599923  764970.1001228
  954749.1997309  764972.5003788  954665.0003068  764991.6000268
  954646.4996987  765000.5999628  954620.4163707  765032.1473549
#Sta/Elev= 30
       0 2078.15   16.05 2074.96   31.37 2071.26   38.27 2070.35   58.23  2064.3
   84.53 2057.24   92.69 2055.59   114.5 2050.16   126.7 2046.03  152.77 2039.32
  170.61 2037.72  208.09 2028.73  244.66  2024.9  304.09  2018.1  321.24    2014
  323.01  2013.8  324.58 2013.19   325.5  2012.6  351.43  2012.7  355.44 2013.25
   358.9  2013.7  378.37    2019  391.13  2019.6  398.87  2020.9  411.73  2027.2
  418.98 2027.19  429.59 2027.74     441 2027.08  443.71 2027.18  452.66 2031.76
#Mann= 3 ,-1 , 0
       0     .07       0  324.58     .05       0  355.44     .05       0
#XS Ineff= 2 , 0
       0     300    2022     380       0    2022
Permanent Ineff=
       F       F
Bank Sta=324.58,355.44
Exp/Cntr=0.5,0.3

Type RM Length L Ch R = 1 ,8799    ,281.91,254.58,231.82
XS GIS Cut Line= 6
   954815.369587  764887.6875787  954778.5997949  764924.8997387
  954720.2000508  764944.9998348  954686.2001788  764952.5999628
  954637.7997947  764977.8999308  954595.6150907  765018.7687949
#Sta/Elev= 25
       0 2034.47    1.69 2033.72   17.16 2029.38   18.02 2029.31   19.43 2028.97
   32.79 2026.26   44.08 2024.35   47.27 2023.89   52.33  2022.3  108.06  2015.1
  111.66 2013.75  114.78 2012.45  131.02 2012.45  148.93  2013.8  154.09  2015.7
  203.56  2019.4  223.47 2028.16  227.69 2028.24  232.51  2028.3  239.09 2028.24
  245.41 2027.81  249.44 2027.91  253.32 2030.05  259.88 2032.72  262.28 2033.89
#Mann= 3 ,-1 , 0
       0     .09       0  111.66     .05       0  148.93     .05       0
Bank Sta=111.66,148.93
Exp/Cntr=0.3,0.1

Type RM Length L Ch R = 1 ,8544    ,53.5,50.2,41.99
XS GIS Cut Line= 6
  954491.5326585  764762.0202505  954473.1999865  764803.5004426
  954473.3996665  764839.3998346  954467.8004345  764870.4004107
  954477.4004345  764935.8002188  954476.3876985  765010.7662349
#Sta/Elev= 30
       0 2055.69    6.97 2052.92   12.62  2050.8   23.42 2044.34   34.32    2038
   45.37  2037.1   67.68    2023   81.57  2011.6   83.12  2011.1   97.45  2010.5
  106.07  2010.6  113.15    2011  116.05  2011.5  118.39  2012.5  143.86  2018.3
  179.45  2020.4   181.6 2021.83   186.7 2022.02  191.25  2022.9  195.48 2024.31
  200.75 2026.34  204.58 2027.95  209.82  2028.8  216.83 2028.97  219.75 2029.05
  221.26 2029.04  232.96 2028.87  241.41 2034.45  246.65 2038.03  254.44 2042.16
#Mann= 4 ,-1 , 0
       0     .09       0   81.57    .055       0  116.05     .07       0
  143.86     .05       0
Bank Sta=81.57,116.05
Exp/Cntr=0.5,0.3

Type RM Length L Ch R = 1 ,8494    ,30.72,34.57,33.76
XS GIS Cut Line= 6
  954405.2514424  764749.6288265  954419.2003704  764854.4004106
  954430.6998904  764898.0996107  954431.2999544  764913.8999307
  954428.2996344  764919.3404427  954434.8788344  765008.6004749
#Sta/Elev= 25
       0 2036.34   13.04 2034.33   19.96 2032.66   24.75  2031.7   57.37  2026.8
    74.6  2020.5    80.7  2019.2   84.15  2014.7   93.04  2012.6   96.62  2011.2
   98.49  2010.8  106.27  2010.2  115.27    2010  122.16  2010.8     129  2011.8
  151.52  2017.3  167.33  2025.2  173.54 2025.93  205.44  2028.5  213.45 2029.47
  228.77 2029.68  233.91 2029.92  240.32 2030.08  258.53  2039.6  263.05 2042.09
#Mann= 3 ,-1 , 0
       0     .08       0   98.49    .055       0  122.16     .05       0
#XS Ineff= 2 , 0
       0   50.25    2027   178.5       0    2027
Permanent Ineff=
       F       F
Bank Sta=98.49,122.16
Exp/Cntr=0.5,0.3

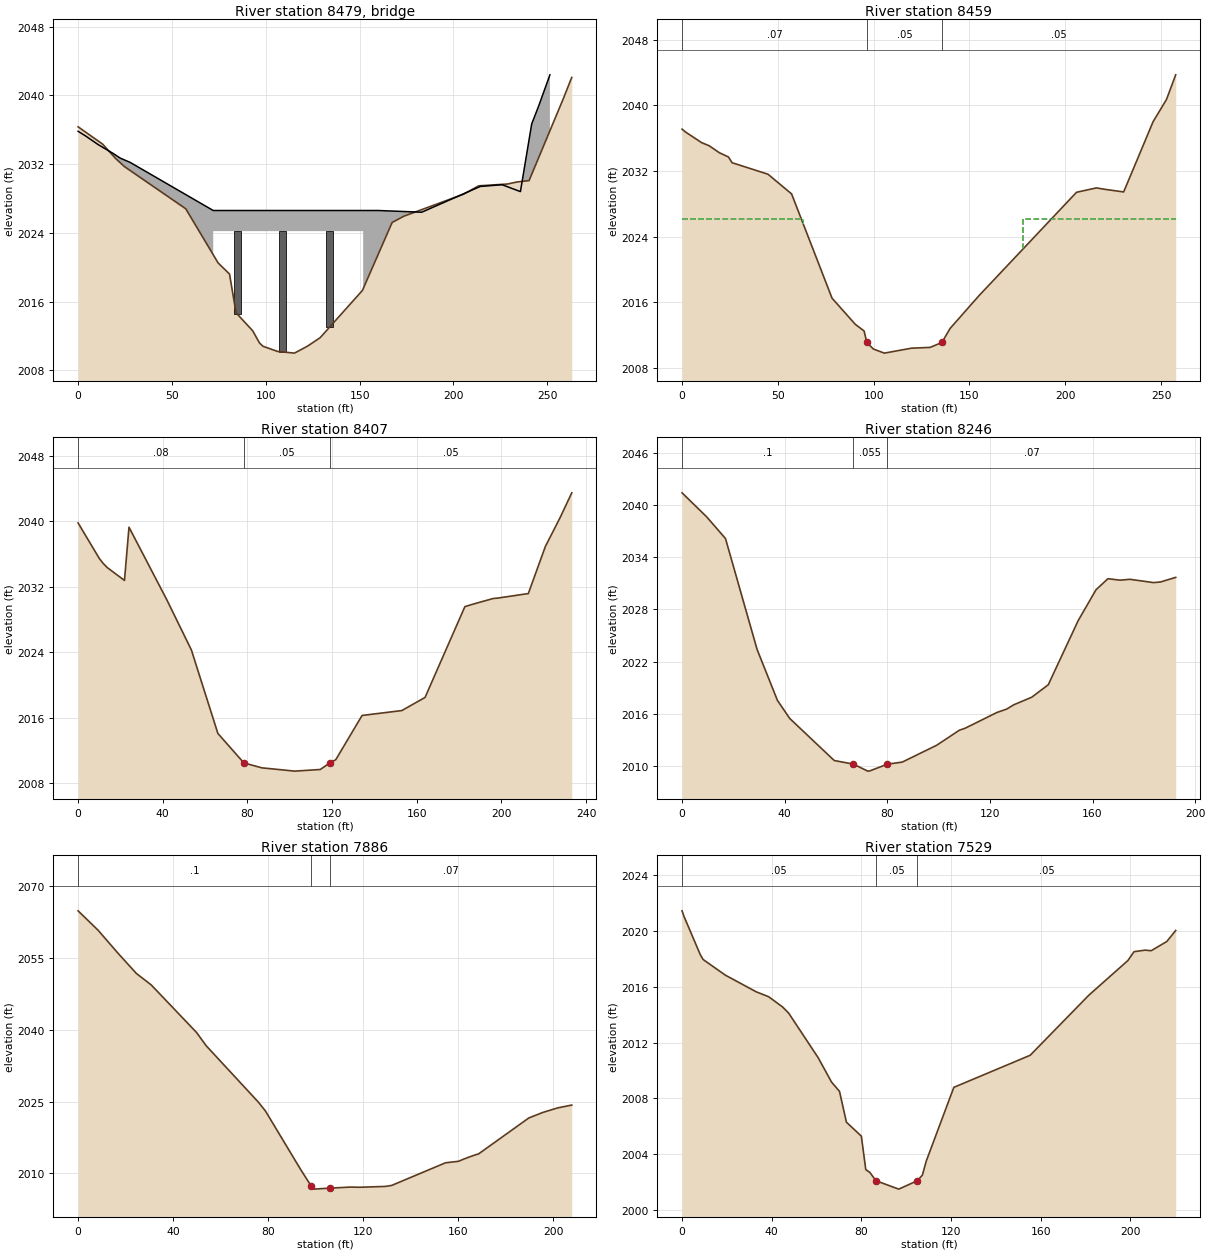
Type RM Length L Ch R = 3 ,8479    ,,,
Bridge Culvert--1,0,-1,-1, 0
Deck Dist Width WeirC Skew NumUp NumDn MinLoCord MaxHiCord MaxSubmerge Is_Ogee
9.5,12,2.6,0, 19, 19, , , 0.95, 0, 0,0,,
       0    2.63    4.29   10.82   18.22   18.47   18.68   22.43   27.73      72
   151.9   159.9   183.1   214.3   225.9   235.7   241.7   245.4  251.42
 2035.82 2035.46 2035.23 2034.25  2033.3 2033.27 2033.24  2032.7  2032.2  2026.6
  2026.6  2026.6  2026.4  2029.4  2029.6  2028.8 2036.67 2038.75 2042.39
                                                                          2024.2
  2024.2
       0    2.63    4.29   10.82   18.22   18.47   18.68   22.43    25.8      76
   155.9   160.4   181.1   211.6   222.7   231.2   241.7   245.4  251.42
 2035.82 2035.46 2035.23 2034.25  2033.3 2033.27 2033.24  2032.7  2032.2  2026.6
  2026.6  2026.6  2026.4  2029.4  2029.6  2028.8 2036.67 2038.75 2042.39
                                                                          2024.2
  2024.2
Pier Skew, UpSta & Num, DnSta & Num=  ,85, 6 ,87, 6 , 0 , 0 , 0 ,,
       4       4       2       2      .5      .5
    2014    2016    2016  2023.2  2023.2  2024.2
       4       4       2       2      .5      .5
    2014    2016    2016  2023.2  2023.2  2024.2
Pier Skew, UpSta & Num, DnSta & Num=  ,109, 6 ,111, 6 , 0 , 0 , 0 ,,
       4       4       2       2      .5      .5
    2010    2012    2012  2023.2  2023.2  2024.2
       4       4       2       2      .5      .5
    2010    2012    2012  2023.2  2023.2  2024.2
Pier Skew, UpSta & Num, DnSta & Num=  ,134, 6 ,137, 6 , 0 , 0 , 0 ,,
       4       4       2       2      .5      .5
    2013    2015    2015  2023.2  2023.2  2024.2
       4       4       2       2      .5      .5
    2013    2015    2015  2023.2  2023.2  2024.2
BR Coef=-1 , 1 , 0 ,, 0 ,,,0.8,0,2,0,
WSPro=,,,, 1 ,,,, 0 ,,,, 0 ,,,,-1 ,-1 ,-1 , 0 , 0 , 0 , 0 , 0
BC Design=,, 0 ,, 0 ,,,,,,

Type RM Length L Ch R = 1 ,8459    ,60.29,52.6,55.65
XS GIS Cut Line= 6
  954366.5923704  764754.5645065  954368.9004664  764780.5997065
  954389.2002424  764841.6004106  954386.0995704  764870.4997387
  954394.8998264  764887.8995467  954399.2589944  765005.4895628
#Sta/Elev= 28
       0 2037.09     1.9 2036.73    10.2 2035.45   14.13 2035.07   19.46 2034.22
   24.21  2033.7   26.13    2033   44.86  2031.6   57.18  2029.2   78.28  2016.5
   90.46  2013.3   95.03  2012.5   96.42  2011.1   99.87  2010.3  105.59  2009.8
  119.71  2010.4   129.5  2010.5  135.66  2011.1  139.88  2012.8  154.98  2016.8
   205.9  2029.4  216.27 2029.93   220.7 2029.76  230.49 2029.44  235.77 2032.37
  245.86    2038  252.86 2040.71  257.66 2043.71
#Mann= 3 ,-1 , 0
       0     .07       0   96.42     .05       0  135.66     .05       0
#XS Ineff= 2 , 0
       0    63.2  2026.2     178       0  2026.2
Permanent Ineff=
       F       F
Bank Sta=96.42,135.66
Exp/Cntr=0.5,0.3

Type RM Length L Ch R = 1 ,8407    ,161.99,160.34,158.32
XS GIS Cut Line= 6
  954319.4330743  764776.4924425  954330.7001463  764828.7000586
  954328.4995703  764853.3999626  954340.7998583  764907.6002827
  954356.7998583  764953.3997068  954357.3302903  765003.8767628
#Sta/Elev= 28
       0 2039.82   10.05 2035.47   11.72 2034.92   13.76 2034.37   21.91  2032.8
   24.05  2039.3   41.98  2030.4   53.53  2024.3   66.05  2014.1   78.34  2010.5
   86.86  2009.9  102.41  2009.5  114.43  2009.7  118.93  2010.5  121.75  2010.9
  134.18  2016.3  152.96  2016.9  163.92  2018.5  182.76  2029.6  188.21 2030.02
  196.16 2030.59  198.26 2030.64   212.1 2031.17  212.69 2031.18   212.9 2031.32
  220.78 2036.95  227.74 2040.47  233.24  2043.5
#Mann= 3 ,-1 , 0
       0     .08       0   78.34     .05       0  118.93     .05       0
Bank Sta=78.34,118.93
Exp/Cntr=0.3,0.1

Type RM Length L Ch R = 1 ,8246    ,366.36,360.51,348.69
XS GIS Cut Line= 4
  954161.1533941  764845.2448266  954176.2717301  764897.5302667
  954187.6104821  764947.9254028  954233.5962742  765020.9990669
#Sta/Elev= 28
       0  2041.4    9.53 2038.66   16.93 2036.15   29.26 2023.39   37.18 2017.54
   41.96 2015.47   59.32 2010.63   66.75 2010.22   72.39 2009.41   73.12 2009.43
   80.05 2010.21   85.85 2010.45   99.29 2012.39  108.02  2014.1  110.48 2014.36
  122.72 2016.15   126.6 2016.55  129.26 2017.03  136.33 2017.91  142.75 2019.34
  154.39  2026.7  161.34 2030.25  165.99 2031.53  170.73 2031.36  174.58 2031.46
  183.81 2031.08  186.46 2031.15  192.42 2031.68
#Mann= 3 , 0 , 0
       0      .1       0   66.75    .055       0   80.05     .07       0
Bank Sta=66.75,80.05
Exp/Cntr=0.3,0.1

Type RM Length L Ch R = 1 ,7886    ,355.61,356.83,362.71
XS GIS Cut Line= 4
  953840.6895216  765034.5619469  953889.9039857   765119.210907
  953912.5425777   765144.802715  953972.5837938  765191.0639631
#Sta/Elev= 26
       0  2064.9    8.43 2060.84   16.81 2056.04   24.54 2051.81   30.78 2049.42
   49.89 2039.47   53.93 2036.71   75.78 2024.99   78.88 2023.08    93.8 2010.77
   98.06 2007.45   99.02 2006.73   105.9 2006.93  114.69 2007.16  118.65 2007.12
  129.52  2007.3  132.09 2007.51  154.76 2012.24  160.13 2012.54  163.96 2013.31
  167.83 2013.99  168.53 2014.05   189.8  2021.6   195.6 2022.74  202.06 2023.72
  207.89  2024.3
#Mann= 3 , 0 , 0
       0      .1       0   98.06    .055       0   105.9     .07       0
Bank Sta=98.06,105.9
Exp/Cntr=0.3,0.1

Type RM Length L Ch R = 1 ,7529    ,68.59,67.07,67.96
XS GIS Cut Line= 6
  953553.5619692  765237.4634512  953586.4999533  765303.0004753
  953595.9996013  765312.0997393  953604.9995373  765328.0997393
  953607.3997933  765344.0997393  953669.6784494  765420.8137234
#Sta/Elev= 30
       0 2021.46     .82 2021.08    8.18  2018.3     9.4 2017.97   19.29 2016.85
   33.12 2015.65   38.64  2015.3    44.9 2014.56   47.59 2014.12    60.8 2010.91
   66.69 2009.18   70.26 2008.51   73.35  2006.3      80  2005.3   81.98  2002.9
   83.79  2002.7   86.54  2002.1   96.69  2001.5  104.93  2002.1  107.22  2002.5
  108.94  2003.5  121.27  2008.8  155.33  2011.1  181.45  2015.4  198.96  2017.9
  201.66 2018.53  206.62 2018.64  209.33  2018.6  216.28 2019.26  220.26 2020.05
#Mann= 3 ,-1 , 0
       0     .05       0   86.54     .05       0  104.93     .05       0
Bank Sta=86.54,104.93
Exp/Cntr=0.5,0.3

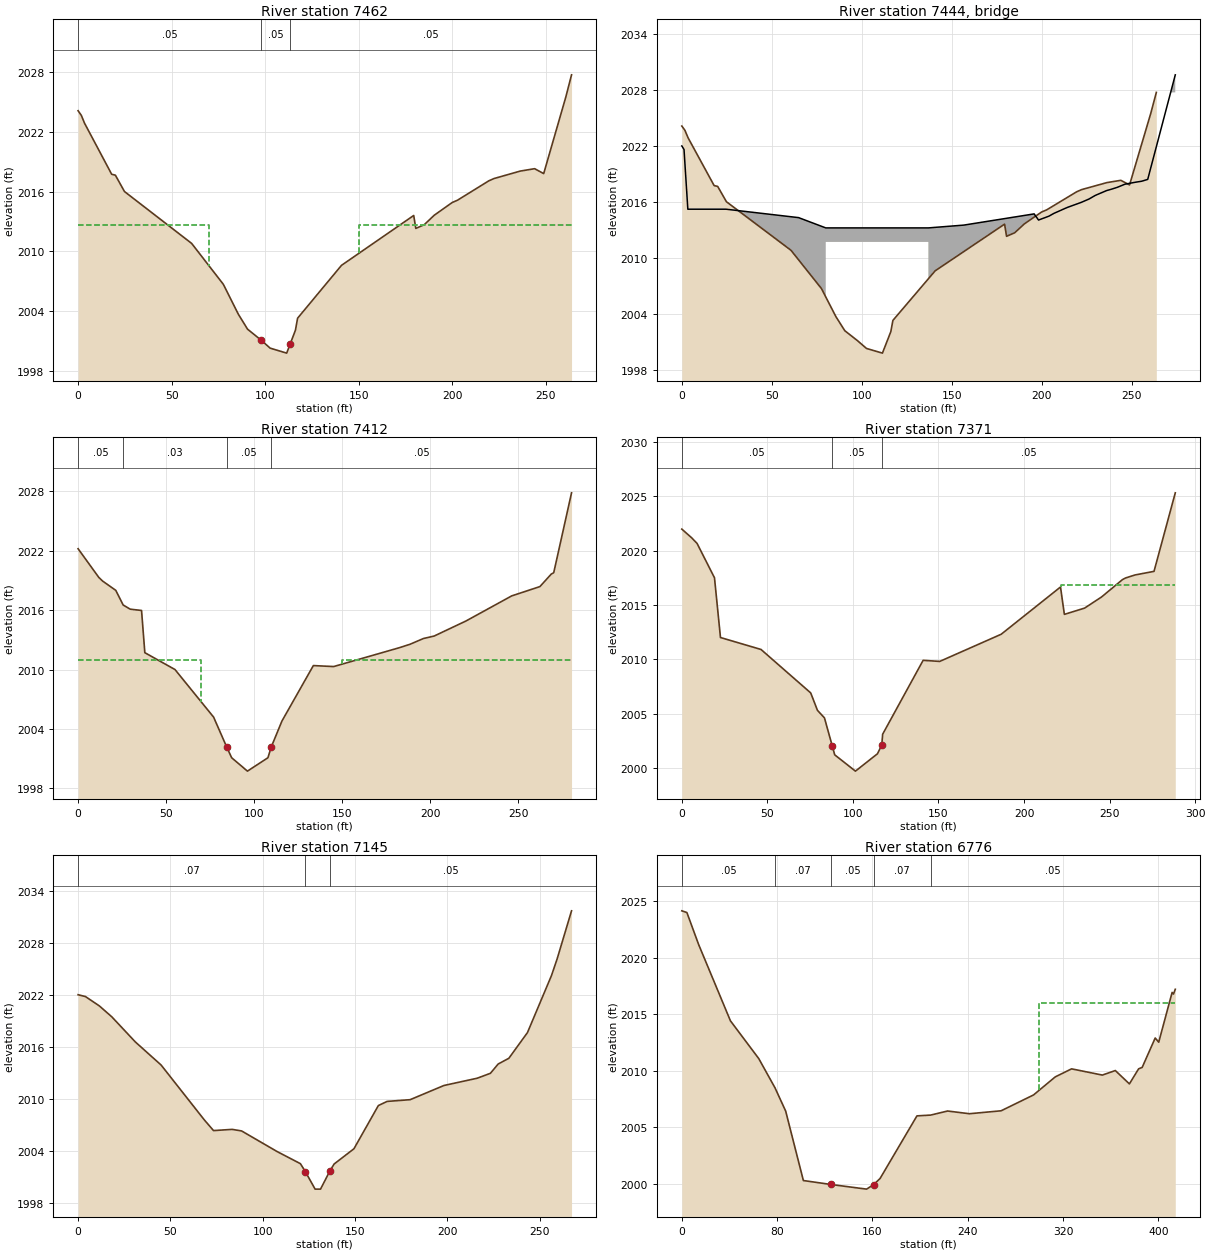
Type RM Length L Ch R = 1 ,7462    ,44.89,49.53,43.58
XS GIS Cut Line= 6
  953479.1724651  765254.8079632  953527.3997932  765335.9998993
  953537.1001452  765344.0997393  953541.5002732  765364.3995153
  953579.9996013  765420.2003474  953621.2115053  765473.3735955
#Sta/Elev= 30
       0  2024.1    1.72 2023.64    3.48 2022.84   17.95 2017.73   19.93 2017.64
   24.79    2016   60.68  2010.8   77.62  2006.7   85.64  2003.7   90.57  2002.2
    97.7 2001.12  102.63  2000.3  111.48  1999.8  113.272000.681  116.15  2002.1
   117.3  2003.3  140.76  2008.6  179.36  2013.6  180.47  2012.3  185.02 2012.68
   190.3 2013.62  199.93  2014.9  202.76 2015.13  219.47 2017.07  222.23  2017.3
  236.28 2018.05  243.96 2018.29  248.82  2017.8  260.63 2025.47   263.7  2027.7
#Mann= 3 , 0 , 0
       0     .05       0    97.7     .05       0  113.27     .05       0
#XS Ineff= 2 , 0
       0      70 2012.65     150       0 2012.65
Permanent Ineff=
       F       F
Bank Sta=97.7,113.27
Exp/Cntr=0.5,0.3

Type RM Length L Ch R = 3 ,7444    ,,,
Bridge Culvert--1,0,-1,-1, 0
Deck Dist Width WeirC Skew NumUp NumDn MinLoCord MaxHiCord MaxSubmerge Is_Ogee
11,12,2.6,0, 27, 28, , , 0.95, 0, 0,0,,
       0     .05    1.22    3.34   24.62    64.9      80     137   156.7   195.8
  198.23  204.04  206.73  212.21  214.37  220.24  222.08  226.29   229.8     236
  238.75  241.99  246.29  251.87  255.47  258.91  274.23
 2021.97 2021.96 2021.59  2015.2  2015.2  2014.3  2013.2  2013.2  2013.5  2014.7
 2014.04 2014.46 2014.75 2015.22  2015.4 2015.81 2015.94 2016.29 2016.68 2017.19
 2017.34 2017.54 2017.88 2018.08 2018.19 2018.39 2029.58
                                                  2011.7  2011.7
                                                                                
                                                        
       0     .05    1.22   12.21    13.7   33.67    66.9      75     135   153.8
     194  198.23  204.04  206.73  212.21  214.37  220.24  222.08  226.29   229.8
     236  238.75  241.99  246.29  251.87  255.47  258.91  274.23
 2021.97 2021.96 2021.59 2019.21  2015.2  2015.2  2014.3  2013.2  2013.2  2013.5
  2014.7 2014.04 2014.46 2014.75 2015.22  2015.4 2015.81 2015.94 2016.29 2016.68
 2017.19 2017.34 2017.54 2017.88 2018.08 2018.19 2018.39 2029.58
                                                          2011.7  2011.7
                                                                                
                                                                
BR Coef=-1 , 0 , 0 ,, 0 ,,,0.8,0,,0,
WSPro=,,,, 1 ,,,, 0 ,,,, 0 ,,,,-1 ,-1 ,-1 , 0 , 0 , 0 , 0 , 0
BC Design=,, 0 ,, 0 ,,,,,,

Type RM Length L Ch R = 1 ,7412    ,43.59,41.12,39.76
XS GIS Cut Line= 6
  953440.0106091  765263.9870992  953477.5002731  765322.5998353
  953493.3999211  765369.2000274  953524.0001132  765417.6004114
  953540.1997932  765451.1998995  953584.6127213  765500.2372115
#Sta/Elev= 28
       0 2022.19   11.75  2019.3   13.91 2018.93    21.4 2017.99   25.61 2016.51
   29.62 2016.09   36.04 2015.96   37.91  2011.7   55.03    2010   76.96  2005.2
   84.36  2002.2   87.22  2001.1   96.18 1999.75  107.81  2001.1  109.74  2002.2
  115.76  2004.8  133.61  2010.4  145.12  2010.3   182.4  2012.2  188.52 2012.55
  196.13 2013.13  202.22 2013.38   220.3  2014.9  246.25 2017.43  262.27 2018.37
  268.72 2019.63  270.12 2019.77  280.24 2027.83
#Mann= 4 ,-1 , 0
       0     .05       0   25.61     .03       0   84.36     .05       0
  109.74     .05       0
#XS Ineff= 2 , 0
       0      70    2011     150       0    2011
Permanent Ineff=
       F       F
Bank Sta=84.36,109.74
Exp/Cntr=0.5,0.3

Type RM Length L Ch R = 1 ,7371    ,219.74,225.71,235.91
XS GIS Cut Line= 6
   953392.281969  765284.1803792  953449.1999851  765376.3004434
  953484.0999531  765426.8000274  953507.1000171  765466.2004755
  953527.4796652  765494.2601235  953554.1763692  765521.2742676
#Sta/Elev= 27
       0 2021.98    5.75 2021.18    8.92 2020.66   19.09  2017.5   22.59    2012
   46.29  2010.9   75.33  2006.9   79.27  2005.3   83.37  2004.6   87.96    2002
   89.36  2001.2  101.48  1999.7  114.36  2001.3  116.85  2002.1  117.39  2003.1
  141.04  2009.9  150.74  2009.8  186.66  2012.3  221.33 2016.65   223.6 2014.13
  235.44 2014.71  245.31 2015.73  257.54 2017.33  259.34 2017.48  264.91 2017.76
  275.99 2018.09  288.42 2025.32
#Mann= 3 ,-1 , 0
       0     .05       0   87.96     .05       0  116.85     .05       0
#XS Ineff= 2 , 0
       0                  221.33       0  2016.8
Permanent Ineff=
       F       F
Bank Sta=87.96,116.85
Exp/Cntr=0.3,0.1

Type RM Length L Ch R = 1 ,7145    ,325.66,369.19,412.3
XS GIS Cut Line= 6
  953260.7553128  765333.3180433  953241.3740648  765398.9175314
  953241.3740648  765438.4254995  953248.8287848  765477.9344915
  953260.0108648  765513.7150996  953277.9011688  765593.4775317
#Sta/Elev= 30
       0 2022.06    3.98 2021.85   11.52 2020.77   18.26 2019.51   31.01 2016.61
   44.99 2013.94   68.41  2007.6   73.38 2006.37   83.49 2006.51   88.59 2006.33
  107.91 2003.94  120.45 2002.55  123.11 2001.64  128.41 1999.61  131.35 1999.61
  136.47 2001.73  138.71 2002.51  149.45 2004.27  162.68 2009.26  167.43 2009.74
  179.91 2009.94  198.23 2011.58  216.27 2012.42  223.41 2012.99  227.61 2014.06
  233.38 2014.72  243.47 2017.69  256.49 2024.28  259.53 2026.19  267.35 2031.75
#Mann= 3 ,-1 , 0
       0     .07       0  123.11     .05       0  136.47     .05       0
Bank Sta=123.11,136.47
Exp/Cntr=0.3,0.1

Type RM Length L Ch R = 1 ,6776    ,277,284.11,292.78
XS GIS Cut Line= 6
  953289.8276968  765263.2467472  953213.0471527  765248.3383312
  953167.5754087  765236.4107792  953121.3581926  765217.0295311
  953096.0131686  765219.2659471  952884.4496483  765246.8709392
#Sta/Elev= 30
       0 2024.13    4.25 2023.98    14.1 2021.15   40.79  2014.4   64.55 2011.06
   78.21 2008.47   87.17 2006.41  102.01 2000.27  125.22 1999.92  155.07 1999.51
  160.98 1999.91  166.38 2000.45  197.33 2005.99  208.81 2006.06  223.08 2006.42
  241.35 2006.18  267.97 2006.44  295.15 2007.84  313.42 2009.44  327.09 2010.15
  352.93  2009.6  363.82    2010  375.63 2008.82  383.36 2010.15  386.36 2010.28
  397.28 2012.88  400.25 2012.51  411.48 2016.91  412.65 2016.77  414.14 2017.19
#Mann= 5 ,-1 , 0
       0     .05       0   78.21     .07       0  125.22     .05       0
  160.98     .07       0  208.81     .05       0
#XS Ineff= 2 , 0
       0                     300       0    2016
Permanent Ineff=
       F       F
Bank Sta=125.22,160.98
Exp/Cntr=0.3,0.1