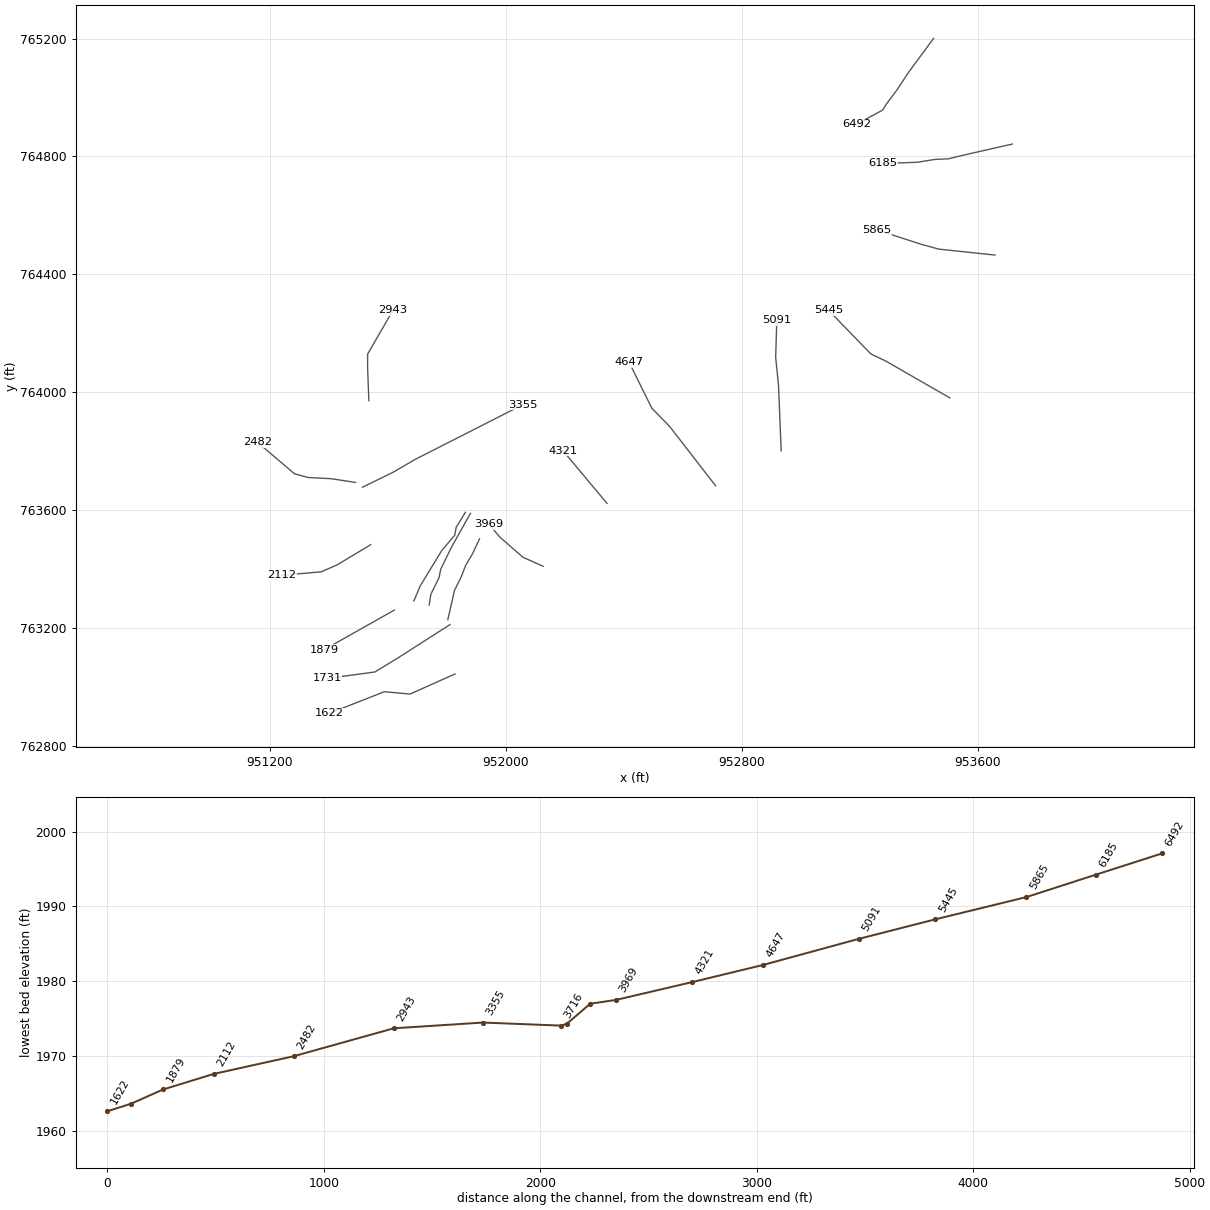
HEC-RAS study dtl_little_ivy_crk.prj: dtl_Little_Ivy_Crk

--- dtl_little_ivy_crk.g01 (geometry) --- (continued)

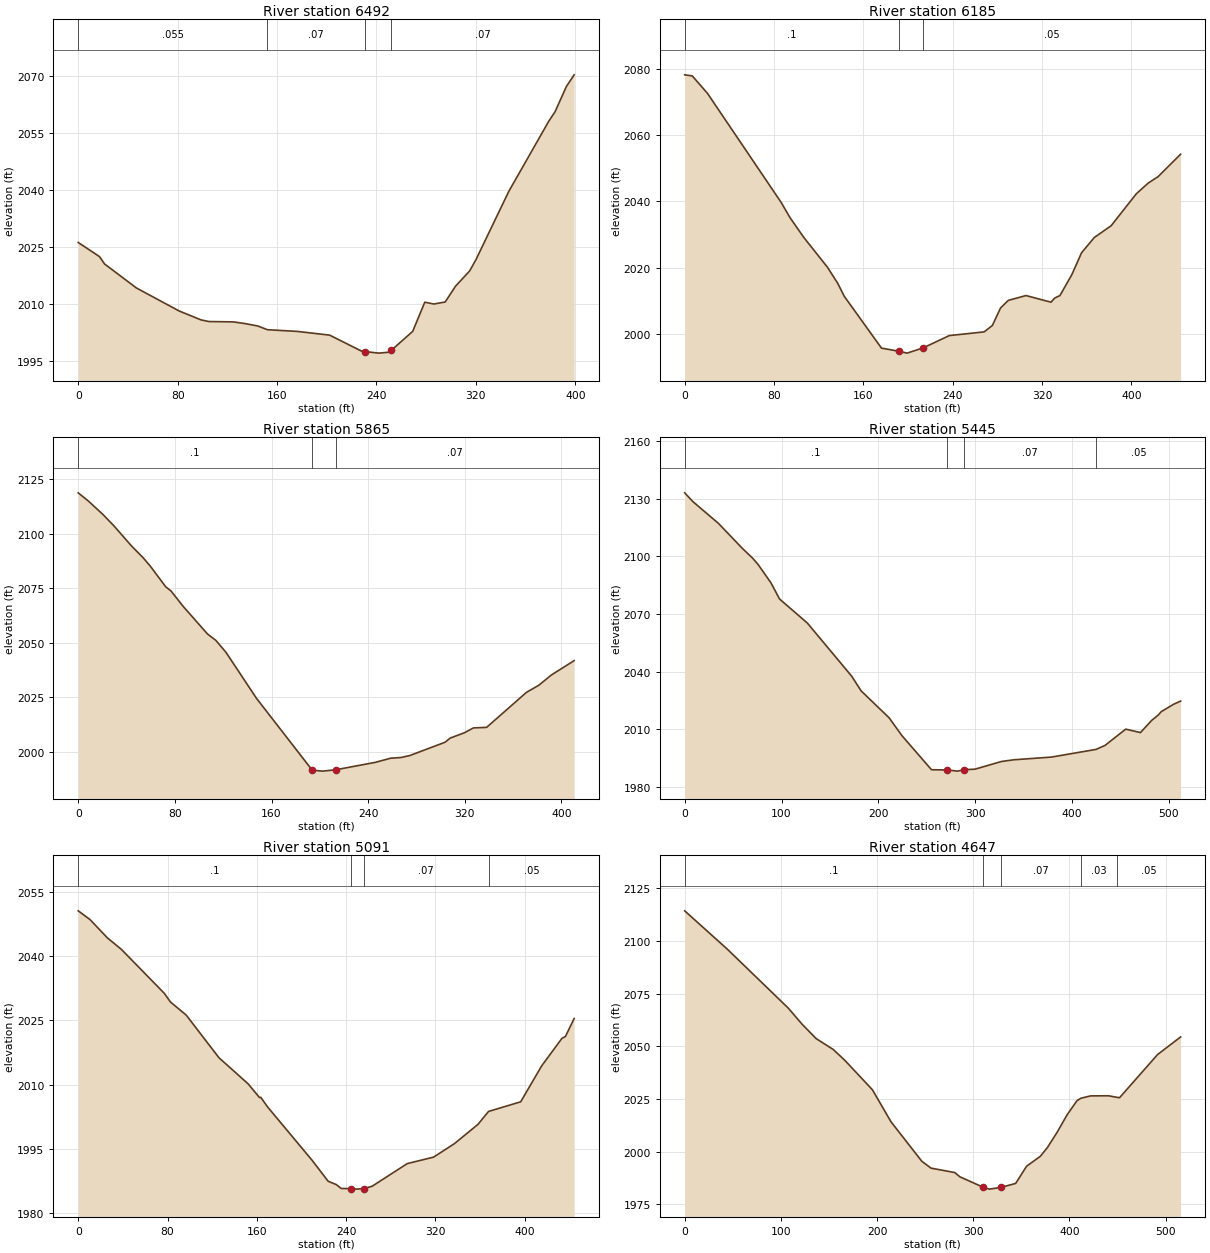
Type RM Length L Ch R = 1 ,6492    ,322.38,306.84,294.23
XS GIS Cut Line= 6
  953450.8435051  765200.6301711   953364.371825   765082.849691
  953327.1002729  765026.1968909  953289.8276968  764976.2523148
  953278.6466408  764957.6155148  953189.9385447  764909.1618827
#Sta/Elev= 30
       0 2026.18   17.13 2022.47   21.18 2020.54    46.9 2014.21   81.27 2008.17
   98.87 2005.83  105.12  2005.4  124.64 2005.31  133.99 2004.88   144.5 2004.23
  152.22 2003.26  176.18 2002.81  202.32 2001.83  227.97 1997.63  230.61 1997.51
  241.97  1997.1  250.42 1997.36  251.84  1997.8  269.12 2002.81  278.87 2010.48
   286.2 2010.01  295.29 2010.54  303.58 2014.68  314.99 2018.71  320.17 2021.75
  346.45  2039.6  378.51 2057.98  383.76 2060.58   392.8 2067.17  399.05 2070.24
#Mann= 4 ,-1 , 0
       0    .055       0  152.22     .07       0  230.61     .05       0
  251.84     .07       0
Bank Sta=230.61,251.84
Exp/Cntr=0.3,0.1

Type RM Length L Ch R = 1 ,6185    ,328.6,320.05,311.24
XS GIS Cut Line= 6
  953717.7112174  764842.0724746  953547.0052972  764803.3089546
  953501.5335531  764792.1278985  953455.3163371  764789.8914825
   953394.935153  764780.2003465  953280.1375848  764776.4740105
#Sta/Elev= 30
       0 2078.22     6.8 2077.89   20.35 2072.66   86.47 2039.69   94.43 2035.08
  106.87 2029.08  127.75 2020.22  137.02 2015.35  142.86 2011.43  176.27 1995.76
  192.14  1994.8  199.16 1994.25  213.55 1995.82  236.97 1999.54  268.21 2000.66
  275.54 2002.58  282.89 2007.87   289.8 2010.16   305.7 2011.62   328.1 2009.62
  331.47 2010.89  336.06 2011.61  346.74 2017.93  355.45 2024.54  366.82 2029.13
  381.97 2032.69  404.41  2042.3   415.1 2045.55  424.04 2047.51  444.16 2054.27
#Mann= 3 ,-1 , 0
       0      .1       0  192.14    .055       0  213.55     .05       0
Bank Sta=192.14,213.55
Exp/Cntr=0.3,0.1

Type RM Length L Ch R = 1 ,5865    ,423.04,420.03,416.86
XS GIS Cut Line= 5
  953658.8220014  764465.6244741  953467.9883371  764485.7511941
  953438.9159531  764493.9513861   953411.334513  764501.4050821
  953259.2653928  764550.6041862
#Sta/Elev= 30
       0 2118.79    8.47    2115   20.47 2108.87   29.65 2103.61   44.16 2094.41
   53.62 2089.12   59.67  2085.2   72.42 2075.74   76.95 2073.74   86.77 2066.82
  107.06 2054.08  113.93 2051.18  122.26 2045.74  147.57 2024.61  193.68  1991.7
  202.41 1991.26  213.03 1991.86  246.01 1995.29  258.74 1997.19  267.03 1997.49
  274.46  1998.4  303.66  2004.5  307.89  2006.4   319.7 2008.85  327.09 2011.06
  338.06 2011.32  370.95 2027.33  381.25 2030.62  391.74 2035.35  410.49 2041.89
#Mann= 3 ,-1 , 0
       0      .1       0  193.68    .055       0  213.03     .07       0
Bank Sta=193.68,213.03
Exp/Cntr=0.3,0.1

Type RM Length L Ch R = 1 ,5445    ,371.53,354.25,337.71
XS GIS Cut Line= 4
  953506.0063851  763981.0871294  953289.8276968  764105.5758336
  953238.3921768  764130.1753856  953095.2676966  764277.7726978
#Sta/Elev= 30
       0 2133.09    8.48 2128.52   34.92 2117.17   59.83 2104.04   70.13 2099.12
   75.78 2095.82   89.07 2086.28   97.96 2077.85  126.68 2065.33   172.4 2037.71
  182.21 2030.04  211.15    2016  224.33 2006.75  254.86 1989.02  271.09 1988.89
  281.79 1988.29   288.9 1989.06  299.69  1989.3  327.01 1993.29  339.99  1994.2
  378.76  1995.6  424.86  1999.6  434.17 2001.72   455.4 2010.14  470.59 2008.35
  482.13 2014.65  489.06  2017.5  492.08 2019.24  504.64 2023.02  512.08 2024.74
#Mann= 4 ,-1 , 0
       0      .1       0  271.09    .055       0   288.9     .07       0
  424.86     .05       0
Bank Sta=271.09,288.9
Exp/Cntr=0.3,0.1

Type RM Length L Ch R = 1 ,5091    ,428.71,443.76,454.07
XS GIS Cut Line= 4
  952934.2518883  763801.4355452  952925.3072483  764022.8315135
  952915.6161123  764118.9943296  952919.3434723  764244.9739778
#Sta/Elev= 30
       0 2050.56   10.55 2048.53   26.15 2044.25   38.81 2041.54   77.21  2031.3
   82.67 2029.29   96.79 2026.24  126.07 2016.31  152.17 2010.23  162.46 2007.01
  163.55 2007.08  169.47 2004.89  209.66 1992.35  223.85 1987.52  231.24 1986.72
  235.61 1985.82  244.18 1985.78  249.82 1985.67  255.63  1985.8  263.22 1986.33
  294.76 1991.62  318.33 1993.13  336.95 1996.26  358.15 2000.78  367.58 2003.78
  396.37 2006.03  415.18 2014.41  433.28 2020.81  436.47 2021.27  444.26 2025.45
#Mann= 4 ,-1 , 0
       0      .1       0  244.18    .055       0  255.63     .07       0
  367.58     .05       0
Bank Sta=244.18,255.63
Exp/Cntr=0.3,0.1

Type RM Length L Ch R = 1 ,4647    ,327.72,325.76,324.73
XS GIS Cut Line= 4
   952712.110448   763682.910617  952556.3129438  763884.1798653
  952495.9327837  763946.0519934  952418.4067676  764102.5939456
#Sta/Elev= 30
       0 2114.35   44.26 2096.17  107.69 2068.16  122.01 2060.53  136.71 2053.67
  154.61 2048.45   166.5 2043.36  195.17 2029.38  214.48  2014.2  246.47 1995.46
  256.06 1992.15  280.91 1990.03  286.17 1988.02  310.29 1983.09  316.94 1982.17
  329.25 1983.03  344.15 1984.88   355.5 1993.03   369.8 1997.77  377.13  2001.9
  387.13 2009.07  397.88 2017.64  407.91 2024.17  412.03 2025.34  422.04 2026.46
  440.66  2026.5  450.03 2025.73  452.18 2025.59  491.71 2046.09  515.67 2054.45
#Mann= 5 ,-1 , 0
       0      .1       0  310.29    .055       0  329.25     .07       0
  412.03     .03       0  450.03     .05       0
Bank Sta=310.29,329.25
Exp/Cntr=0.3,0.1

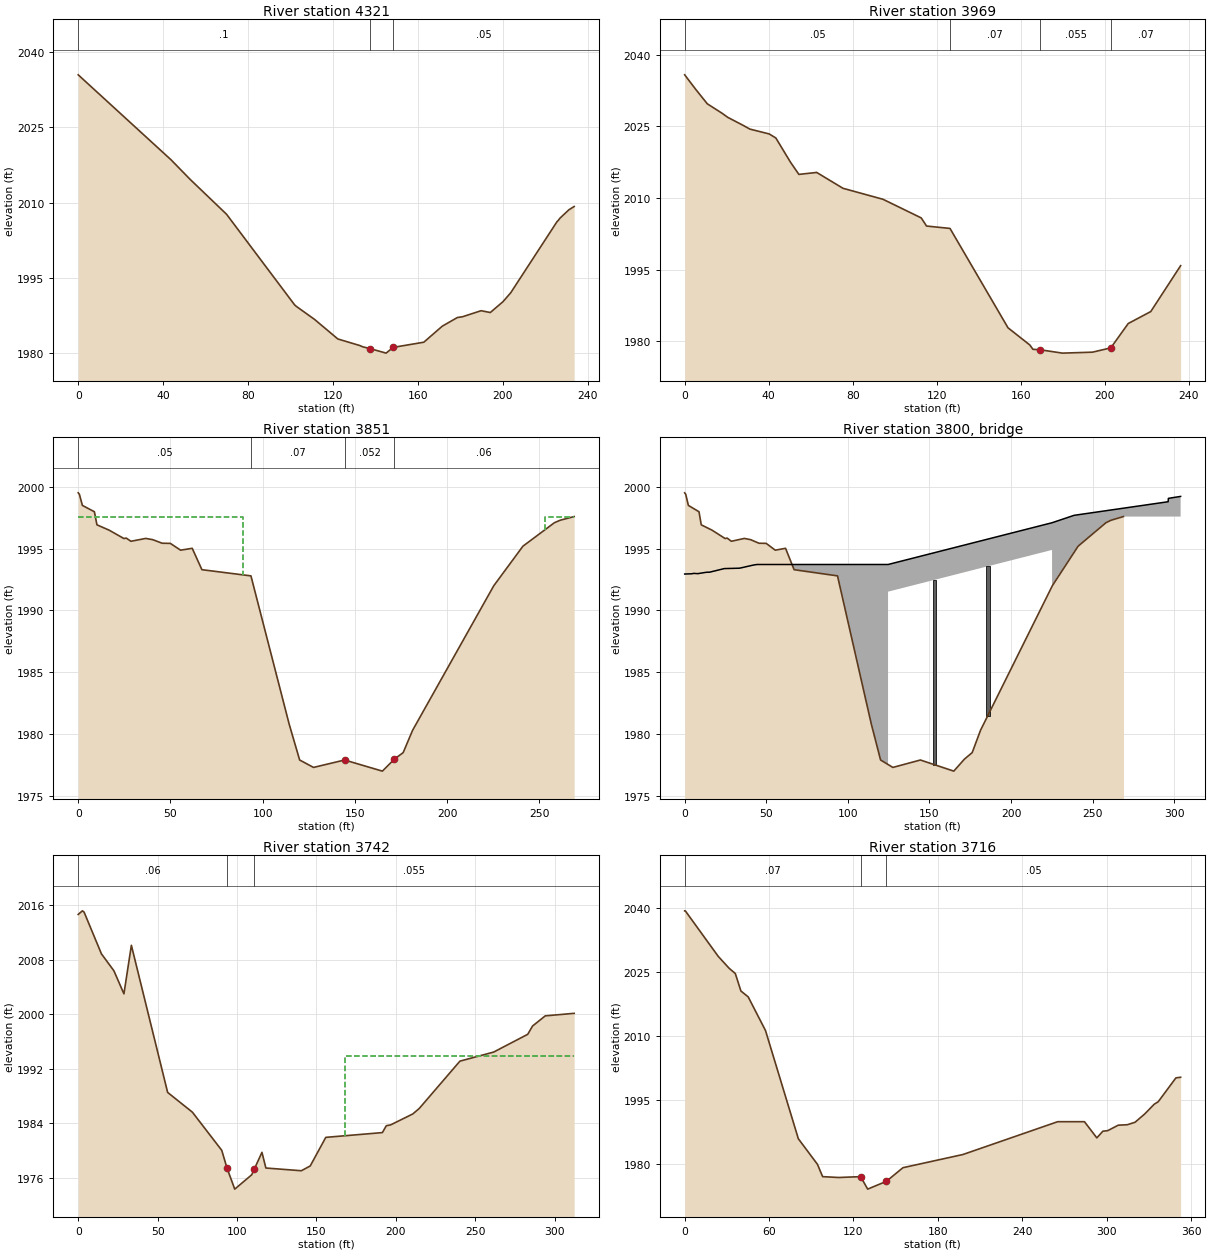
Type RM Length L Ch R = 1 ,4321    ,348.85,352.68,353
XS GIS Cut Line= 2
  952344.0315995  763623.3250809  952194.1435993  763802.6213372
#Sta/Elev= 26
       0 2035.53   43.72 2018.55   52.81  2014.6   69.91 2007.65   101.9 1989.58
  102.64 1989.28  111.34 1986.64  122.35 1982.72  132.67 1981.41  134.16 1981.14
   137.4 1980.81  145.09 1979.89  148.43 1981.04  162.85 1982.07  171.56 1985.28
  178.68 1987.01  181.07 1987.16  189.84 1988.37  194.19 1988.01  200.12 1990.16
   203.8 1991.95  225.65 2006.19  226.18  2006.4  226.99 2006.86  231.26 2008.56
   233.7  2009.2
#Mann= 3 ,-1 , 0
       0      .1       0   137.4    .055       0  148.43     .05       0
Bank Sta=137.4,148.43
Exp/Cntr=0.3,0.1

Type RM Length L Ch R = 1 ,3969    ,167.76,118.14,69.87
XS GIS Cut Line= 6
  952127.3542232  763409.9849206  952058.5997911  763440.8001527
   951980.200303  763509.5003128   951959.999855  763533.4004728
   951954.199919  763542.4004088  951943.9926831  763552.3074017
#Sta/Elev= 29
       0 2035.75    5.31 2032.68   10.78 2029.68   17.76 2027.72   20.56 2026.84
    27.8 2025.18   31.04 2024.39   40.22 2023.38    43.4 2022.53   50.43 2017.42
   54.37 2014.91    62.5  2015.3    62.7 2015.35   62.91  2015.3   75.36    2012
   94.41  2009.7  112.61  2005.8  115.14  2004.1   126.3  2003.6  153.92  1982.8
  164.31  1979.2  165.77  1978.3  169.24  1978.2  179.84  1977.5  194.13  1977.7
  202.84  1978.6  211.15  1983.7  221.87  1986.2  236.08  1995.8
#Mann= 4 ,-1 , 0
       0     .05       0   126.3     .07       0  169.24    .055       0
  202.84     .07       0
Bank Sta=169.24,202.84
Exp/Cntr=0.5,0.3

Type RM Length L Ch R = 1 ,3851    ,90.16,108.79,113.65
XS GIS Cut Line= 6
  951804.3293268  763228.9406964  951826.9003348  763328.0997365
  951849.9997268  763374.8002806  951864.8999509  763413.2996086
  951888.0003669  763452.4000247  951911.8217967   763503.127793
#Sta/Elev= 30
       0 1999.52    .643  1999.4   2.284  1998.5   8.773 1997.99   10.16 1996.93
  16.749  1996.5  24.797 1995.82  26.002 1995.86  28.585  1995.6  36.606 1995.83
  40.412 1995.73  45.551 1995.44  49.938 1995.43  55.511 1994.88  61.819 1995.03
  67.059  1993.3  93.647  1992.8 114.379  1980.8 120.055  1977.9 127.579  1977.3
 144.442  1977.9 164.903    1977 171.416 1977.97 176.189  1978.5 181.273  1980.3
 225.292    1992 241.095  1995.2 258.147  1997.1  261.26  1997.3 268.875  1997.6
#Mann= 4 ,-1 , 0
       0     .05       0  93.647     .07       0 144.442    .052       0
 171.416     .06       0
#XS Ineff= 2 , 0
       0   89.55  1997.6  253.22       0  1997.6
Permanent Ineff=
       F       F
Bank Sta=144.442,171.416
Skew Angle= 25
Exp/Cntr=0.5,0.3

Type RM Length L Ch R = 3 ,3800    ,,,
Bridge Culvert--1,0,-1,-1, 0
Deck Dist Width WeirC Skew NumUp NumDn MinLoCord MaxHiCord MaxSubmerge Is_Ogee
28,24.6,2.6,25, 20, 19, , , 0.95, 0, 0,0,,
       0   4.359   5.429   8.048  13.232  15.317  22.766  24.371  33.497  35.292
  41.953  44.228  50.209 124.617 225.127 238.631 296.272 296.399  298.13 303.903
 1992.95 1992.97    1993 1992.98 1993.09  1993.1 1993.34 1993.39 1993.42 1993.47
 1993.67 1993.72 1993.72 1993.72  1997.1  1997.7  1998.8 1999.07 1999.11 1999.23
                                                                                
                         1991.52  1994.9
       0   4.359   5.429   8.048  13.232  15.317  22.766  24.371  33.497  35.292
  41.953  44.228  53.409 153.918 185.159  219.78 236.456 259.838 311.217
 1992.95 1992.97    1993 1992.98 1993.09  1993.1 1993.34 1993.39 1993.42 1993.47
 1993.67 1993.72 1993.82  1995.3  1996.1  1996.8  1997.1  1997.7  1998.8
                                                                                
                  1991.6  1993.1
Pier Skew, UpSta & Num, DnSta & Num=  ,153.166, 2 ,81.568, 2 , 0 , 0 , 0 ,,
     2.2     2.2
    1992  1994.9
     2.2     2.2
    1992  1994.9
Pier Skew, UpSta & Num, DnSta & Num=  ,185.793, 2 ,114.195, 2 , 0 , 0 , 0 ,,
     2.2     2.2
    1992  1994.9
     2.2     2.2
    1992  1994.9
BR Coef=-1 , 0 , 0 ,, 0 ,,,0.8,-1,,0,
WSPro=,,,, 1 ,,,, 0 ,,,, 0 ,,,,-1 ,-1 ,-1 , 0 , 0 , 0 , 0 , 0
BC Design=,, 0 ,, 0 ,,,,,,

Type RM Length L Ch R = 1 ,3742    ,41.06,26.35,33.54
XS GIS Cut Line= 6
  951741.1249747  763278.5934324  951746.7999827  763315.1000565
  951774.5002067  763371.3995766  951780.6001747  763400.8999926
  951815.9998548  763473.4002167  951880.9941589  763589.5894009
#Sta/Elev= 30
       0 2014.63   2.628 2015.16   3.707 2014.97   14.61 2008.85  22.495 2006.35
  28.784 2002.97   33.47  2010.1    56.3  1988.5  71.879  1985.6  90.359    1980
  93.667  1977.4   98.55  1974.3 109.219  1976.4 110.778  1977.2 115.681  1979.7
 118.146  1977.4 140.469    1977 146.061  1977.7 155.867  1981.9 191.494  1982.6
 193.977 1983.61 196.687 1983.73 210.653 1985.34 214.695 1986.14 240.317 1993.09
 261.542 1994.42 283.004 1997.03 286.058 1998.25 294.052 1999.74 312.232 2000.11
#Mann= 3 ,-1 , 0
       0     .06       0  93.667    .056       0 110.778    .055       0
#XS Ineff= 2 , 0
       0   38.89  1993.9     168       0  1993.9
Permanent Ineff=
       F       F
Bank Sta=93.667,110.778
Skew Angle= 25
Exp/Cntr=0.5,0.3

Type RM Length L Ch R = 1 ,3716    ,377.28,360.59,347.99
XS GIS Cut Line= 6
  951689.0166866  763292.3273205  951711.4996306  763344.9005045
  951784.1002067  763463.9998967  951827.7000788  763515.3002488
  951832.7002708  763542.6000888  951864.0459349  763593.2430329
#Sta/Elev= 30
       0 2039.41     .44 2039.41   23.81 2028.74   31.58 2025.93      36 2024.69
   39.98 2020.59   45.17  2019.2   57.47  2011.3   80.81  1985.9   94.39  1979.9
   98.09    1977  109.55  1976.8   125.1    1977   130.1 1974.07   143.4  1975.9
  155.17  1979.1  197.87  1982.2  265.18  1989.9  284.22  1989.9  293.03  1986.1
   297.3 1987.67  300.72 1987.79   308.2 1989.08  314.72 1989.19   320.2 1989.77
  327.11 1991.73  333.87 1994.02  336.65 1994.58  349.25 2000.19  352.59 2000.34
#Mann= 3 ,-1 , 0
       0     .07       0   125.1     .04       0   143.4     .05       0
Bank Sta=125.1,143.4
Exp/Cntr=0.3,0.1

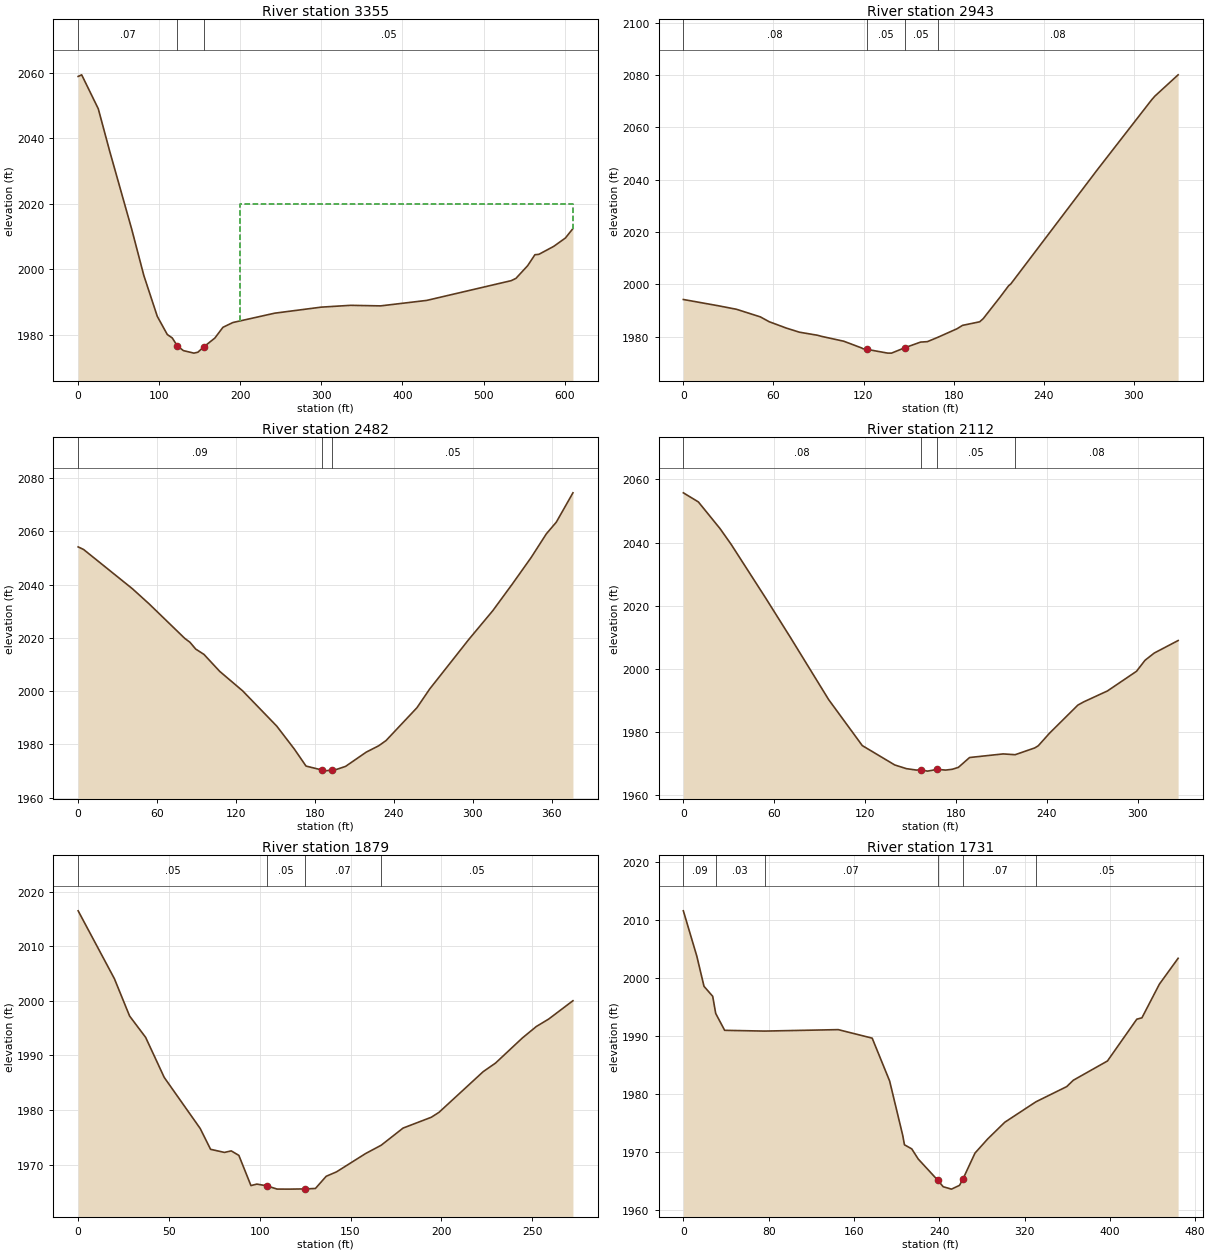
Type RM Length L Ch R = 1 ,3355    ,401.13,411.81,427.86
XS GIS Cut Line= 4
  951515.2787024   763678.259609  951620.0533585  763729.6193531
  951694.0127826  763772.7625211  952057.6433751  763957.6590334
#Sta/Elev= 30
       0 2058.82    4.35 2059.31   24.83 2048.96   38.84 2036.08   66.08 2012.24
   80.99 1998.16    97.6 1985.69  109.95 1980.15  116.06 1979.11  122.17 1976.73
  129.78 1975.25  142.76 1974.48  147.68 1974.76  154.96 1976.39  168.59 1979.07
  178.58 1982.35  190.87 1983.81  242.48 1986.66  299.94  1988.5  336.12 1989.05
  372.99 1988.88  429.93 1990.55  534.13 1996.57  539.93 1997.26  554.43 2001.14
  563.35 2004.48  568.19 2004.59  586.55 2007.02  600.92 2009.56  610.25 2012.45
#Mann= 3 , 0 , 0
       0     .07       0  122.17     .05       0  154.96     .05       0
#XS Ineff= 2 , 0
       0                     200       0    2020
Permanent Ineff=
       F       F
Bank Sta=122.17,154.96
Exp/Cntr=0.3,0.1

Type RM Length L Ch R = 1 ,2943    ,442.21,461.38,481.79
XS GIS Cut Line= 4
  951536.6301264  763971.6980734  951532.4460624  764081.5323136
  951532.4460624  764129.6500736  951618.2203985  764278.1884418
#Sta/Elev= 30
       0 1994.21   23.58 1991.78   35.38 1990.47    51.3 1987.56   57.19 1985.71
   68.56 1983.29    77.3 1981.71   89.45 1980.53   92.12 1980.11  106.86 1978.26
  118.83 1975.67  119.54 1975.41  122.07 1975.17  136.01 1973.72  138.65 1973.71
  147.33 1975.73  158.03 1977.93  162.56  1978.1  169.45 1979.74  182.23 1983.01
  185.96 1984.32  197.35 1985.68  199.71 1986.87  210.95  1995.1  216.62 1999.44
  218.16 2000.19  275.62  2043.7  311.73 2070.38  314.02  2071.9  329.56 2080.07
#Mann= 4 ,-1 , 0
       0     .08       0  122.07     .05       0  147.33     .05       0
  169.45     .08       0
Bank Sta=122.07,147.33
Exp/Cntr=0.3,0.1

Type RM Length L Ch R = 1 ,2482    ,355.34,369.95,381.45
XS GIS Cut Line= 5
  951491.6499023   763694.498201  951409.0131022   763707.050393
  951330.5593421   763711.234457   951284.533614  763723.7866491
  951157.9631179  763831.5288572
#Sta/Elev= 30
       0 2054.15    4.12 2053.19   41.27 2038.43   53.66 2032.89   81.07 2019.79
   84.94 2018.37   89.35  2015.8   95.64 2013.79  107.59 2007.43  125.01 2000.12
  150.96 1986.87  164.29 1978.28   173.2 1971.88  185.23 1970.41  186.28 1969.98
  192.89 1970.41  196.28  1970.6  203.25 1971.76     219 1977.12  228.34 1979.47
  233.99 1981.44  257.49 1993.77  267.18  2000.8  296.83 2019.36  315.16 2030.21
  330.07 2040.26  344.37 2050.22  355.83 2059.03  363.44 2063.45  376.07 2074.45
#Mann= 3 ,-1 , 0
       0     .09       0  185.23     .05       0  192.89     .05       0
Bank Sta=185.23,192.89
Exp/Cntr=0.3,0.1

Type RM Length L Ch R = 1 ,2112    ,233.9,233.73,231.88
XS GIS Cut Line= 4
  951542.9062224  763483.1978487  951427.8413902  763414.1587446
  951374.4930382  763391.1463926   951240.599918  763379.6397046
#Sta/Elev= 30
       0 2055.75    9.92 2052.87   24.33 2044.35   31.59 2039.41   54.22 2022.53
   70.76  2009.9   95.97 1990.24  118.14  1975.7  139.58 1969.56  147.29 1968.39
  153.99 1967.94  157.05 1968.02  161.19 1967.61  167.76 1968.17  173.16 1967.94
  177.54 1968.19  181.58  1968.8  188.99 1971.92  211.15 1973.06  219.05 1972.81
  232.01 1974.96  234.36 1975.65  241.77 1979.63  260.47 1988.52  264.41 1989.56
  279.99    1993  299.19 1999.23  304.86 2002.74  310.95 2005.02  326.67 2008.97
#Mann= 4 ,-1 , 0
       0     .08       0  157.05     .05       0  167.76     .05       0
  219.05     .08       0
Bank Sta=157.05,167.76
Exp/Cntr=0.3,0.1

Type RM Length L Ch R = 1 ,1879    ,149.79,149.59,149.21
XS GIS Cut Line= 2
  951623.2676945  763261.6359924  951385.9710542  763127.7418482
#Sta/Elev= 30
       0 2016.48   19.95 2004.06   28.33 1997.22   37.17 1993.31    47.4 1985.98
   67.21 1976.63   72.92 1972.82   80.56 1972.25    84.3 1972.53   88.49 1971.71
   95.15 1966.18    98.4 1966.45  103.81 1966.14  109.54 1965.54  116.17 1965.53
  125.01 1965.57  130.66 1965.65  136.59 1967.88  142.26 1968.69  158.27 1972.04
  166.89 1973.57  178.94 1976.71  194.48 1978.69  198.71 1979.59  223.09 1987.05
  229.85 1988.61  244.54 1993.18  252.25 1995.29  259.08 1996.66  272.46 2000.02
#Mann= 4 ,-1 , 0
       0     .05       0  103.81     .05       0  125.01     .07       0
  166.89     .05       0
Bank Sta=103.81,125.01
Exp/Cntr=0.3,0.1

Type RM Length L Ch R = 1 ,1731    ,104.54,108.3,114.65
XS GIS Cut Line= 4
  951811.2362068  763211.9791603  951640.8723025  763102.8013042
  951557.1889744  763051.5449841  951395.0529102  763029.5781361
#Sta/Elev= 30
       0 2011.63   12.64 2003.81   19.39  1998.6   27.54 1996.88   30.36 1993.92
   38.75 1991.01   76.13 1990.88  145.27 1991.13  177.13 1989.66  193.49 1982.27
  205.78 1972.88   207.4 1971.26  214.25 1970.55  220.38 1968.79  238.53 1965.17
  243.76 1964.02  251.49 1963.61  259.03 1964.26  262.28 1965.36  273.56 1969.83
  285.53 1972.28  301.57 1975.16  330.73 1978.68  359.59  1981.3   365.8  1982.4
  397.79 1985.72  425.32 1992.93  430.14 1993.17  446.52 1998.98  464.09 2003.44
#Mann= 6 ,-1 , 0
       0     .09       0   30.36     .03       0   76.13     .07       0
  238.53     .05       0  262.28     .07       0  330.73     .05       0
Bank Sta=238.53,262.28
Exp/Cntr=0.3,0.1

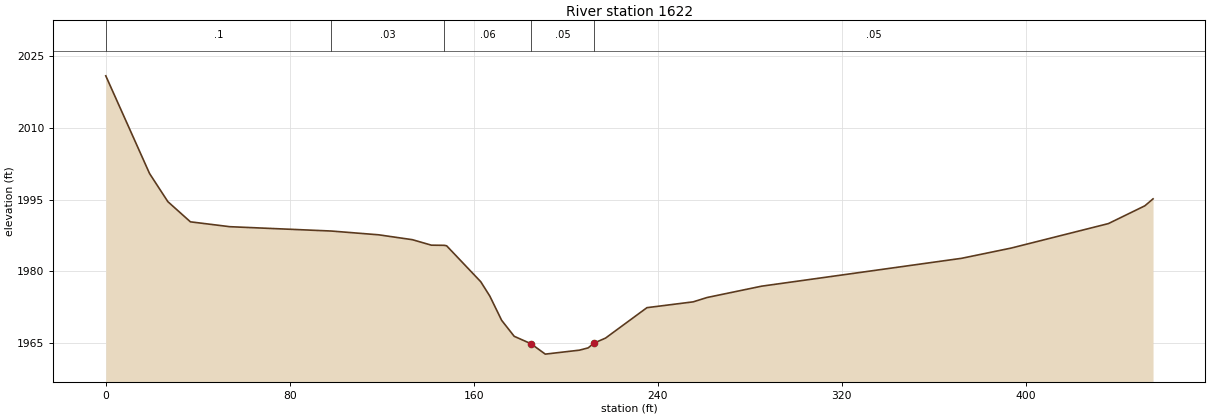
Type RM Length L Ch R = 1 ,1622    ,384.75,373.95,363.8
XS GIS Cut Line= 4
  951828.6155348  763044.8726001  951676.2146386   762976.693656
  951589.3190225   762984.714648  951402.1594702  762911.1873519
#Sta/Elev= 30
       0 2020.91   19.03 2000.45      27 1994.55   36.79 1990.33   53.93 1989.31
   98.11  1988.4  118.65 1987.61   133.3 1986.59  141.56 1985.44  147.14 1985.41
  148.19 1985.31  163.03 1977.78  166.96 1974.78  172.11  1969.7  177.57 1966.35
  184.85  1964.8  191.08 1962.62  205.93 1963.45  209.73 1963.93  212.14  1964.9
  217.28 1965.98  235.27 1972.35  255.39 1973.57  261.44 1974.48  285.11 1976.85
  372.09 1982.69   393.6 1984.83  435.89 1989.96  451.73 1993.68  455.31 1995.14
#Mann= 5 ,-1 , 0
       0      .1       0   98.11     .03       0  147.14     .06       0
  184.85     .05       0  212.14     .05       0
Bank Sta=184.85,212.14
Exp/Cntr=0.3,0.1