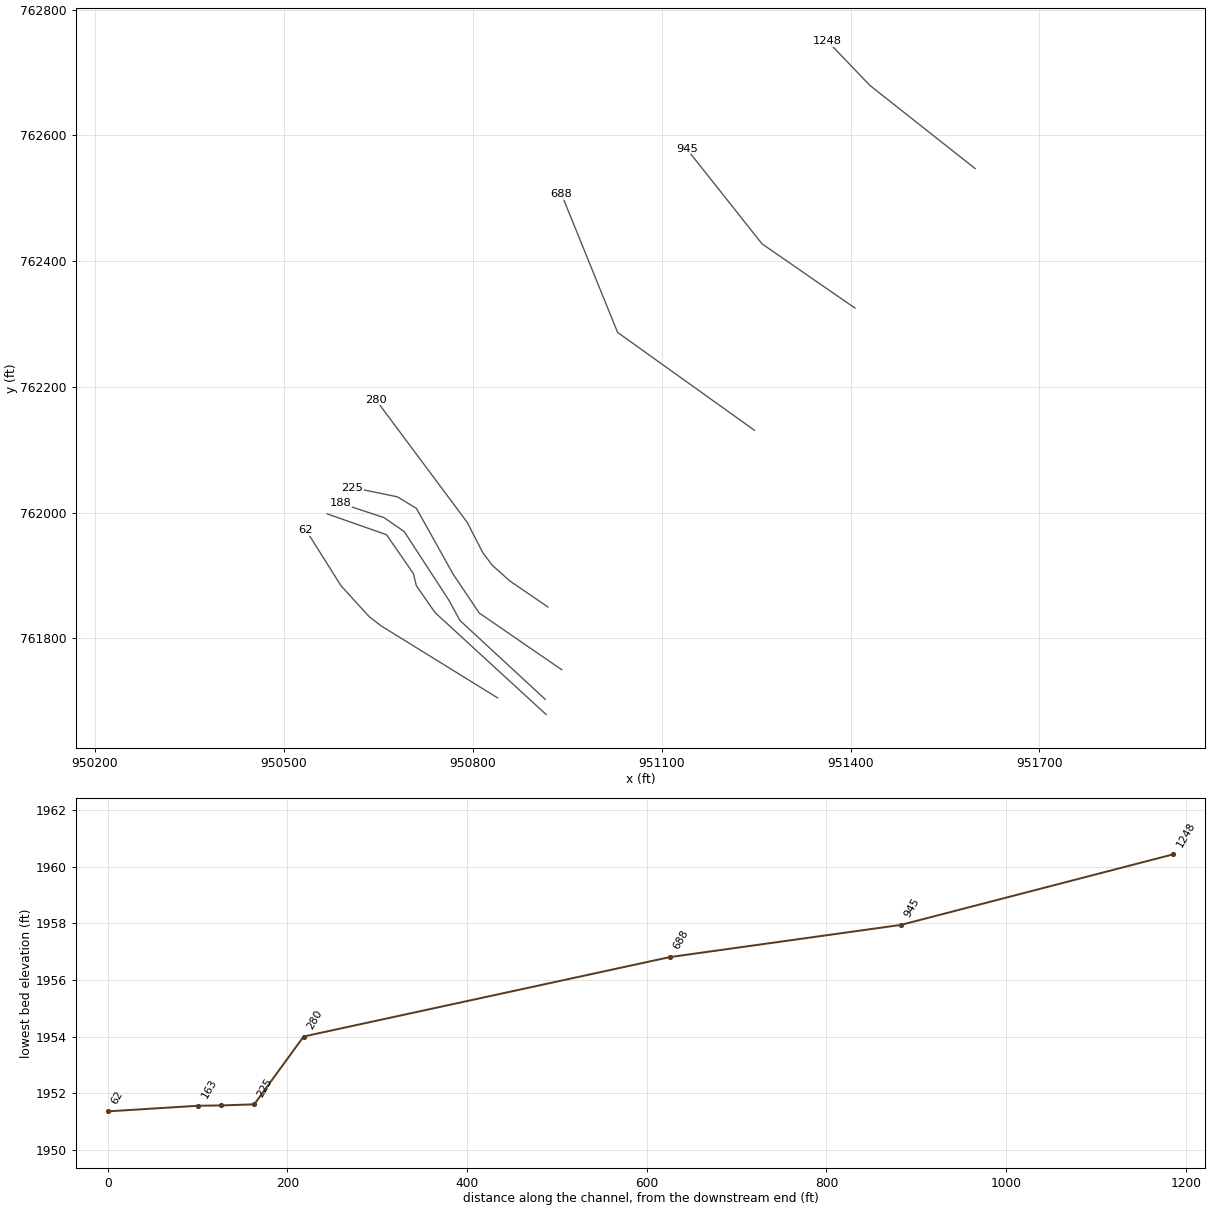
HEC-RAS study dtl_little_ivy_crk.prj: dtl_Little_Ivy_Crk

--- dtl_little_ivy_crk.g01 (geometry) --- (continued)

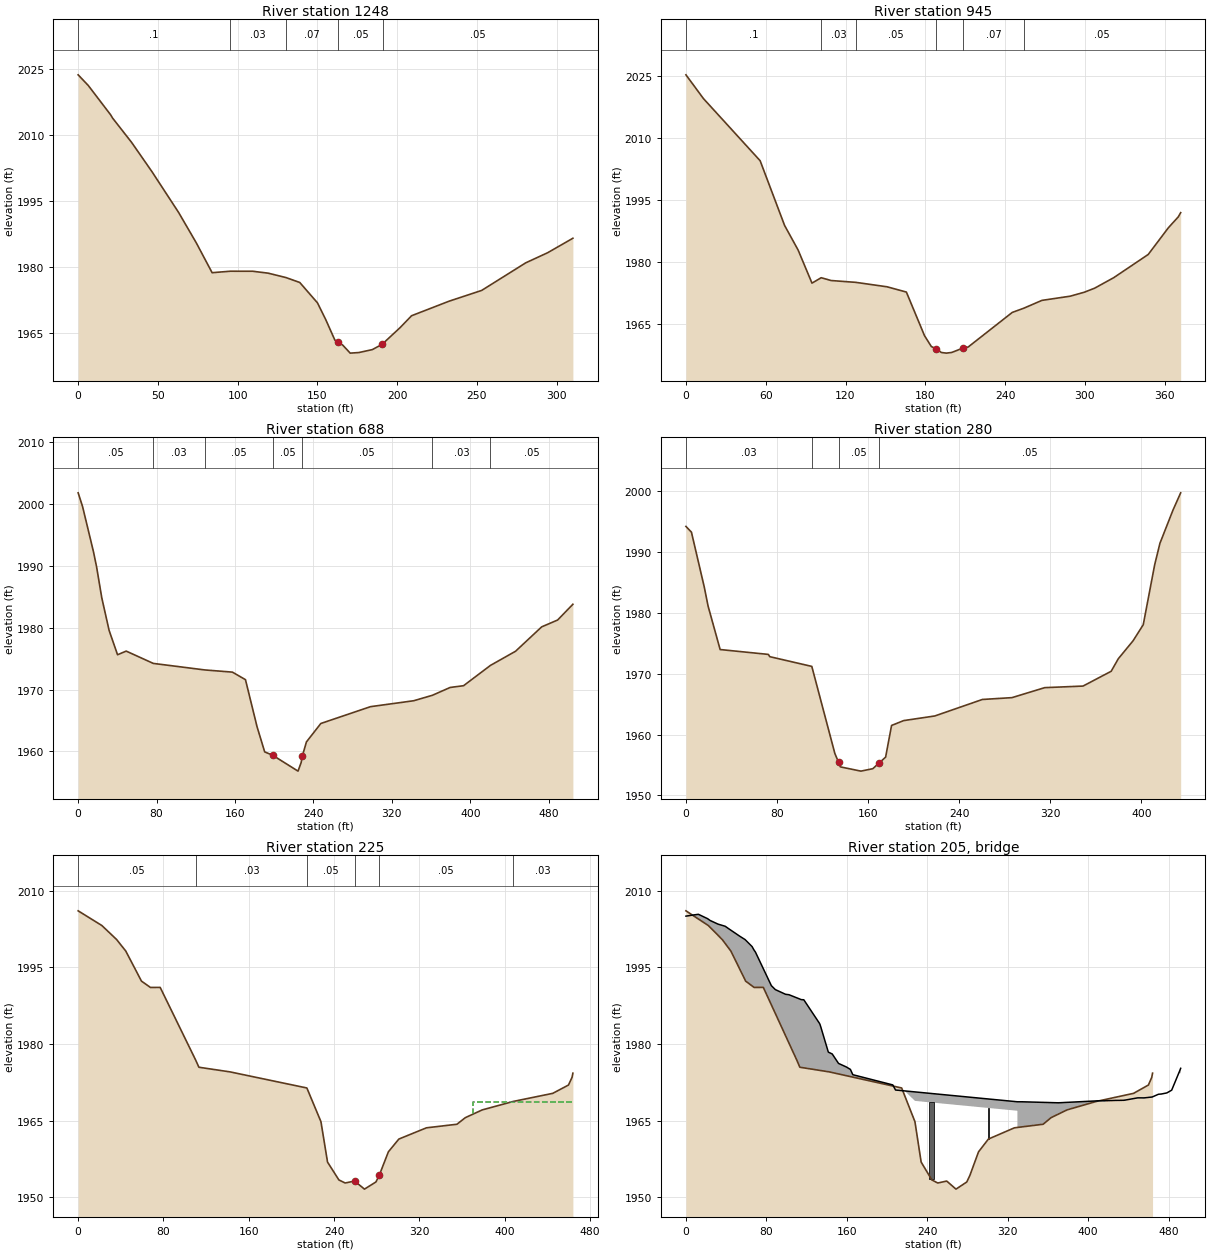
Type RM Length L Ch R = 1 ,1248    ,305.9,303.32,299.51
XS GIS Cut Line= 3
  951597.8479185  762547.2208874  951430.7628622  762679.4110956
  951363.7277262  762749.6052717
#Sta/Elev= 30
       0 2023.78    6.35 2021.35   20.42 2014.65   21.56 2013.95   33.58 2008.37
   46.31 2001.72   62.98 1992.46   74.09 1985.52   83.98 1978.75   95.36 1979.09
  109.42 1979.08  119.06 1978.65  130.32 1977.64   138.9 1976.53  150.02 1971.89
  155.27 1968.02  160.92 1963.42  162.91 1962.96  165.87 1962.27  170.52 1960.45
  175.93 1960.58   184.4 1961.25  190.49 1962.44  201.83 1966.26     209 1968.96
   232.6 1972.28  252.95 1974.72  280.58    1981  294.32  1983.3  310.12 1986.59
#Mann= 5 ,-1 , 0
       0      .1       0   95.36     .03       0  130.32     .07       0
  162.91     .05       0  191.16     .05       0
Bank Sta=162.91,190.49
Exp/Cntr=0.3,0.1

Type RM Length L Ch R = 1 ,945     ,252.78,257.36,261.99
XS GIS Cut Line= 3
  951407.0367822  762325.3743591   951259.496814  762427.4640872
  951139.9263818  762578.4999915
#Sta/Elev= 30
       0 2025.27   13.15 2019.53    55.8 2004.49   74.19 1988.84   84.39 1982.87
   94.79 1974.88  101.72 1976.19  109.19 1975.51  127.68 1975.07  151.19    1974
  165.78 1972.72  179.42 1962.17  184.56 1959.54  188.23    1959  192.04 1958.11
  195.73 1957.95  199.87 1958.11  208.38 1959.18  212.22 1959.42  245.41  1967.8
  253.97  1968.8  267.73 1970.71  288.92 1971.72  299.56 1972.68  307.36 1973.66
   321.7  1976.2  347.64 1981.81   362.8 1988.27  370.25 1990.91  372.06 1991.93
#Mann= 6 ,-1 , 0
       0      .1       0  101.72     .03       0  127.68     .05       0
  188.01     .05       0  208.44     .07       0  253.97     .05       0
Bank Sta=188.23,208.38
Exp/Cntr=0.3,0.1

Type RM Length L Ch R = 1 ,688     ,414.65,407.45,396.92
XS GIS Cut Line= 3
   951247.382894  762131.0846948  951030.1402697   762286.665111
  950940.9662536  762506.7534314
#Sta/Elev= 30
       0 2001.84    4.49 1999.63   15.67 1992.28   18.82 1989.85   24.11 1984.85
   31.58 1979.58    40.2 1975.64   49.02 1976.23   76.63 1974.24  129.31 1973.18
  157.33 1972.83  170.68 1971.61   182.5 1963.99  190.29 1959.92  198.32 1959.39
  224.29 1956.81  227.46 1958.19  228.58  1959.2  232.88 1961.54  247.57 1964.52
  298.23 1967.24  342.33  1968.2  361.34 1969.08  379.49 1970.35  393.14 1970.63
  420.52 1973.91  446.21 1976.21  472.82 1980.15   489.1 1981.26  504.67 1983.81
#Mann= 7 ,-1 , 0
       0     .05       0   76.63     .03       0  129.31     .05       0
  198.32     .05       0  228.58     .05       0  361.34     .03       0
  420.52     .05       0
Bank Sta=198.32,228.58
Exp/Cntr=0.3,0.1

Type RM Length L Ch R = 1 ,280     ,58.33,54.99,58.42
XS GIS Cut Line= 6
  950919.5308615  761849.9803104  950858.8004935  761891.5997665
  950831.2999494  761916.2996705  950816.3003974  761936.0004066
  950791.3004614  761984.6997986  950646.0245572  762179.9479269
#Sta/Elev= 30
       0 1994.19    4.83 1993.25   16.07 1984.26   19.44 1981.12   30.05 1973.97
   72.43 1973.17   73.63  1972.8  110.57  1971.2  130.82  1956.9  134.06 1955.46
   135.6  1954.7  153.73    1954  164.16  1954.4  169.42 1955.29  175.41  1956.3
  180.63  1961.5  191.28  1962.3  218.62 1963.06  260.43 1965.77  286.41 1966.07
  315.15 1967.71   348.8 1967.97  373.56  1970.4  379.82 1972.46  392.84 1975.42
  401.74 1978.05  411.74 1987.87  416.37 1991.41  427.91  1996.9  434.61 1999.71
#Mann= 4 ,-1 , 0
       0     .03       0  110.57     .05       0  134.06     .05       0
  169.42     .05       0
Bank Sta=134.06,169.42
Exp/Cntr=0.5,0.3

Type RM Length L Ch R = 1 ,225     ,35.84,37.47,33.55
XS GIS Cut Line= 6
  950941.5284296  761750.2570463  950810.5004614  761840.3997664
  950768.8001093  761902.5002465  950710.7003972  762006.9001187
  950680.4883012  762025.2297187  950608.5973323  762040.0529616
#Sta/Elev= 30
       0 2006.08   22.26  2003.2   36.08 2000.46   44.68  1998.2   59.38 1992.32
   67.81 1991.08   76.94 1991.09  110.29 1976.83  113.25 1975.46  142.49 1974.55
  214.52  1971.4  227.72  1964.8  233.88  1956.9  244.53  1953.4  250.42  1952.8
   259.3 1953.18  268.53  1951.6  279.27    1953  282.38  1954.3  290.95  1958.9
  300.77  1961.4  326.62  1963.6  355.24  1964.3  363.11 1965.59     379 1967.11
  408.18 1968.77  445.14 1970.35  459.88 1971.98  463.22 1973.49     464  1974.3
#Mann= 6 ,-1 , 0
       0     .05       0  110.29     .03       0  214.52     .05       0
   259.3     .05       0  282.38     .05       0  408.18     .03       0
#XS Ineff= 2 , 0
       0     198  1970.8     370       0  1968.7
Permanent Ineff=
       F       F
Bank Sta=259.3,282.38
Exp/Cntr=0.5,0.3

Type RM Length L Ch R = 3 ,205     ,,,
Bridge Culvert--1,0,-1,-1, 0
Deck Dist Width WeirC Skew NumUp NumDn MinLoCord MaxHiCord MaxSubmerge Is_Ogee
7.2,19.5,2.6,0, 58, 64, , , 0.95, 0, 0,0,,
       0    7.57   12.39   21.57   23.95   28.58   31.86   39.03   42.36   53.51
   58.82   65.78   67.61   69.09   84.95   88.88   99.09  102.41  111.62  114.63
   117.2   132.7  133.21   134.2  141.59  145.45  151.72  159.32  163.53  165.95
   205.7   208.4   329.6   334.2   370.3   411.3  416.26  416.95  417.22  424.81
  428.16  428.28  432.31  435.33  436.52  446.97  449.07  449.27  449.84  455.44
  457.39  463.55  469.84  472.75  478.15  483.01  490.57  491.96
 2005.04 2005.27  2005.4 2004.54  2004.2 2003.78 2003.48 2003.06  2002.6 2001.11
 2000.45 1999.08 1998.43 1998.01 1991.43 1990.66 1989.74 1989.66 1988.94  1988.7
 1988.67 1984.08 1983.89 1983.29 1978.42 1978.06 1976.21 1975.53 1975.04    1974
    1972    1971  1968.7  1968.7  1968.5  1968.9 1968.89 1968.91 1968.91 1968.95
 1968.97 1968.97 1968.98 1968.99 1969.02 1969.39 1969.46 1969.47 1969.47 1969.46
  1969.5 1969.63 1970.17 1970.22 1970.43 1970.97 1974.56 1975.25
                                                                                
                                                                                
                                                                                
         1969.24 1966.94
                                                                                
                                                                
       0    7.57   12.39   21.57   23.95   28.58   31.86   39.03   42.36   53.51
   58.82   65.78   67.61   69.09   84.95   88.88   99.09  102.41  111.62  114.63
   117.2   132.7  133.21   134.2  141.59  145.45  151.72  159.32  163.53  166.91
  172.09  179.21  179.35  179.47   185.9   222.9   229.4   350.6   351.6   377.7
  406.03  409.13  416.26  416.95  417.22  424.81  428.16  428.28  432.31  435.33
  436.52  446.97  449.07  449.27  449.84  455.44  457.39  463.55  469.84  472.75
  478.15  483.01  490.57  491.96
 2005.04 2005.27  2005.4 2004.54  2004.2 2003.78 2003.48 2003.06  2002.6 2001.11
 2000.45 1999.08 1998.43 1998.01 1991.43 1990.66 1989.74 1989.66 1988.94  1988.7
 1988.67 1984.08 1983.89 1983.29 1978.42 1978.06 1976.21 1975.53 1975.04 1974.98
 1974.93 1974.86 1974.86 1974.86    1974    1972    1971  1968.7  1968.7  1968.5
  1968.9 1968.67 1968.89 1968.91 1968.91 1968.95 1968.97 1968.97 1968.98 1968.99
 1969.02 1969.39 1969.46 1969.47 1969.47 1969.46  1969.5 1969.63 1970.17 1970.22
 1970.43 1970.97 1974.56 1975.25
                                                                                
                                                                                
                                                                                
                                                 1969.24 1966.94
                                                                                
                                                                                
                                
Pier Skew, UpSta & Num, DnSta & Num=  ,244, 6 ,266, 6 , 0 , 0 , 0 ,,
     5.4     5.4     3.9     3.9       1       1
    1956  1957.3  1957.3  1959.3  1959.3    1970
     5.4     5.4     3.9     3.9       1       1
    1956  1957.3  1957.3  1959.3  1959.3    1970
Pier Skew, UpSta & Num, DnSta & Num=  ,300.5, 2 ,318, 2 , 0 , 0 , 0 ,,
       1       1
    1966 1969.24
       1       1
    1966 1969.24
BR Coef=-1 , 0 , 0 ,, 0 ,,,0.8,0,,0,
WSPro=,,,, 1 ,,,, 0 ,,,, 0 ,,,,-1 ,-1 ,-1 , 0 , 0 , 0 , 0 , 0
BC Design=,, 0 ,, 0 ,,,,,,

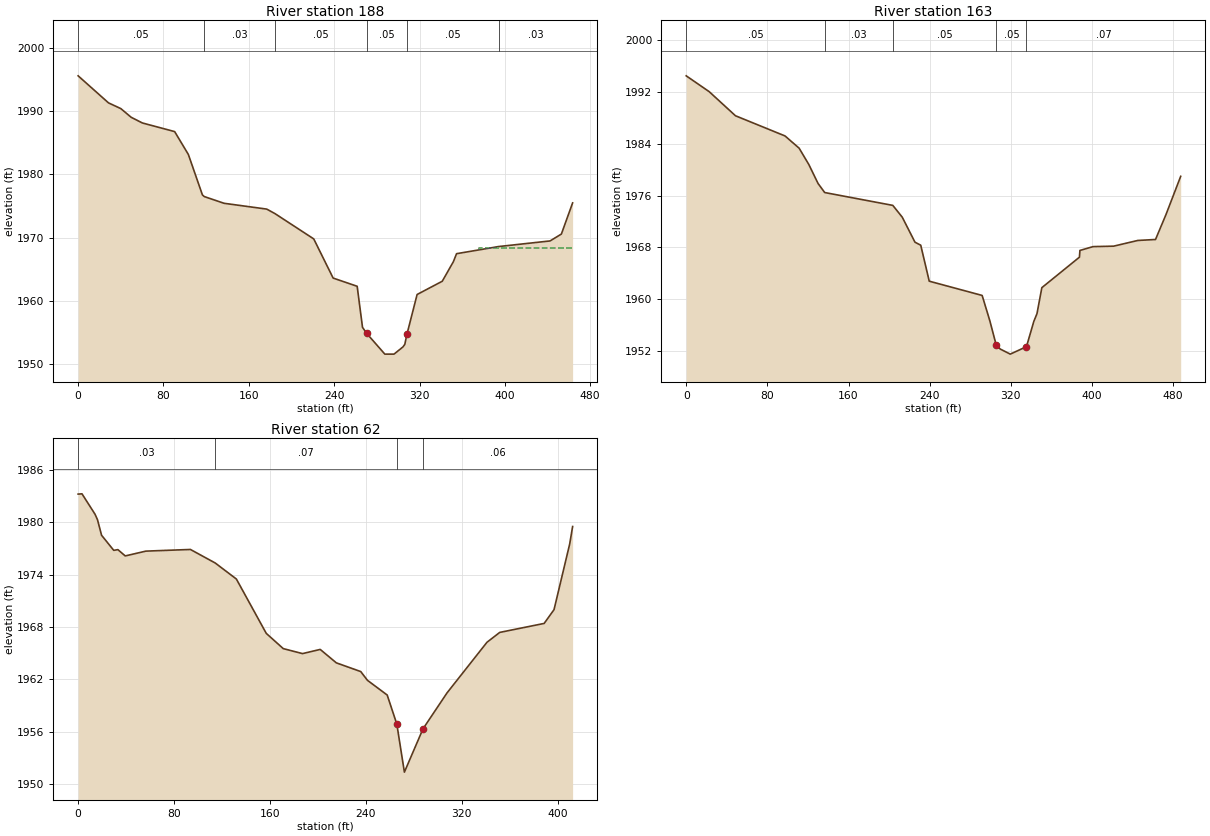
Type RM Length L Ch R = 1 ,188     ,27.47,25.17,26.13
XS GIS Cut Line= 6
  950915.1317575  761703.3281502  950779.6995653  761828.6995424
  950762.4001093  761860.6002145  950691.4000452  761969.8999266
  950659.2228932  761992.2333666  950590.2964291  762014.9641187
#Sta/Elev= 30
       0 1995.62   28.45 1991.34   40.02 1990.43   49.68 1989.06   60.16 1988.16
   90.47 1986.79  103.32 1983.17  116.51 1976.76   118.3  1976.5  136.79 1975.44
  176.77 1974.52  184.56  1973.8  220.85  1969.8  239.02  1963.6  261.55  1962.3
  266.55  1955.8  270.51 1954.83  287.47 1951.56  296.07 1951.56  304.46  1952.7
  306.18  1953.1   308.2 1954.71  317.72    1961  341.31  1963.1  351.74  1966.2
  354.69 1967.46  394.03 1968.59  442.36 1969.48  452.95 1970.57  463.48  1975.5
#Mann= 6 ,-1 , 0
       0     .05       0   118.3     .03       0  184.56     .05       0
  270.51     .05       0   308.2     .05       0  394.03     .03       0
#XS Ineff= 2 , 0
       0     214  1968.4     376       0  1968.4
Permanent Ineff=
       F       F
Bank Sta=270.51,308.2
Exp/Cntr=0.5,0.3

Type RM Length L Ch R = 1 ,163     ,94.21,100.52,103.68
XS GIS Cut Line= 6
  950916.5981255  761679.1310302  950740.1997893  761841.1995104
  950710.4996932  761884.0999905  950706.0002372  761902.9999585
  950663.2001092  761965.0000866   950569.032045  761998.0998626
#Sta/Elev= 30
       0 1994.47   22.63 1992.03   48.56 1988.31   97.38  1985.2  111.31 1983.31
  120.94 1980.77  129.94 1977.87  136.51 1976.47  203.62 1974.49  212.95 1972.67
   225.5 1968.81  231.17 1968.35  239.56  1962.8  291.71  1960.6  299.26  1956.7
  305.65  1952.9  309.59 1952.33  319.43 1951.55  335.38  1952.7  342.64  1956.6
  345.76  1957.8  350.54  1961.8  387.58  1966.5  388.08 1967.54  401.02 1968.13
  421.28  1968.2  445.12 1969.08  462.59 1969.23  472.87 1973.06   487.4 1978.97
#Mann= 5 ,-1 , 0
       0     .05       0  136.51     .03       0  203.62     .05       0
  305.65     .05       0  335.38     .07       0
Bank Sta=305.65,335.38
Exp/Cntr=0.3,0.1

Type RM Length L Ch R = 1 ,62      ,56.08,62.09,53.26
XS GIS Cut Line= 5
  950839.6056134  761705.5287262  950654.8237892  761819.9166944
  950635.7589571  761834.5824224  950591.0296131  761883.7108705
   950535.302509  761972.4353506
#Sta/Elev= 30
       0 1983.23    3.22 1983.26    14.1 1980.92   16.13  1980.3   19.55 1978.51
   29.71 1976.78   33.17 1976.86    39.3 1976.14   56.53 1976.69   93.71 1976.88
  114.37 1975.33  132.04 1973.49  156.97 1967.26  171.17 1965.51  187.23 1964.94
  201.98 1965.42  215.44 1963.88  235.81 1962.88  241.38 1961.88  257.88 1960.19
  265.91 1956.86  272.23 1951.35  287.74 1956.31  307.83 1960.44  341.14 1966.24
  351.79 1967.37  388.84  1968.4  397.09 1969.98  410.17 1977.52  412.59 1979.51
#Mann= 4 ,-1 , 0
       0     .03       0  114.37     .07       0  265.91     .05       0
  287.74     .06       0
Bank Sta=265.91,287.74
Exp/Cntr=0.3,0.1

Chan Stop Cuts=-1
Use User Specified Reach Order=0
User Specified Reach Order=Little_Ivy_crk  ,reach one