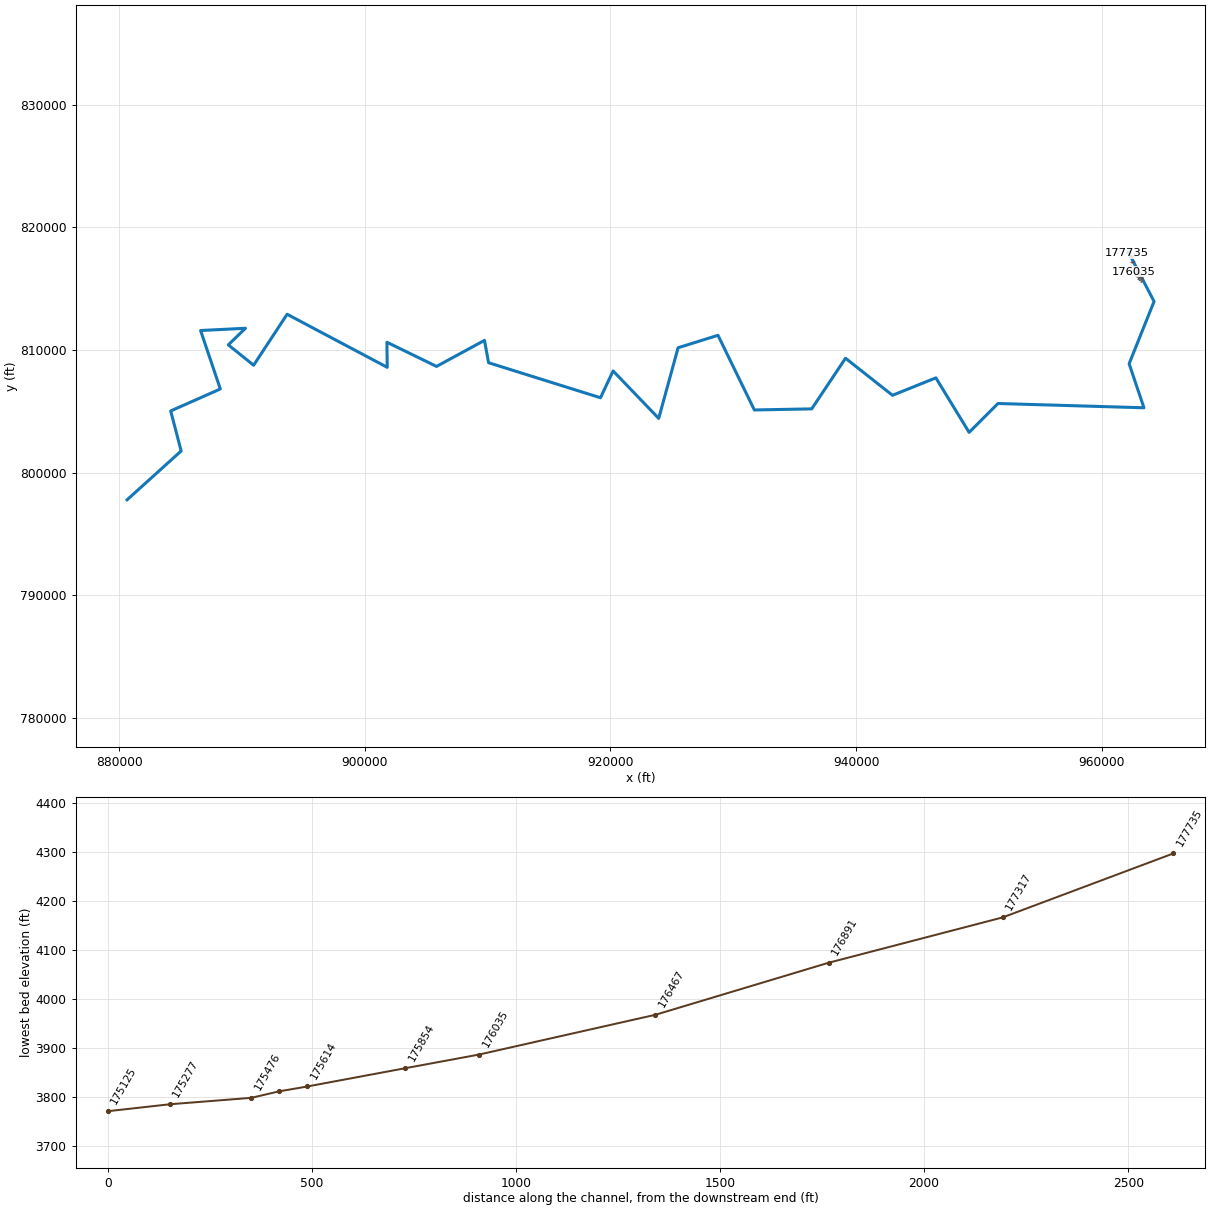
--- lds_big_laurel_crk.prj (project) ---

Proj Title=lds_big_laurel_crk
Current Plan=p24
Default Exp/Contr=0.3,0.1
English Units
Geom File=g20
Flow File=f01
Plan File=p24
Y Axis Title=Elevation
X Axis Title(PF)=Main Channel Distance
X Axis Title(XS)=Station
BEGIN DESCRIPTION:
NCFPMP - Big Laurel Basin - Big Laurel Creek LDS
END DESCRIPTION:
DSS Export Rating Curves= 0
DSS Export Rating Curve Sorted= 0
DSS Export Volume Flow Curves= 0
DXF OffsetX= 0
DXF OffsetY= 0
DXF ScaleX= 1
DXF ScaleY= 10

--- lds_big_laurel_crk.p24 (plan) ---

Plan Title=lds_big_laurel_crk
Program Version=3.13
Short Identifier=lds_big_laur
Geom File=g20
Flow File=f01
Subcritical Flow
K Sum by GR= 0
Std Step Tol= 0.01
Critical Tol= 0.01
Num of Std Step Trials= 20
Max Error Tol= 0.3
Flow Tol Ratio= 0.001
Split Flow NTrial= 30
Split Flow Tol= 0.02
Split Flow Ratio= 0.02
Log Output Level= 0
Friction Slope Method= 0
Unsteady Friction Slope Method= 2
Unsteady Bridges Friction Slope Method= 1
Parabolic Critical Depth
Global Vel Dist= 0 , 0 , 0
Global Log Level= 0
CheckData=True
Encroach Param=-1 ,10,10, 2
Encroach River=Big_Laurel_Creek
Encroach Reach=Main_Branch
Encroach Node=177735
       1     165     219
Encroach Node=177317
       1     129     176
Encroach Node=176891
       1     118     164
Encroach Node=176467
       1     150     192
Encroach Node=176035
       4      .7
Encroach Node=175854
       4      .7
Encroach Node=175614
       1     213     284
Encroach Node=175543
       1     139   212.3
Encroach Node=175476
       1      63   125.8
Encroach Node=175277
       1     140     330
Encroach Node=175125
       4      .7
Encroach Node=174774
       4      .7
Encroach Node=174338
       4      .7
Encroach Node=173917
       1     139  203.31
Encroach Node=173486
       1     158     204
Encroach Node=173075
       1     148     192
Encroach Node=172912
       1     195     292
Encroach Node=172774
       4      .7
Encroach Node=172717
       1     210     285
Encroach Node=172590
       1     153     216
Encroach Node=172390
       4      .7
Encroach Node=172185
       1     433     500
Encroach Node=171942
       4      .7
Encroach Node=171804
       1     239   298.3
Encroach Node=171406
       1     165  232.19
Encroach Node=171176
       1     250     328
Encroach Node=170964
       4      .7
Encroach Node=170542
       4      .7
Encroach Node=170272
       1     122  207.62
Encroach Node=170059
       1     138   204.5
Encroach Node=169919
       1     132     208
Encroach Node=169690
       1     180     258
Encroach Node=169421
       1     250   327.5
Encroach Node=169134
       1     273     329
Encroach Node=168912
       1     124     220
Encroach Node=168858
       1   129.5     214
Encroach Node=168691
       1     130     185
Encroach Node=168646
       4      .7
Encroach Node=168391
       1     131     177
Encroach Node=167976
       4      .7
Encroach Node=167877
       1     155     220
Encroach Node=167837
       1     161     215
Encroach Node=167546
       4      .7
Encroach Node=167461
       4      .7
Encroach Node=167427
       1      70  149.74
Encroach Node=167319
       1     100     160
Encroach Node=167152
       1     171     223
Encroach Node=166974
       1     200     265
Encroach Node=166832
       1     169   218.5
Encroach Node=166791
       1     160     204
Encroach Node=166676
       1     163     205
Encroach Node=166364
       1     236     290
Encroach Node=166167
       4      .7
Encroach Node=166026
       1     187     272
Encroach Node=165881
       4      .7
Encroach Node=165716
       4      .7
Encroach Node=165638
       4      .7
Encroach Node=165588
       1      75     160
Encroach Node=165458
       1      85     170
Encroach Node=165173
       4      .7
Encroach Node=165108
       4      .7
Encroach Node=164845
       1     160  221.47
Encroach Node=164624
       1     143  210.54
Encroach Node=164194
       1   198.6   252.2
Encroach Node=163732
       1     166     205
Encroach Node=163530
       1     121     171
Encroach Node=163288
       1     160     237
Encroach Node=163104
       1     245     296
Encroach Node=162884
       4      .7
Encroach Node=162725
       4      .7
Encroach Node=162683
       1     125     235
Encroach Node=162457
       4      .7
Encroach Node=162047
       1   188.8     275
Encroach Node=161620
       4      .7
Encroach Node=161395
       4      .7
Encroach Node=161104
       4      .7
Encroach Node=160720
       4      .7
Encroach Node=160443
       1     170     330
Encroach Node=160400
       1     180     330
Encroach Node=160226
       1     208     290
Encroach Node=160173
       1     235     315
Encroach Node=159883
       4      .7
Encroach Node=159598
       1     138     265
Encroach Node=159275
       1     174   221.5
Encroach Node=159048
       1     123     270
Encroach Node=158879
       1     155     273
Encroach Node=158620
       1     191     268
Encroach Node=158176
       4      .7
Encroach Node=157992
       1     230     387
Encroach Node=157938
       1     200   375.7
Encroach Node=157774
       1     275     339
Encroach Node=157509
       1     150     275
Encroach Node=157356
       1     110   229.5
Encroach Node=157304
       1     133     218
Encroach Node=157092
       1     182     238
Encroach Node=156870
       4      .7
Encroach Node=156811
       1     140     255
Encroach Node=156676
       4      .7
Encroach Node=156578
       4      .7
Encroach Node=156513
       1    57.4     230
Encroach Node=156351
       1      64     190
Encroach Node=156064
       1      95     160
Encroach Node=155652
       1   45.75     170
Encroach Node=155224
       1      69     181
Encroach Node=154978
       1     160     260
Encroach Node=154811
       4      .7
Encroach Node=154770
       1     220     325
Encroach Node=154506
       4      .7
Encroach Node=154208
       1     190     270
Encroach Node=154160
       1     158     302
Encroach Node=154043
       1     122     171
Encroach Node=153680
       1      37      84
Encroach Node=153504
       1      98     143
Encroach Node=153367
       1     113     178
Encroach Node=153309
       1   96.71  164.36
Encroach Node=153130
       1     110     200
Encroach Node=152973
       1    66.3     210
Encroach Node=152683
       1      77   219.5
Encroach Node=152269
       4      .7
Encroach Node=152098
       4      .7
Encroach Node=152064
       4      .7
Encroach Node=151789
       4      .7
Encroach Node=151571
       1   102.3     147
Encroach Node=151420
       1      71     126
Encroach Node=151371
       1    84.5  130.75
Encroach Node=150966
       4      .7
Encroach Node=150830
       4      .7
Encroach Node=150704
       1      83     150
Encroach Node=150545
       4      .7
Encroach Node=150112
       1      70     124
Encroach Node=149689
       1      81     133
Encroach Node=149265
       4      .7
Encroach Node=149070
       4      .7
Encroach Node=148842
       1    92.5     214
Encroach Node=148484
       1   79.68     181
Encroach Node=148341
       1   64.55     340
Encroach Node=148249
       1    60.7     245
Encroach Node=148001
       1   59.75     136
Encroach Node=147585
       1   48.47     230
Encroach Node=147416
       1  106.81     576
Encroach Node=147269
       1  188.39     800
Encroach Node=147158
       1     204     653
Encroach Node=146994
       1   146.7     256
Encroach Node=146623
       4      .7
Encroach Node=146167
       1      56     290
Encroach Node=145962
       1  153.76     216
Encroach Node=145898
       1  134.69   201.5
Encroach Node=145814
       1      71     135
Encroach Node=145728
       4      .7
Encroach Node=145346
       1    84.5     154
Encroach Node=145019
       1   87.99     183
Encroach Node=144585
       1   87.46     250
Encroach Node=144171
       1      69     230
Encroach Node=143731
       1   62.27     248
Encroach Node=143536
       4      .7
Encroach Node=143315
       4      .7
Encroach Node=142983
       4      .7
Encroach Node=142748
       4      .7
Encroach Node=142558
       1      80     210
Encroach Node=142456
       1     109     210
Encroach Node=142138
       4      .7
Encroach Node=141908
       1      90     210
Encroach Node=141553
       1     100  191.82
Encroach Node=141412
       1    77.1     170
Encroach Node=141172
       1      78     160
Encroach Node=140786
       1    62.2   113.4
Encroach Node=140516
       1      87     130
Encroach Node=140464
       1      99     188
Encroach Node=140274
       1     130     247
Encroach Node=139928
       4      .7
Encroach Node=139706
       1      82     155
Encroach Node=139651
       1    80.5     145
Encroach Node=139401
       1      48     102
Encroach Node=139040
       4      .7
Encroach Node=138839
       1     112     172
Encroach Node=138599
       1     156  215.01
Encroach Node=138295
       1     150     261
Encroach Node=138159
       1     119     220
Encroach Node=137931
       1      95     210
Encroach Node=137862
       1      90     188
Encroach Node=137810
       4      .7
Encroach Node=137567
       4      .7
Encroach Node=137396
       4      .7
Encroach Node=137009
       4      .7
Encroach Node=136526
       4      .7
Encroach Node=136107
       4      .7
Encroach Node=135689
       4      .7
Encroach Node=135284
       4      .7
Encroach Node=135042
       1     350   537.5
Encroach Node=134986
       1     393   511.1
Encroach Node=134800
       1     382     570
Encroach Node=134491
       4      .7
Encroach Node=134347
       4      .7
Encroach Node=133983
       4      .7
Encroach Node=133730
       1     127     376
Encroach Node=133555
       1      78     240
Encroach Node=133506
       4      .7
Encroach Node=133355
       1     163     290
Encroach Node=133311
       1     167     256
Encroach Node=133238
       4      .7
Encroach Node=133080
       1     125   243.7
Encroach Node=132808
       1     140  219.21
Encroach Node=132274
       1      68   121.5
Encroach Node=132019
       1   130.5     194
Encroach Node=131784
       4      .7
Encroach Node=131420
       4      .7
Encroach Node=131131
       4      .7
Encroach Node=131085
       1      90     153
Encroach Node=130974
       1      84     125
Encroach Node=130568
       1  135.32     186
Encroach Node=130155
       1     117     158
Encroach Node=129754
       1      97     152
Encroach Node=129433
       1   77.88  187.88
Encroach Node=129359
       1  110.55  230.55
Encroach Node=129265
       1     154     255
Encroach Node=128935
       1     238     310
Encroach Node=128658
       1     129     210
Encroach Node=128597
       1      85     161
Encroach Node=128388
       1     120     200
Encroach Node=128021
       1     140  188.05
Encroach Node=127826
       1     130     210
Encroach Node=127762
       1     120     235
Encroach Node=127539
       1     200     290
Encroach Node=127289
       1     142     219
Encroach Node=127082
       4      .7
Encroach Node=127030
       1     100     205
Encroach Node=126851
       1     240     340
Encroach Node=126624
       1     105     265
Encroach Node=126518
       1     100     225
Encroach Node=126264
       1      85     200
Encroach Node=125890
       1      86     294
Encroach Node=125611
       4      .7
Encroach Node=125418
       1   65.28     522
Encroach Node=125229
       1      76     350
Encroach Node=124987
       1      48     220
Encroach Node=124734
       1      68     140
Encroach Node=124532
       1     120     210
Encroach Node=124293
       4      .7
Encroach Node=124079
       1     130     219
Encroach Node=123798
       4      .7
Encroach Node=123348
       4      .7
Encroach Node=122953
       1      85     155
Encroach Node=122631
       1     283     343
Encroach Node=122529
       1     250     325
Encroach Node=122463
       1     240     335
Encroach Node=122208
       1     281     375
Encroach Node=121777
       4      .7
Encroach Node=121638
       1      85     160
Encroach Node=121589
       1      61     120
Encroach Node=121412
       1     118     180
Encroach Node=121197
       1     118  188.18
Encroach Node=121018
       1      85     195
Encroach Node=120971
       1      90   257.8
Encroach Node=120691
       1      98     220
Encroach Node=120376
       1      80     220
Encroach Node=120331
       4      .7
Encroach Node=120080
       1      72     170
Encroach Node=119886
       1   66.86     150
Encroach Node=119594
       4      .7
Encroach Node=119517
       1     180     380
Encroach Node=119290
       1     220     375
Encroach Node=119031
       1     210     286
Encroach Node=118661
       4      .7
Encroach Node=118310
       4      .7
Encroach Node=118096
       1     150  210.16
Encroach Node=117934
       1   129.5     186
Encroach Node=117873
       1     114     190
Encroach Node=117775
       1     128     210
Encroach Node=117363
       1      76     201
Encroach Node=117180
       4      .7
Encroach Node=116896
       4      .7
Encroach Node=116429
       1     255     366
Encroach Node=116099
       1     140     250
Encroach Node=115825
       4      .7
Encroach Node=115719
       1     200  477.28
Encroach Node=115567
       1     180     516
Encroach Node=115081
       1     175     470
Encroach Node=114608
       1     168     336
Encroach Node=114475
       1     123     248
Encroach Node=114437
       1     120     245
Encroach Node=114208
       4      .7
Encroach Node=113962
       4      .7
Encroach Node=113833
       4      .7
Encroach Node=113789
       1      90  246.54
Encroach Node=113627
       1    41.2     191
Encroach Node=113476
       1   83.77  242.53
Encroach Node=113419
       1   91.37  250.13
Encroach Node=113248
       4      .7
Encroach Node=113056
       4      .7
Encroach Node=113015
       1     100  201.08
Encroach Node=112819
       1     130     187
Encroach Node=112654
       4      .7
Encroach Node=112320
       4      .7
Encroach Node=111900
       4      .7
Encroach Node=111496
       4      .7
Encroach Node=111312
       4      .7
Encroach Node=111267
       4      .7
Encroach Node=110978
       4      .7
Encroach Node=110616
       4      .7
Encroach Node=110180
       4      .7
Encroach Node=109758
       1   57.63     175
Encroach Node=109327
       4      .7
Encroach Node=108894
       4      .7
Encroach Node=108635
       1      90     180
Encroach Node=108504
       4      .7
Encroach Node=108424
       1     132     260
Encroach Node=108380
       1     140     270
Encroach Node=108307
       1     110     260
Encroach Node=108213
       1     100     290
Encroach Node=107920
       1     120  273.49
Encroach Node=107736
       1      98  180.88
Encroach Node=107650
       1      80  148.05
Encroach Node=107601
       1      90     154
Encroach Node=107504
       4      .7
Encroach Node=107405
       4      .7
Encroach Node=107338
       1      40     155
Encroach Node=107179
       4      .7
Encroach Node=107062
       1      70     160
Encroach Node=107024
       1     105  188.11
Encroach Node=106800
       1     120  201.92
Encroach Node=106372
       1      65  249.18
Encroach Node=106110
       1      65     165
Encroach Node=105857
       1      75     175
Encroach Node=105603
       1     155   275.5
Encroach Node=105532
       1     135  265.25
Encroach Node=105412
       1     145     250
Encroach Node=105371
       4      .7
Encroach Node=105204
       4      .7
Encroach Node=105077
       1   50.21     255
Encroach Node=104971
       1      45     248
Encroach Node=104813
       1      50     170
Encroach Node=104692
       1      50     190
Encroach Node=104573
       1      50     210
Encroach Node=104533
       1    44.3     186
Encroach Node=104251
       1      75   140.7
Encroach Node=104116
       1      62     117
Encroach Node=103950
       1      51   106.3
Encroach Node=103780
       1      44     130
Encroach Node=103362
       1      72     129
Encroach Node=102926
       1      62     120
Encroach Node=102554
       1      75     140
Encroach Node=102442
       1     112  194.91
Encroach Node=102404
       1     135  209.19
Encroach Node=102305
       1     105     171
Encroach Node=102102
       1      65     145
Encroach Node=101689
       1      65     160
Encroach Node=101264
       1     108     200
Encroach Node=100921
       1   72.24     158
Encroach Node=100740
       1    75.9     180
Encroach Node=100579
       4      .7
Encroach Node=100406
       1      90     240
Encroach Node=100345
       1     109     253
Encroach Node=100237
       1     125     230
Encroach Node=100100
       4      .7
Encroach Node=99972
       1      75     180
Encroach Node=99553
       1      54      95
Encroach Node=99339
       1      84     130
Encroach Node=99114
       1      53     120
Encroach Node=98699
       1      68     128
Encroach Node=98268
       4      .7
Encroach Node=98058
       1      87     136
Encroach Node=97842
       1      55     110
Encroach Node=97637
       1      66     149
Encroach Node=97389
       4      .7
Encroach Node=97129
       1      65     122
Encroach Node=96970
       1    34.1      86
Encroach Node=96879
       1   61.37     113
Encroach Node=96752
       1   45.24  156.31
Encroach Node=96549
       4      .7
Encroach Node=96183
       4      .7
Encroach Node=95739
       4      .7
Encroach Node=95323
       4      .7
Encroach Node=95209
       1      63     150
Encroach Node=95169
       1      70  159.76
Encroach Node=94867
       4      .7
Encroach Node=94452
       1      70     230
Encroach Node=94215
       1      80     280
Encroach Node=93988
       1     190     340
Encroach Node=93595
       4      .7
Encroach Node=93284
       1   103.5  277.53
Encroach Node=93105
       4      .7
Encroach Node=92894
       4      .7
Encroach Node=92800
       1     129  205.02
Encroach Node=92716
       1     110  204.11
Encroach Node=92517
       4      .7
Encroach Node=92454
       1      85  240.01
Encroach Node=92269
       1     200     336
Encroach Node=92028
       1     273  460.36
Encroach Node=91805
       4      .7
Encroach Node=91491
       4      .7
Encroach Node=91189
       1     205  360.45
Encroach Node=91143
       4      .7
Encroach Node=90890
       1      70     170
Encroach Node=90655
       1      70     145
Encroach Node=90428
       4      .7
Encroach Node=90131
       4      .7
Encroach Node=89732
       4      .7
Encroach Node=89240
       4      .7
Encroach Node=88817
       4      .7
Encroach Node=88415
       4      .7
Encroach Node=88070
       1      80     197
Encroach Node=87686
       4      .7
Encroach Node=87411
       4      .7
Encroach Node=87251
       4      .7
Encroach Node=87055
       1      70  187.98
Encroach Node=86859
       1     100     205
Encroach Node=86807
       1     100   222.4
Encroach Node=86704
       1     115     192
Encroach Node=86577
       1      74     154
Encroach Node=86382
       4      .7
Encroach Node=86326
       1      35     119
Encroach Node=86214
       1      35     135
Encroach Node=86105
       1      45     145
Encroach Node=85941
       1   29.37  139.22
Encroach Node=85787
       1   31.55     125
Encroach Node=85655
       1   43.89  144.37
Encroach Node=85588
       1    49.9  137.39
Encroach Node=85482
       4      .7
Encroach Node=85380
       4      .7
Encroach Node=85241
       4      .7
Encroach Node=84982
       4      .7
Encroach Node=84729
       4      .7
Encroach Node=84671
       1      65     170
Encroach Node=84449
       1   27.51     180
Encroach Node=84158
       1   69.94     220
Encroach Node=83953
       1      75     151
Encroach Node=83842
       1      64     127
Encroach Node=83730
       1     102     175
Encroach Node=83688
       1     110     172
Encroach Node=83565
       1     110     210
Encroach Node=83284
       1     205     365
Encroach Node=82918
       1     206     299
Encroach Node=82538
       1      77     153
Encroach Node=82110
       1      52     125
Encroach Node=81698
       1      55     125
Encroach Node=81266
       1      55     125
Encroach Node=81113
       1      70  137.72
Encroach Node=80987
       1     120  192.55
Encroach Node=80951
       1     185     245
Encroach Node=80842
       4      .7
Encroach Node=80434
       1   57.94   137.3
Encroach Node=79990
       4      .7
Encroach Node=79700
       4      .7
Encroach Node=79564
       1     120     260
Encroach Node=79527
       1     140     232
Encroach Node=79337
       4      .7
Encroach Node=79101
       1   58.66     122
Encroach Node=78711
       4      .7
Encroach Node=78411
       4      .7
Encroach Node=78328
       4      .7
Encroach Node=78043
       1      80  163.34
Encroach Node=77857
       1     115  204.07
Encroach Node=77616
       1      94  175.89
Encroach Node=77420
       1      75     170
Encroach Node=77223
       1      80  171.78
Encroach Node=77022
       1      75     155
Encroach Node=76636
       1     112     185
Encroach Node=76385
       4      .7
Encroach Node=76108
       4      .7
Encroach Node=75827
       4      .7
Encroach Node=75714
       4      .7
Encroach Node=75584
       1  111.54   192.7
Encroach Node=75433
       1      60  176.95
Encroach Node=75370
       1      82     200
Encroach Node=75264
       1      55     125
Encroach Node=74968
       1    45.5   119.5
Encroach Node=74804
       1   29.43  129.24
Encroach Node=74660
       1   59.36     135
Encroach Node=74392
       4      .7
Encroach Node=74088
       4      .7
Encroach Node=73914
       4      .7
Encroach Node=73665
       4      .7
Encroach Node=73229
       4      .7
Encroach Node=72784
       1   57.04     133
Encroach Node=72574
       1      64     143
Encroach Node=72462
       4      .7
Encroach Node=72358
       4      .7
Encroach Node=71961
       4      .7
Encroach Node=71719
       4      .7
Encroach Node=71611
       4      .7
Encroach Node=71548
       4      .7
Encroach Node=71397
       4      .7
Encroach Node=71316
       4      .7
Encroach Node=71064
       1   77.54  156.78
Encroach Node=70651
       1   46.34     125
Encroach Node=70429
       4      .7
Encroach Node=70172
       1     122     195
Encroach Node=69796
       4      .7
Encroach Node=69382
       4      .7
Encroach Node=69118
       4      .7
Encroach Node=68954
       1      50     115
Encroach Node=68702
       4      .7
Encroach Node=68647
       4      .7
Encroach Node=68544
       4      .7
Encroach Node=68431
       4      .7
Encroach Node=68372
       4      .7
Encroach Node=68093
       1      80     146
Encroach Node=67673
       4      .7
Encroach Node=67253
       1    53.6  150.24
Encroach Node=66986
       4      .7
Encroach Node=66910
       4      .7
Encroach Node=66798
       4      .7
Encroach Node=66569
       1     145  246.91
Encroach Node=66380
       1     116   218.9
Encroach Node=65957
       4      .7
Encroach Node=65517
       4      .7
Encroach Node=65306
       4      .7
Encroach Node=65111
       4      .7
Encroach Node=64730
       4      .7
Encroach Node=64234
       4      .7
Encroach Node=64018
       4      .7
Encroach Node=63873
       4      .7
Encroach Node=63818
       1      90     225
Encroach Node=63677
       4      .7
Encroach Node=63420
       4      .7
Encroach Node=63277
       1      57     145
Encroach Node=63134
       1   24.69      91
Encroach Node=62990
       1    42.9   118.2
Encroach Node=62828
       4      .7
Encroach Node=62584
       1      65  168.97
Encroach Node=62159
       1      80   165.9
Encroach Node=61958
       4      .7
Encroach Node=61858
       4      .7
Encroach Node=61702
       4      .7
Encroach Node=61291
       1      76     149
Encroach Node=61166
       4      .7
Encroach Node=60868
       4      .7
Encroach Node=60446
       4      .7
Encroach Node=60195
       4      .7
Encroach Node=59982
       1   52.99     140
Encroach Node=59675
       1     105  177.69
Encroach Node=59510
       4      .7
Encroach Node=59229
       4      .7
Encroach Node=59036
       4      .7
Encroach Node=58765
       4      .7
Encroach Node=58524
       1     148     225
Encroach Node=58391
       4      .7
Encroach Node=58253
       4      .7
Encroach Node=57893
       4      .7
Encroach Node=57469
       4      .7
Encroach Node=57050
       4      .7
Encroach Node=56907
       4      .7
Encroach Node=56782
       4      .7
Encroach Node=56638
       4      .7
Encroach Node=56430
       4      .7
Encroach Node=56164
       4      .7
Encroach Node=55988
       1     112  187.38
Encroach Node=55747
       1      85  152.57
Encroach Node=55353
       4      .7
Encroach Node=54918
       4      .7
Encroach Node=54497
       4      .7
Encroach Node=54147
       4      .7
Encroach Node=53988
       4      .7
Encroach Node=53664
       4      .7
Encroach Node=53399
       1    49.1     166
Encroach Node=53007
       4      .7
Encroach Node=52723
       4      .7
Encroach Node=52631
       4      .7
Encroach Node=52540
       4      .7
Encroach Node=52237
       4      .7
Encroach Node=51843
       4      .7
Encroach Node=51483
       4      .7
Encroach Node=51311
       4      .7
Encroach Node=51084
       1    72.1     185
Encroach Node=50676
       1      60  140.88
Encroach Node=50222
       1      65     148
Encroach Node=49977
       1     105  198.53
Encroach Node=49792
       1      75     153
Encroach Node=49378
       1      47     120
Encroach Node=49063
       1   55.76     150
Encroach Node=48561
       1     140  276.22
Encroach Node=48422
       1   227.5     313
Encroach Node=48116
       1     150  276.88
Encroach Node=47937
       1   70.45     185
Encroach Node=47806
       1   79.66     185
Encroach Node=47584
       1     115     215
Encroach Node=47293
       4      .7
Encroach Node=46865
       4      .7
Encroach Node=46623
       1   64.75     190
Encroach Node=46378
       1      55     175
Encroach Node=46144
       1     100     300
Encroach Node=45976
       1     130  316.14
Encroach Node=45589
       1     175     310
Encroach Node=45341
       1      75     230
Encroach Node=45160
       4      .7
Encroach Node=45086
       1      75     185
Encroach Node=44915
       1     110  193.54
Encroach Node=44718
       4      .7
Encroach Node=44297
       4      .7
Encroach Node=43862
       4      .7
Encroach Node=43675
       1      65     156
Encroach Node=43454
       1      61     230
Encroach Node=43274
       1      55     184
Encroach Node=42879
       1      55     193
Encroach Node=42736
       1      82     195
Encroach Node=42594
       1     110     213
Encroach Node=42512
       4      .7
Encroach Node=42372
       1      88     177
Encroach Node=42155
       1      46     165
Encroach Node=41733
       1      57     190
Encroach Node=41302
       1    54.5     170
Encroach Node=41035
       1     160     265
Encroach Node=40767
       1     105     210
Encroach Node=40600
       1      75     197
Encroach Node=40449
       1   60.68     170
Encroach Node=40313
       4      .7
Encroach Node=40040
       1      58     133
Encroach Node=39622
       1      56     136
Encroach Node=39181
       4      .7
Encroach Node=38931
       4      .7
Encroach Node=38758
       4      .7
Encroach Node=38606
       4      .7
Encroach Node=38357
       4      .7
Encroach Node=37912
       4      .7
Encroach Node=37492
       4      .7
Encroach Node=37064
       4      .7
Encroach Node=36669
       4      .7
Encroach Node=36252
       4      .7
Encroach Node=35791
       4      .7
Encroach Node=35379
       4      .7
Encroach Node=34938
       1   65.49     160
Encroach Node=34516
       4      .7
Encroach Node=34272
       1   99.25  171.25
Encroach Node=34089
       4      .7
Encroach Node=33951
       1      60     140
Encroach Node=33707
       4      .7
Encroach Node=33256
       4      .7
Encroach Node=32799
       4      .7
Encroach Node=32368
       4      .7
Encroach Node=32223
       1    85.7     234
Encroach Node=31961
       4      .7
Encroach Node=31841
       4      .7
Encroach Node=31683
       1    38.2     126
Encroach Node=31382
       4      .7
Encroach Node=31202
       4      .7
Encroach Node=31062
       1  125.68  218.68
Encroach Node=30868
       1  132.11  212.69
Encroach Node=30654
       4      .7
Encroach Node=30263
       4      .7
Encroach Node=30068
       4      .7
Encroach Node=29964
       4      .7
Encroach Node=29841
       4      .7
Encroach Node=29674
       4      .7
Encroach Node=29326
       4      .7
Encroach Node=28981
       4      .7
Encroach Node=28595
       4      .7
Encroach Node=28285
       4      .7
Encroach Node=28030
       4      .7
Encroach Node=27710
       4      .7
Encroach Node=27481
       4      .7
Encroach Node=27294
       4      .7
Encroach Node=26958
       4      .7
Encroach Node=26683
       1  126.48  279.38
Encroach Node=26583
       1  133.46  246.63
Encroach Node=26423
       4      .7
Encroach Node=26026
       4      .7
Encroach Node=25582
       4      .7
Encroach Node=25173
       4      .7
Encroach Node=24753
       4      .7
Encroach Node=24309
       4      .7
Encroach Node=24094
       4      .7
Encroach Node=23887
       4      .7
Encroach Node=23652
       4      .7
Encroach Node=23468
       4      .7
Encroach Node=23048
       4      .7
Encroach Node=22633
       4      .7
Encroach Node=22266
       4      .7
Encroach Node=21951
       1     225     336
Encroach Node=21689
       4      .7
Encroach Node=21332
       1      75     200
Encroach Node=21069
       1      85     210
Encroach Node=20910
       1      75     205
Encroach Node=20512
       1      70     225
Encroach Node=20250
       1      94     245
Encroach Node=20065
       1  135.45  236.37
Encroach Node=19964
       1  133.28  237.24
Encroach Node=19692
       4      .7
Encroach Node=19226
       4      .7
Encroach Node=18824
       1     188   315.7
Encroach Node=18674
       1     225  333.42
Encroach Node=18439
       1  166.55  275.86
Encroach Node=18024
       4      .7
Encroach Node=17898
       4      .7
Encroach Node=17744
       1   54.92   150.5
Encroach Node=17510
       4      .7
Encroach Node=17085
       4      .7
Encroach Node=16768
       4      .7
Encroach Node=16649
       4      .7
Encroach Node=16505
       4      .7
Encroach Node=16245
       1  139.64   237.2
Encroach Node=15976
       1     130  243.21
Encroach Node=15743
       4      .7
Encroach Node=15558
       1     150     270
Encroach Node=15392
       1     135     260
Encroach Node=15001
       1      85     200
Encroach Node=14883
       1   64.15     180
Encroach Node=14759
       4      .7
Encroach Node=14543
       1      90     200
Encroach Node=14115
       1   44.37     130
Encroach Node=13720
       4      .7
Encroach Node=13258
       1      72     164
Encroach Node=12841
       4      .7
Encroach Node=12651
       1   68.21  156.81
Encroach Node=12438
       1      75  147.57
Encroach Node=12024
       1      59     125
Encroach Node=11575
       1   55.22     150
Encroach Node=11145
       1     100  208.71
Encroach Node=10724
       1      42     173
Encroach Node=10313
       1   38.44  180.63
Encroach Node=10070
       1      87     212
Encroach Node=9923
       1     100     222
Encroach Node=9825
       1     121   242.5
Encroach Node=9464
       1     140  254.83
Encroach Node=9001
       1     105     212
Encroach Node=8761
       1      90     191
Encroach Node=8567
       1     110     205
Encroach Node=8374
       1   97.32     260
Encroach Node=8146
       1   70.09     280
Encroach Node=7972
       1   54.64     200
Encroach Node=7751
       1      60     160
Encroach Node=7633
       1      80     180
Encroach Node=7327
       1      55     160
Encroach Node=6897
       1   51.01  121.47
Encroach Node=6471
       4      .7
Encroach Node=6058
       4      .7
Encroach Node=5833
       1  104.26  180.09
Encroach Node=5571
       4      .7
Encroach Node=5225
       4      .7
Encroach Node=5043
       1      81     160
Encroach Node=4708
       1      60     190
Encroach Node=4331
       1      69     185
Encroach Node=4015
       1   31.27     235
Encroach Node=3882
       1   72.02   208.8
Encroach Node=3506
       1   72.09  170.97
Encroach Node=3073
       4      .7
Encroach Node=2940
       4      .7
Encroach Node=2774
       4      .7
Encroach Node=2635
       4      .7
Encroach Node=2215
       1    46.1     141
Encroach Node=1801
       4      .7
Encroach Node=1373
       4      .7
Encroach Node=982
       4      .7
Encroach Node=674
       1     110     270
Encroach Node=473
       1     120     340
Encroach Node=418
       1     150     370
Encroach Node=189
       1     261     590
Computation Interval=1HOUR
Output Interval=1HOUR
Run HTab= 0
Run UNet= 0
Run PostProcess= 0
UNET Theta= 1
UNET Theta Warmup= 1
UNET ZTol= 0.02
UNET ZSATol= 0.05
UNET MxIter= 20
UNET MaxInSteps= 0
UNET DtIC= 0
UNET DtMin= 0
UNET MaxCRTS= 20
UNET WFStab= 2
UNET SFStab= 1
UNET WFX= 1
UNET SFX= 1
UNET DSS MLevel= 4
UNET DZMax Abort= 100
UNET Convert EG Bridges=-1
UNET Use Existing IB Tables=-1
UNET Froude Reduction=False
UNET Froude Limit= 1
UNET Froude Power= 10
Instantaneous Interval=1HOUR
DSS File=dss
Write IC File= 0
Echo Input=False
Echo Output=False
Write Detailed= 0
Detailed Automatic Start=False, 10

--- lds_big_laurel_crk.f01 (steady flow) ---

Flow Title=lds_big_laurel_crk
Program Version=3.13
Number of Profiles= 2
Profile Names=100YR,100FW
River Rch & RM=Big_Laurel_Creek,Main_Branch     ,177735
    1140    1140
River Rch & RM=Big_Laurel_Creek,Main_Branch     ,169421
    1370    1370
River Rch & RM=Big_Laurel_Creek,Main_Branch     ,162884
    1610    1610
River Rch & RM=Big_Laurel_Creek,Main_Branch     ,159883
    1850    1850
River Rch & RM=Big_Laurel_Creek,Main_Branch     ,156676
    2100    2100
River Rch & RM=Big_Laurel_Creek,Main_Branch     ,154770
    2300    2300
River Rch & RM=Big_Laurel_Creek,Main_Branch     ,148001
    3860    3860
River Rch & RM=Big_Laurel_Creek,Main_Branch     ,146994
    3950    3950
River Rch & RM=Big_Laurel_Creek,Main_Branch     ,142748
    4240    4240
River Rch & RM=Big_Laurel_Creek,Main_Branch     ,139401
    4820    4820
River Rch & RM=Big_Laurel_Creek,Main_Branch     ,138295
    4950    4950
River Rch & RM=Big_Laurel_Creek,Main_Branch     ,133730
    5070    5070
River Rch & RM=Big_Laurel_Creek,Main_Branch     ,129265
    5350    5350
River Rch & RM=Big_Laurel_Creek,Main_Branch     ,128388
    5430    5430
River Rch & RM=Big_Laurel_Creek,Main_Branch     ,122208
    5720    5720
River Rch & RM=Big_Laurel_Creek,Main_Branch     ,121777
    5830    5830
River Rch & RM=Big_Laurel_Creek,Main_Branch     ,116099
    5960    5960
River Rch & RM=Big_Laurel_Creek,Main_Branch     ,113962
    6020    6020
River Rch & RM=Big_Laurel_Creek,Main_Branch     ,109758
    6850    6850
River Rch & RM=Big_Laurel_Creek,Main_Branch     ,109327
    6970    6970
River Rch & RM=Big_Laurel_Creek,Main_Branch     ,101689
    7120    7120
River Rch & RM=Big_Laurel_Creek,Main_Branch     ,101264
    7220    7220
River Rch & RM=Big_Laurel_Creek,Main_Branch     ,92269
    7290    7290
River Rch & RM=Big_Laurel_Creek,Main_Branch     ,90890
    7390    7390
River Rch & RM=Big_Laurel_Creek,Main_Branch     ,88070
    7450    7450
River Rch & RM=Big_Laurel_Creek,Main_Branch     ,86704
    7560    7560
River Rch & RM=Big_Laurel_Creek,Main_Branch     ,82918
    7600    7600
River Rch & RM=Big_Laurel_Creek,Main_Branch     ,80842
    7710    7710
River Rch & RM=Big_Laurel_Creek,Main_Branch     ,79700
    7790    7790
River Rch & RM=Big_Laurel_Creek,Main_Branch     ,76108
    7890    7890
River Rch & RM=Big_Laurel_Creek,Main_Branch     ,70651
    8060    8060
River Rch & RM=Big_Laurel_Creek,Main_Branch     ,67673
    9220    9220
River Rch & RM=Big_Laurel_Creek,Main_Branch     ,66798
    9290    9290
River Rch & RM=Big_Laurel_Creek,Main_Branch     ,60446
    9420    9420
River Rch & RM=Big_Laurel_Creek,Main_Branch     ,58524
    9540    9540
River Rch & RM=Big_Laurel_Creek,Main_Branch     ,57893
    9610    9610
River Rch & RM=Big_Laurel_Creek,Main_Branch     ,49977
    9950    9950
River Rch & RM=Big_Laurel_Creek,Main_Branch     ,49378
    9990    9990
River Rch & RM=Big_Laurel_Creek,Main_Branch     ,45160
   10090   10090
River Rch & RM=Big_Laurel_Creek,Main_Branch     ,40767
   10230   10230
River Rch & RM=Big_Laurel_Creek,Main_Branch     ,40040
   10290   10290
River Rch & RM=Big_Laurel_Creek,Main_Branch     ,26423
   13560   13560
River Rch & RM=Big_Laurel_Creek,Main_Branch     ,23887
   13690   13690
River Rch & RM=Big_Laurel_Creek,Main_Branch     ,22633
   13710   13710
River Rch & RM=Big_Laurel_Creek,Main_Branch     ,19692
   13960   13960
River Rch & RM=Big_Laurel_Creek,Main_Branch     ,18024
   14060   14060
River Rch & RM=Big_Laurel_Creek,Main_Branch     ,17510
   14150   14150
River Rch & RM=Big_Laurel_Creek,Main_Branch     ,9001
   14240   14240
River Rch & RM=Big_Laurel_Creek,Main_Branch     ,2215
   14310   14310
Boundary for River Rch & Prof#=Big_Laurel_Creek,Main_Branch     , 1
Up Type= 3
Up Slope=0.312
Dn Type= 3
Dn Slope=0.0012
Boundary for River Rch & Prof#=Big_Laurel_Creek,Main_Branch     , 2
Up Type= 3
Up Slope=0.312
Dn Type= 3
Dn Slope=0.0012
DSS Import GetInterval= 0
DSS Import GetPeak= 0
DSS Import FillOption= 0

--- lds_big_laurel_crk.g20 (geometry) ---

Geom Title=lds_big_laurel_crk
Program Version=3.13

River Reach=Big_Laurel_Creek,Main_Branch
Reach XY= 30
  962152.6772791  817992.5794318  964251.5490366  813951.6945567
  962222.0354757  808875.4787495  963427.5905396  805287.9790066
  951547.2302597  805637.0457078  949196.6663216  803283.7902361
  946489.5479343  807725.2404345  942957.6476129  806305.7524964
  939134.2372114  809326.6178646  936384.0635057  805198.6667966
  931713.8810954  805108.5188593  928752.4660489  811194.1529316
  925505.8078528  810178.3110371  923927.2623697  804421.4977624
  920215.0661736  808289.7701283  919187.1144267  806104.7006788
  910078.1733515  808958.4769168  909744.4928406  810780.2651319
  905839.8919416  808658.4334055   901802.088811  810629.5710049
  901826.3074917  808585.7773635    893678.04314  812908.8246678
   890951.406014  808753.2136891  888891.4672682  810416.2352251
  890286.7365256  811765.7576305  886634.1750029  811583.8998881
  888241.3799922  806820.0105302  884200.5821721  805030.5145722
  885052.7956259  801767.4931224  880645.3767346  797785.4235802

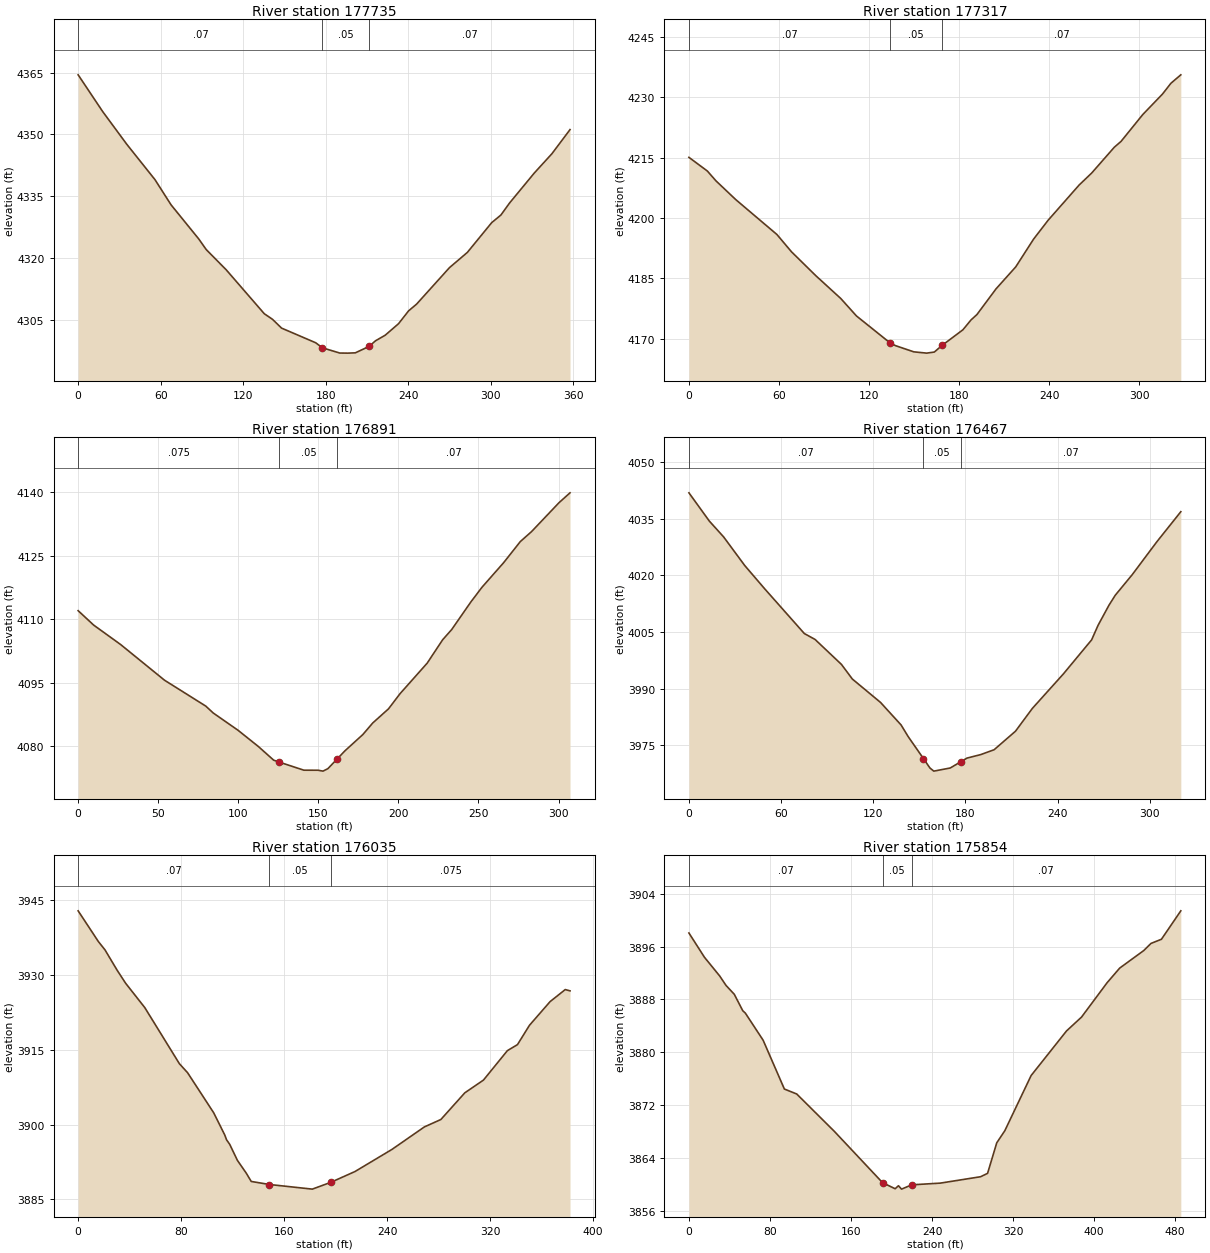
Type RM Length L Ch R = 1 ,177735  ,374.59,418.48,417.08
BEGIN DESCRIPTION:
177657.4
END DESCRIPTION:
XS GIS Cut Line= 6
  962311.2063495  817974.9205959  962286.5349832   817885.206909
   962254.014335  817858.2925981  962194.5783517  817829.1353427
   962167.665065  817826.8934222  962051.0370672  817881.8424921
#Sta/Elev= 30
       0 4364.47   17.95 4355.51   35.32 4347.64   55.86 4339.04   67.57 4332.92
   87.71 4324.64   93.13 4322.07   107.6 4317.18  135.34  4306.5  141.29 4305.15
  147.91 4303.01  172.69 4299.46  177.66 4298.22  190.22 4296.96  196.11 4296.94
  201.54 4297.01  211.53 4298.57  216.24 4299.94  223.23 4301.28  232.95 4304.08
  240.24 4307.19  246.07 4308.83     270 4317.69  282.95 4321.37  300.67  4328.6
  307.37 4330.45  313.65 4333.36  331.67 4340.65  344.42 4345.31  357.62 4351.18
#Mann= 3 , 0 , 0
       0     .07       0  177.66     .05       0  211.53     .07       0
Bank Sta=177.66,211.53
Exp/Cntr=0.3,0.1

Type RM Length L Ch R = 1 ,177317  ,449.11,425.91,404.7
BEGIN DESCRIPTION:
177238.9
END DESCRIPTION:
XS GIS Cut Line= 6
  962511.9406726  817631.7664606   962478.297528   817543.174246
   962454.747634  817507.2881567   962439.048046  817493.8315134
  962416.6196243  817484.8607592  962273.0783398  817505.0462363
#Sta/Elev= 30
       0 4215.04   12.27 4211.65   17.98 4209.22   31.22 4204.55   58.62  4195.9
   68.28 4191.63    84.5 4185.69  101.14 4180.03  111.62 4175.69  134.13 4168.97
  137.69 4168.32  149.77  4166.8  158.37 4166.48  163.44 4166.75  168.67 4168.41
  182.52 4172.28  187.89 4174.71  191.85 4176.06  204.57 4182.43  217.67 4187.87
  229.58 4194.77  239.29 4199.46  259.91 4208.18  268.21 4211.13  283.33 4217.55
  287.82    4219  302.32 4225.67  315.43 4230.74  321.02 4233.41  327.63 4235.51
#Mann= 3 , 0 , 0
       0     .07       0  134.13     .05       0  168.67     .07       0
Bank Sta=134.13,168.67
Exp/Cntr=0.3,0.1

Type RM Length L Ch R = 1 ,176891  ,428.1,424.35,409.93
BEGIN DESCRIPTION:
176813.0
END DESCRIPTION:
XS GIS Cut Line= 6
  962657.7249017  817206.7489444  962615.1110028  817171.9843275
   962572.497104  817115.9137853  962535.4905666  817102.4561177
  962467.0838292  817111.4278961  962397.5556195  817132.7348455
#Sta/Elev= 30
       0 4112.07    9.69 4108.67   26.56 4104.07   53.95 4095.65   79.73 4089.53
   84.35 4087.91   99.85 4083.83  112.53    4080  122.12 4076.76  125.68  4076.3
  140.97  4074.4  149.84 4074.39   152.9 4074.18  155.95 4074.76  161.79 4077.07
  166.67    4079  177.76 4082.81  183.99 4085.56  193.79 4088.88  201.02 4092.47
  217.94 4099.67  227.62  4105.2  233.28 4107.62  245.19 4114.11  252.18  4117.6
  265.71 4123.41  276.12 4128.39   283.1 4130.73  300.28 4137.57  307.15  4139.9
#Mann= 3 , 0 , 0
       0    .075       0  125.68     .05       0  161.79     .07       0
Bank Sta=125.68,161.79
Exp/Cntr=0.3,0.1

Type RM Length L Ch R = 1 ,176467  ,419.62,432,417.9
BEGIN DESCRIPTION:
176388.7
END DESCRIPTION:
XS GIS Cut Line= 6
  962813.6023814  816827.7087199  962736.2238656  816731.2672234
  962714.9169162  816717.8095559  962694.7314391  816712.2032186
  962639.7823692  816716.6880836  962551.1901546  816751.4527005
#Sta/Elev= 30
       0 4041.81    13.3 4034.32   22.58 4030.14   36.32 4022.57   49.36 4016.38
   75.11 4004.56   82.11 4002.99   99.27 3996.39  106.36 3992.52  124.72 3986.32
  138.13 3980.34  142.67  3977.3  152.64 3971.47  156.88 3968.96  159.39 3968.13
  170.11 3968.96  176.82 3970.58     181 3971.58  189.98 3972.51  198.65 3973.79
  212.58  3978.7  223.53 3984.72   243.7 3993.84  262.15 4002.89  266.32 4006.72
  273.42 4012.05   277.5 4014.68   288.6 4020.16  304.57 4028.84   320.2 4036.81
#Mann= 3 , 0 , 0
       0     .07       0  152.64     .05       0  176.82     .07       0
Bank Sta=152.64,176.82
Exp/Cntr=0.3,0.1

Type RM Length L Ch R = 1 ,176035  ,140.18,180.69,196.07
BEGIN DESCRIPTION:
175956.7
END DESCRIPTION:
XS GIS Cut Line= 6
  962887.6154561  816436.3333242  962882.0080947  816357.8343603
  962852.8518634  816326.4351844  962812.4809091  816301.7638181
  962767.6240657  816290.5490952  962616.2324751  816358.9558326
#Sta/Elev= 30
       0 3942.91   15.71 3936.75   20.85 3935.08   30.43 3930.94   36.92 3928.37
   51.76  3923.5    78.7 3912.22   85.02 3910.43  105.32 3902.38  113.93 3897.92
   115.3 3896.97  117.79 3896.04  123.76 3892.83  130.74 3890.22  134.49  3888.6
  148.633887.988  181.95 3887.06  196.453888.438   215.1 3890.59  243.77 3895.02
  269.05 3899.55  281.82 3901.03  300.45 3906.39  314.91 3908.94   333.5 3914.85
  341.35 3916.06  350.67 3919.94  366.69 3924.69  378.47 3927.11  382.17 3926.85
#Mann= 3 , 0 , 0
       0     .07       0  148.63     .05       0  196.45    .075       0
Bank Sta=148.63,196.45
Exp/Cntr=0.3,0.1

Type RM Length L Ch R = 1 ,175854  ,191.09,240.17,265.57
BEGIN DESCRIPTION:
175776.0
END DESCRIPTION:
XS GIS Cut Line= 6
  963008.7283189  816363.4417218  962949.2933598  816212.0501312
  962895.4657622  816159.3429818  962850.6089188  816144.7648661
  962763.1381765   816148.129283  962659.9678463  816186.2572926
#Sta/Elev= 30
       0 3898.07   15.34 3894.39   30.34 3891.56   36.68 3890.11   44.73 3888.79
   53.15 3886.29   55.68 3885.93   73.25 3881.82   94.23 3874.42  106.42 3873.67
  143.53 3868.01  191.21 3860.22  203.57 3859.31  206.84 3859.76  209.92 3859.25
  219.88  3859.9  248.17 3860.16  287.96 3861.13  294.82 3861.64   303.9 3866.27
  311.92 3868.12  337.84 3876.47   372.8 3883.23  387.57 3885.32  412.87 3890.54
  425.26 3892.75  449.03 3895.41  456.16 3896.49  466.48 3897.12  485.61 3901.43
#Mann= 3 , 0 , 0
       0     .07       0  191.21     .05       0  219.88     .07       0
Bank Sta=191.21,219.88
Exp/Cntr=0.3,0.1

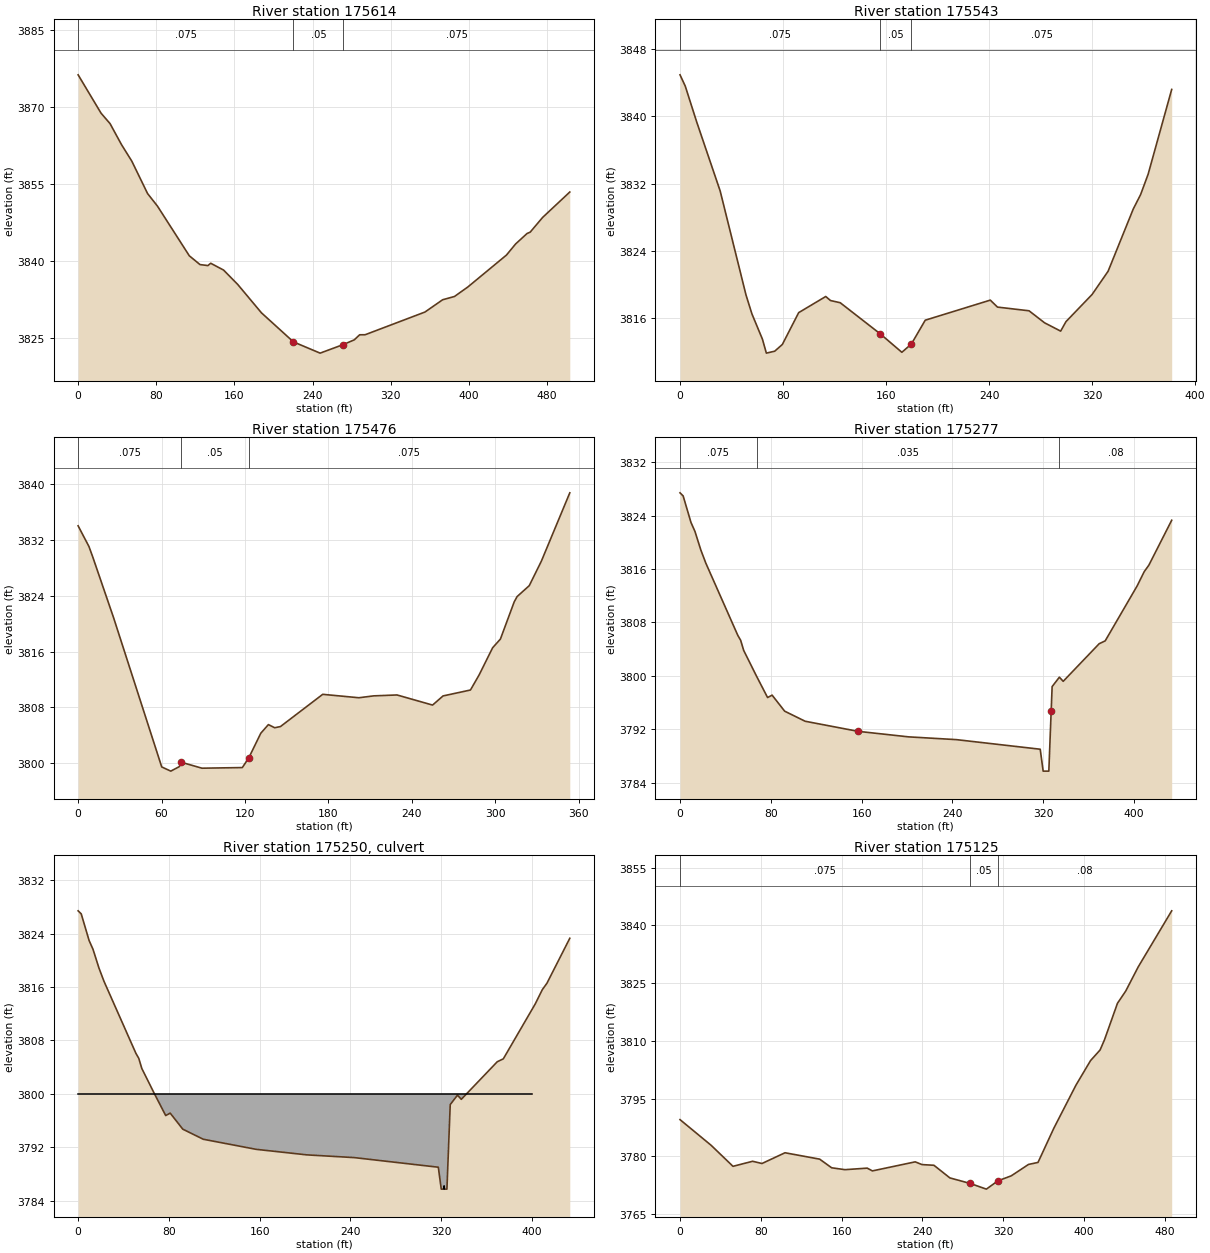
Type RM Length L Ch R = 1 ,175614  ,118.46,70.35,123.88
BEGIN DESCRIPTION:
175535.8
END DESCRIPTION:
XS GIS Cut Line= 6
  963146.6632661  816181.7714035   963024.428931  815982.1595768
  962995.2716755  815949.6379044  962949.2933598  815933.9383165
  962877.5232297   815944.030543  962793.4169043  816005.7094708
#Sta/Elev= 30
       0 3876.18   23.49 3868.71   32.72 3866.67   44.28 3862.63   54.96 3859.37
    71.1 3853.06   81.17 3850.63  113.83 3840.94  124.77 3839.23  132.86 3839.04
  135.73 3839.49  148.91 3838.16  163.34 3835.37   187.7 3829.83  220.45 3824.17
  247.73 3821.99  271.413823.658  282.71 3824.58   288.2 3825.56   293.8 3825.57
  355.03 3829.99  373.12 3832.38  385.26 3833.02     399 3834.88   438.5 3841.09
  447.85 3843.25  459.59 3845.29  462.72 3845.54  475.48 3848.41   503.3 3853.36
#Mann= 3 , 0 , 0
       0    .075       0  220.45     .05       0  271.41    .075       0
Bank Sta=220.45,271.41
Exp/Cntr=0.3,0.1

Type RM Length L Ch R = 1 ,175543  ,51.22,66.94,63.81
BEGIN DESCRIPTION:
175465.5
END DESCRIPTION:
XS GIS Cut Line= 5
  963172.4018234  816068.5856599   963162.415087  816014.6576931
  963108.4881443  815970.7174869  963072.5365078  815931.7691125
  962958.6891469  815761.9976665
#Sta/Elev= 30
       0 3844.95    4.06 3843.61   13.04  3839.3   31.17 3831.13   51.23 3818.75
   55.82  3816.5      64 3813.48   67.05 3811.82   73.53 3812.05   79.46 3812.85
   92.15 3816.64  113.16 3818.56  116.88 3818.08  124.41 3817.82  155.44 3814.12
  172.27 3811.92  179.65  3812.9  190.43 3815.74  240.95 3818.13  246.53  3817.3
  271.04 3816.86   283.1 3815.43  295.59 3814.44  299.73 3815.57     320  3818.8
  332.45 3821.57  351.99 3828.98   357.7  3830.7  363.51 3833.11  381.82 3843.21
#Mann= 3 , 0 , 0
       0    .075       0  155.44     .05       0  179.65    .075       0
#XS Ineff= 2 , 0
       0  113.16 3818.56  240.95       0 3818.13
Permanent Ineff=
       F       F
Bank Sta=155.44,179.65
Exp/Cntr=0.3,0.1

Type RM Length L Ch R = 1 ,175476  ,34.78,199.74,134.22
BEGIN DESCRIPTION:
175398.5
END DESCRIPTION:
XS GIS Cut Line= 3
  963193.3738674  816029.6372856  963185.3842734  815972.7146293
  963008.6228288  815735.0341952
#Sta/Elev= 30
       0 3834.02    7.75 3831.07   10.43 3829.61   25.52 3820.84   60.14 3799.45
   66.66 3798.85   72.74 3799.49   74.26 3800.12   89.07 3799.27   118.1 3799.36
  122.73 3800.74   131.4 3804.28  136.87 3805.52   141.4 3805.07  145.55 3805.24
  175.95 3809.86  201.96 3809.37  212.63 3809.64  229.39 3809.77  254.97 3808.32
   262.5 3809.63  282.23 3810.48  288.53 3812.67  298.18 3816.54  303.76 3817.78
   313.7 3823.12  315.81 3823.88  324.52 3825.44  333.22 3828.95  353.68 3838.75
#Mann= 3 , 0 , 0
       0    .075       0   74.26     .05       0  122.73    .075       0
Bank Sta=74.26,122.73
Exp/Cntr=0.5,0.3

Type RM Length L Ch R = 1 ,175277  ,178.11,152.11,169.78
BEGIN DESCRIPTION:
175198.8
END DESCRIPTION:
XS GIS Cut Line= 6
  963223.3340765  816015.6562643  963193.3738674  815901.8099275
  963210.3506023  815848.8805319  963200.3648901  815730.0403149
  963179.3928461  815695.0872496  963089.5132428  815668.1237783
#Sta/Elev= 30
       0  3827.4    2.75 3826.94    9.68 3822.95   13.14 3821.63   18.34 3818.84
   22.76 3816.86   50.94 3806.05   53.45 3805.31   56.13 3803.79   67.49 3799.92
   77.17 3796.74   81.15  3797.1   92.21  3794.7  110.27 3793.19  156.84 3791.68
  201.52 3790.85  243.35 3790.44  317.41    3789     320 3785.72     325 3785.72
  327.063794.682  327.91 3798.38   334.3 3799.79  337.67 3799.17  369.37  3804.8
  374.68 3805.23  402.83 3813.46  409.05 3815.59  413.14 3816.56  433.27 3823.29
#Mann= 3 ,-1 , 0
       0    .075       0   67.49    .035       0   334.3     .08       0
Bank Sta=156.84,327.06
Exp/Cntr=0.5,0.3

Type RM Length L Ch R = 2 ,175250  ,,,
BEGIN DESCRIPTION:
175173  Pond Dam
END DESCRIPTION:
Bridge Culvert--1,0,-1,-1, 0
Deck Dist Width WeirC Skew NumUp NumDn MinLoCord MaxHiCord MaxSubmerge Is_Ogee
20,20,2.6,0, 2, 2, , , 0.95, 0, 2,2,,
       0     400
    3800    3800
                
       0     400
    3800    3800
                
BR Coef=-1 , 0 , 0 ,, 0 ,,,0.8,0,,0,
WSPro=,,,, 1 ,,,, 0 ,,,, 0 ,,,,-1 ,-1 ,-1 , 0 , 0 , 0 , 0 , 0
Culvert=1,0.5,,100,0.014,0.5,1,1,1,3785.72,322.5,3775.22,303.25,Culvert #1  , 0 ,0
Culvert Bottom n=0.014
BC Design=,, 0 ,, 0 ,,,,,,

Type RM Length L Ch R = 1 ,175125  ,466.83,350.38,236.69
BEGIN DESCRIPTION:
175046.7
END DESCRIPTION:
XS GIS Cut Line= 6
  963328.3335844  815950.7593767  963348.5190615  815866.6530513
  963346.2761169  815800.4892585  963321.6047506  815651.3406125
  963305.9051627  815616.5770198   963197.127471  815522.3774437
#Sta/Elev= 30
       0 3789.57   30.74 3782.92   52.43 3777.45   71.87 3778.76   81.12 3778.18
  103.93 3780.97  138.24 3779.31  150.07 3777.07  163.24 3776.58   185.3 3776.98
  190.43 3776.26  232.79 3778.61  239.55  3777.9  251.33 3777.72  267.13 3774.44
  287.24    3773  303.25 3771.53  314.53 3773.67  327.86 3774.98  344.94 3777.94
  354.34 3778.46  370.03 3787.35  391.92 3798.53  406.31 3804.88   415.8 3807.66
  420.17 3810.31  432.97 3819.76  441.15 3822.94  453.54 3829.22  486.66 3843.77
#Mann= 3 , 0 , 0
       0    .075       0  287.24     .05       0  314.53     .08       0
Bank Sta=287.24,314.53
Exp/Cntr=0.5,0.3