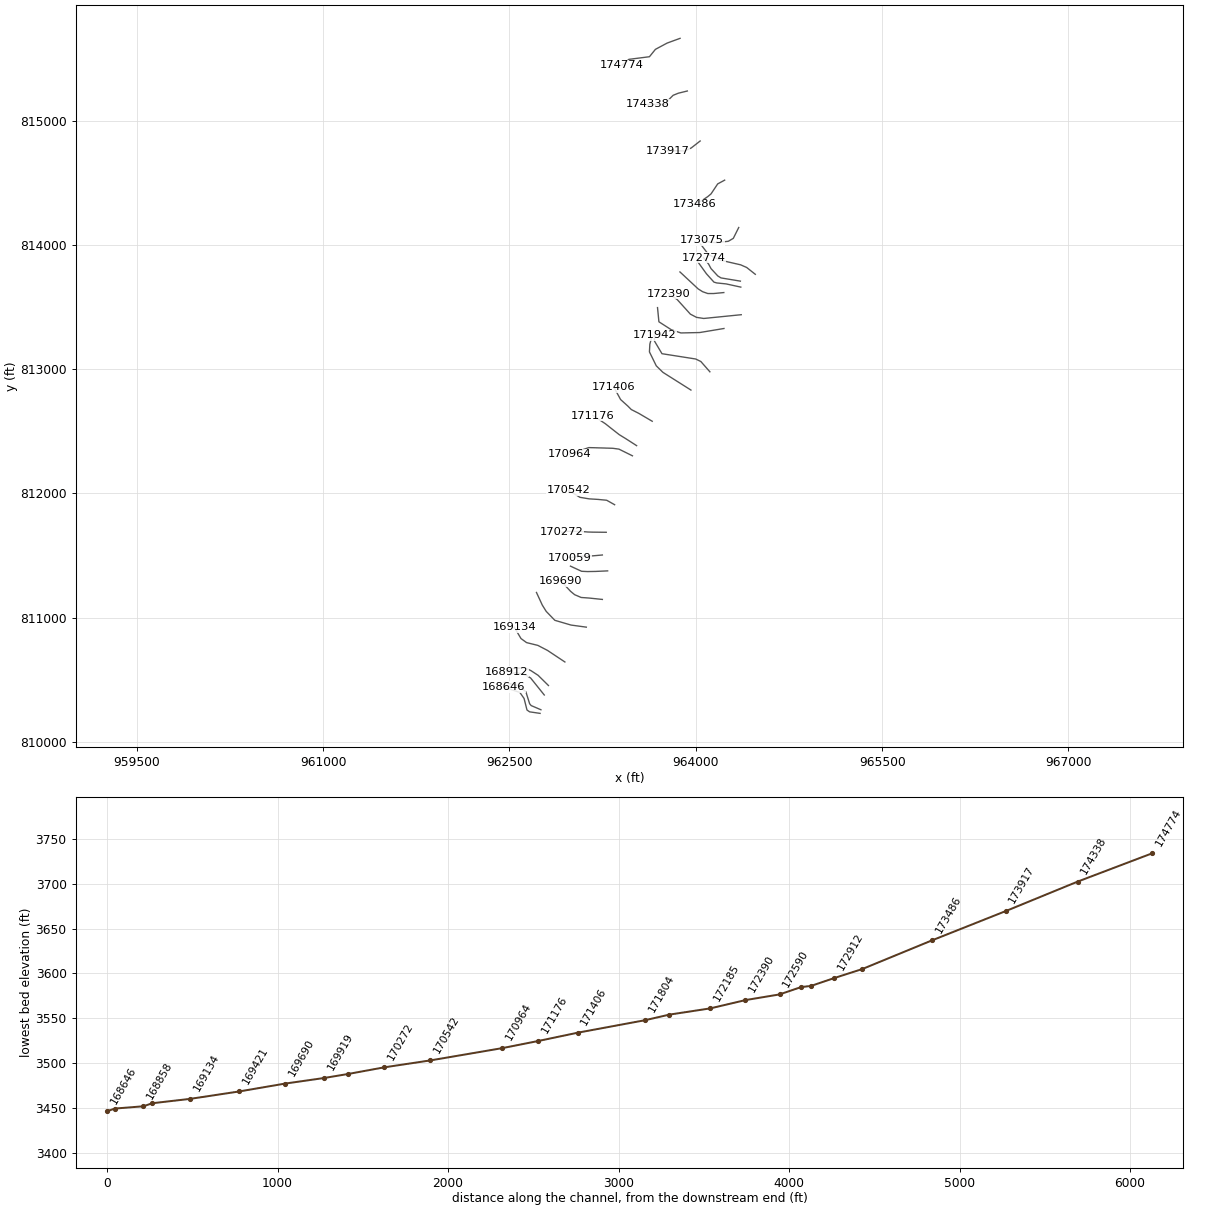
HEC-RAS study lds_big_laurel_crk.prj: lds_big_laurel_crk

--- lds_big_laurel_crk.g20 (geometry) --- (continued)

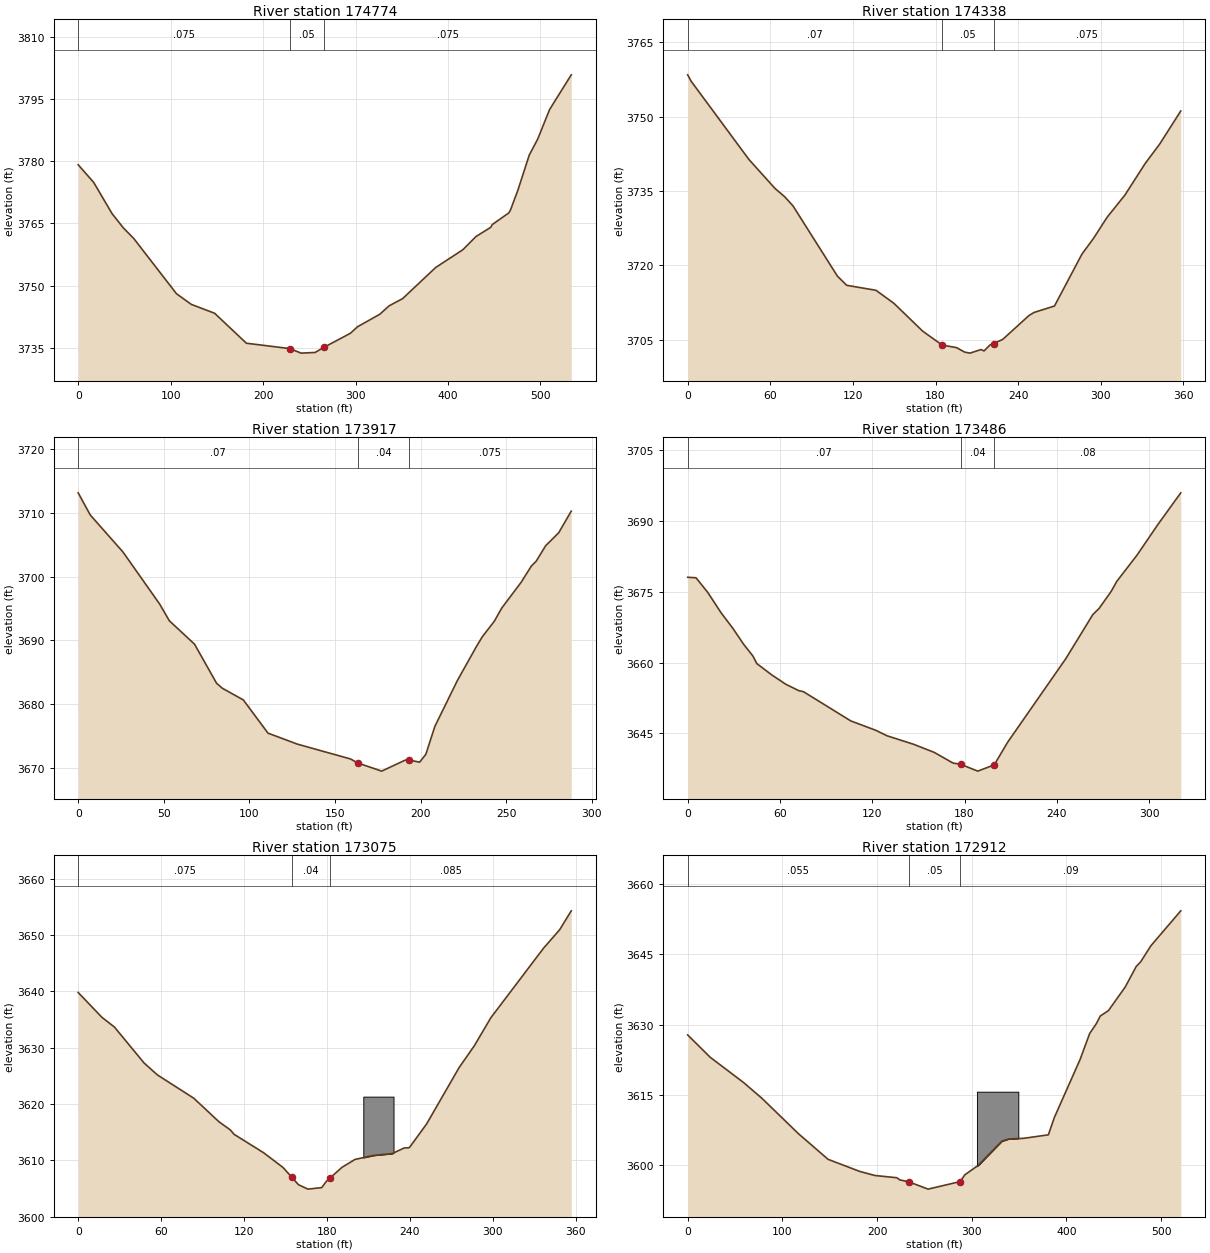
Type RM Length L Ch R = 1 ,174774  ,412.81,435.97,460.78
BEGIN DESCRIPTION:
174696.3
END DESCRIPTION:
XS GIS Cut Line= 6
   963873.342491  815662.5553355  963769.0506885  815624.4263016
  963674.8511124  815573.9631209  963626.6308763  815514.5271377
  963460.6601459  815493.2201882  963406.8325483  815446.1214244
#Sta/Elev= 30
       0 3779.12   16.79 3774.86   36.67 3767.33   48.91 3763.89   60.23 3761.31
  106.32 3748.03  122.35 3745.46  147.56 3743.32  181.92  3736.1  228.88  3734.8
  241.12 3733.71  256.23 3733.87  265.72  3735.1  294.45  3738.5  302.15 3740.07
  326.22 3743.08  336.28 3745.11   350.9 3746.85  386.69 3754.36   416.1 3758.64
  430.27 3761.82  446.21 3764.04  447.82  3764.7   465.7  3767.5  467.42 3768.13
  475.55 3772.97  487.88 3781.45  497.08 3785.34  509.87 3792.43  533.31  3800.8
#Mann= 3 , 0 , 0
       0    .075       0  228.88     .05       0  265.72    .075       0
Bank Sta=228.88,265.72
Exp/Cntr=0.3,0.1

Type RM Length L Ch R = 1 ,174338  ,441.44,421.51,395.51
BEGIN DESCRIPTION:
174260.3
END DESCRIPTION:
XS GIS Cut Line= 6
  963931.6559778  815238.6582675  963858.7643753  815220.7157349
  963817.2719488  815203.8946747   963786.993221  815173.6159469
  963757.8359655  815131.0020481   963614.294681  815131.0020481
#Sta/Elev= 30
       0 3758.44    2.38  3757.2   44.43 3741.37   63.48 3735.49   70.47 3733.83
   76.49 3731.98  108.77  3717.8  115.48 3715.96  136.75 3714.95  149.69 3712.34
   170.6 3706.72  184.78  3703.9  195.26 3703.38  201.11 3702.48  205.04 3702.27
  212.97 3702.99  215.25 3702.72  219.59 3703.93  222.15 3704.19  228.88 3705.06
  247.85 3709.86  251.54 3710.48  266.38 3711.78  286.34 3722.26   294.8 3725.46
   304.7 3729.73  317.47 3734.15  332.22 3740.53  342.89 3744.51  358.09 3751.14
#Mann= 3 , 0 , 0
       0     .07       0  184.78     .05       0  222.15    .075       0
Bank Sta=184.78,222.15
Exp/Cntr=0.3,0.1

Type RM Length L Ch R = 1 ,173917  ,363.51,431.06,461.91
BEGIN DESCRIPTION:
173838.8
END DESCRIPTION:
XS GIS Cut Line= 6
  964034.8273322  814836.0691731  963963.0561778  814779.9986309
  963912.5919729  814756.4487369  963887.9206066  814756.4487369
  963855.3999584  814757.5702091  963771.2936331  814757.5702091
#Sta/Elev= 30
       0 3713.13    7.04 3709.66   26.15 3703.85   47.59 3695.68   53.24 3693.06
   68.01 3689.37   80.85 3683.25   84.19 3682.47   96.49 3680.63   110.9 3675.42
  128.03  3673.7  159.09 3671.37  163.25 3670.75  177.33 3669.46  190.99 3671.18
  193.31 3671.21   199.5 3670.86  203.14 3672.12  208.39 3676.48  221.55 3683.68
  232.39 3688.88  236.05 3690.52  243.15 3692.99  247.49 3695.06  258.72 3699.06
  264.74 3701.63  267.61 3702.41  273.12 3704.83  280.71 3706.85  288.08 3710.26
#Mann= 3 , 0 , 0
       0     .07       0  163.25     .04       0  193.31    .075       0
Bank Sta=163.25,193.31
Exp/Cntr=0.3,0.1

Type RM Length L Ch R = 1 ,173486  ,458.31,410.33,360.42
BEGIN DESCRIPTION:
173407.8
END DESCRIPTION:
XS GIS Cut Line= 6
  964232.1962143  814520.9508209   964176.125672  814490.6720932
  964122.2970503  814409.9301846  964096.5052358  814388.6232352
   964053.891337  814359.4659797  963986.6060718  814326.9453316
#Sta/Elev= 30
       0 3678.09    5.42 3677.98   13.03 3674.89   21.74 3670.54   29.53 3667.18
   36.31  3663.9   42.36  3661.4   44.96 3659.77   54.41 3657.43   63.72  3655.4
   72.07 3654.05   75.33  3653.8  106.02 3647.61  122.41  3645.6  129.54 3644.46
  146.85 3642.65  160.27 3640.93  172.53 3638.66  177.42 3638.41   188.6 3636.95
  199.31 3638.28  208.04 3643.09  245.85 3660.82  263.42 3670.18  267.45 3671.46
  275.38 3675.11  279.02 3677.24  292.06 3682.75  305.68 3689.27  320.58 3696.01
#Mann= 3 , 0 , 0
       0     .07       0  177.42     .04       0  199.31     .08       0
Bank Sta=177.42,199.31
Exp/Cntr=0.3,0.1

Type RM Length L Ch R = 1 ,173075  ,225,163.35,105.38
BEGIN DESCRIPTION:
172997.4
END DESCRIPTION:
XS GIS Cut Line= 6
  964345.4597951  814139.6686759   964301.724424  814052.1979337
  964261.3534697  814028.6480397   964168.275366   814018.554789
  964123.4185226  814019.6762613  964051.6483924  814035.3768734
#Sta/Elev= 30
       0 3639.79   17.18 3635.38   26.16 3633.67   47.67 3627.28   57.26 3625.17
   83.61 3621.03  101.79 3616.86  109.97 3615.42  112.81 3614.62  134.12 3611.36
  148.13 3608.75  154.413607.034  159.33 3605.69  166.11  3604.9  176.18 3605.17
  179.47 3606.27  182.433606.922  190.82 3608.77  200.24 3610.17  213.63 3610.88
  227.07  3611.2  235.71 3612.19  239.54 3612.25  252.13  3616.5   275.5 3626.45
  286.55 3630.34  298.53 3635.32  336.62 3647.65  348.26 3650.92  356.67 3654.28
#Mann= 3 , 0 , 0
       0    .075       0  154.41     .04       0  182.43    .085       0
#Block Obstruct= 1 ,-1
  206.23   228.13621.316
Bank Sta=154.41,182.43
Exp/Cntr=0.3,0.1

Type RM Length L Ch R = 1 ,172912  ,128.63,137.56,56.17
BEGIN DESCRIPTION:
172834.1
END DESCRIPTION:
XS GIS Cut Line= 6
  964478.9088531   813762.871396  964409.3806434    813817.82149
  964361.1593831  813839.1284395  964195.1896769  813877.2564491
  964103.2330454  813920.9918203  964038.1907249  814006.2196179
#Sta/Elev= 30
       0 3627.81   23.77 3623.05   59.04 3617.66    78.3 3614.32  117.09 3606.73
   148.3 3601.28  181.81  3598.7  197.61 3597.84  220.86 3597.36  224.02  3596.9
  233.63 3596.48  253.85 3594.93  287.82 3596.54  292.62 3597.97  306.82    3600
  331.72 3605.15  339.03 3605.63  354.57 3605.76  380.91 3606.51  387.21  3610.2
  414.31 3622.53  424.56 3628.13  431.49 3630.19  435.73 3631.85   444.3 3632.99
  462.19 3638.07   473.7 3642.42  478.36  3643.4  489.22 3646.84  520.72 3654.28
#Mann= 3 , 0 , 0
       0    .055       0  233.63     .05       0  287.82     .09       0
#Block Obstruct= 1 ,-1
  305.46  349.163615.709
Bank Sta=233.63,287.82
Exp/Cntr=0.5,0.3

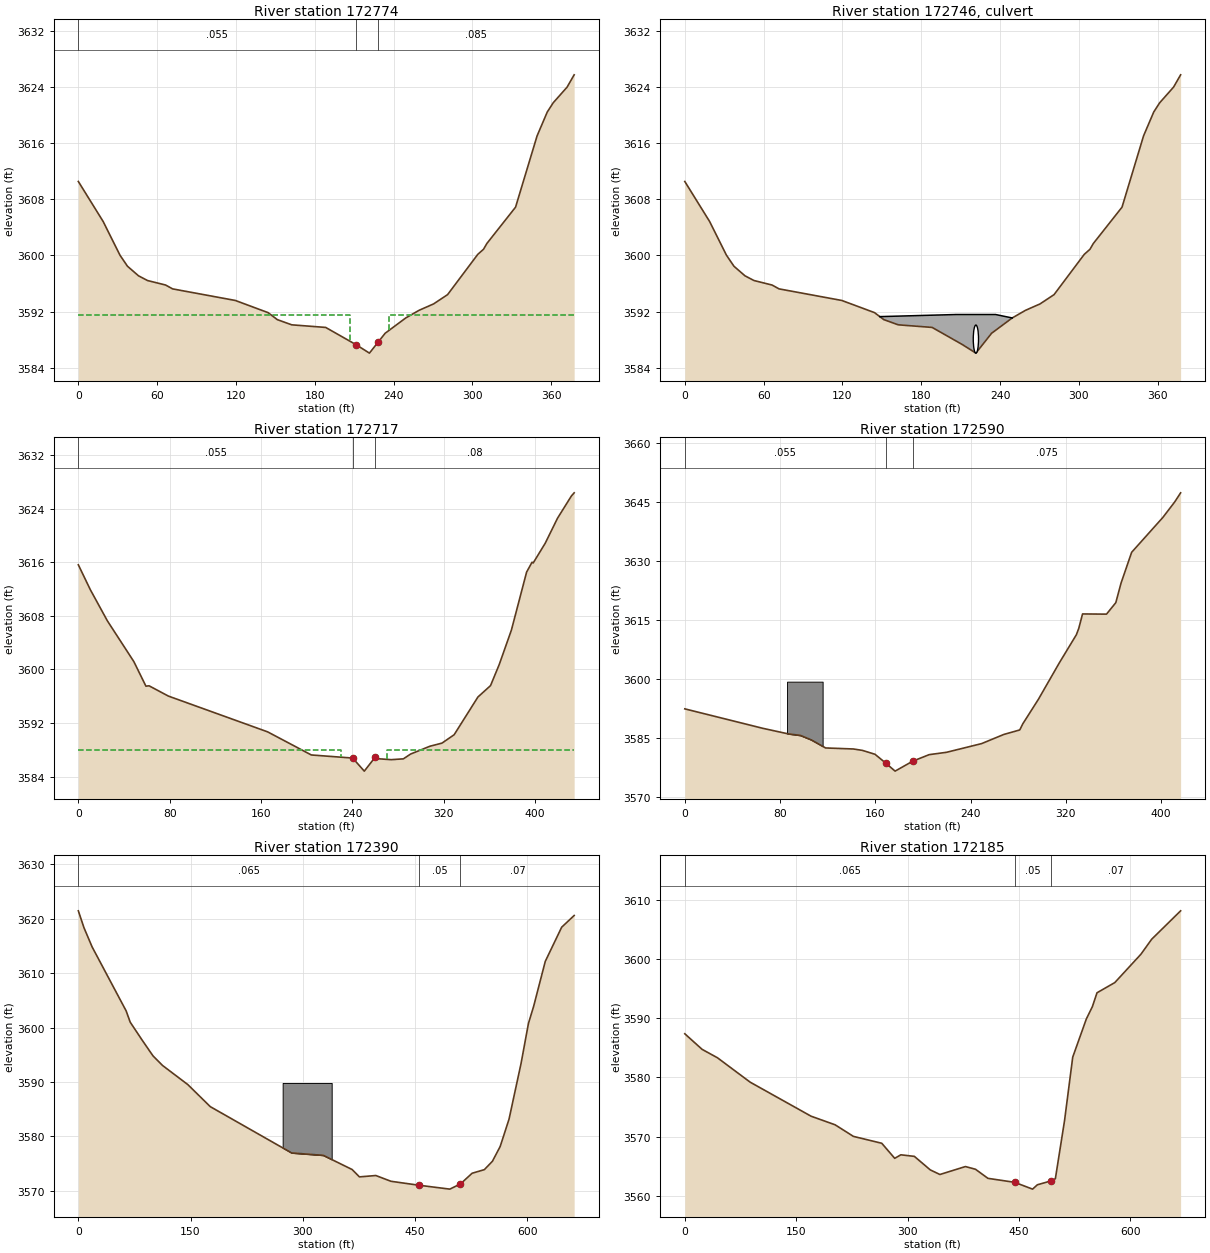
Type RM Length L Ch R = 1 ,172774  ,49.77,57.83,63.56
BEGIN DESCRIPTION:
172696.5
END DESCRIPTION:
XS GIS Cut Line= 6
  964358.9164385   813707.922326  964203.0399829  813733.7151646
  964177.2471443  813749.4147526  964122.2970503  813808.8497117
  964103.2330454  813844.7347768  964061.7406189  813897.4419262
#Sta/Elev= 30
       0 3610.54   18.92 3604.83    31.7 3600.04   37.44 3598.46   45.83  3597.1
   52.66 3596.43   66.41 3595.79   71.77 3595.24  119.52 3593.59  144.39 3591.86
  151.47 3590.86  162.46 3590.12  188.27 3589.75  211.25 3587.31  221.56 3586.09
  228.41 3587.71  233.53 3588.92  249.22  3591.1  259.26 3592.18   270.4  3593.1
  281.05 3594.42  304.05 3600.16  308.39 3600.88  310.93  3601.7  332.79 3606.88
  349.17 3617.03  356.94 3620.44  361.46 3621.75  372.02 3623.98  377.39 3625.73
#Mann= 3 , 0 , 0
       0    .055       0  211.25     .05       0  228.41    .085       0
#XS Ineff= 2 , 0
       0  206.56 3591.59  236.56       0 3591.59
Permanent Ineff=
       F       F
Bank Sta=211.25,228.41
Exp/Cntr=0.5,0.3

Type RM Length L Ch R = 2 ,172746  ,,,
Node Photo=H:\PROJ\06-0741\CE\GIS\DATA\FRENCH_BROAD_RIVER\SHAPEFILES\survey_data\photos\FBSTR_1798.JPG
BEGIN DESCRIPTION:
172665  FBSTR_1798
END DESCRIPTION:
Bridge Culvert--1,0,-1,-1, 0
Deck Dist Width WeirC Skew NumUp NumDn MinLoCord MaxHiCord MaxSubmerge Is_Ogee
24,15,2.6,0, 5, 5, 3591.59, , 0.95, 0, 0,0,,
  148.45  206.56  221.56  236.56  249.22
 3591.29 3591.59 3591.59 3591.59  3591.1
                                        
  153.89  235.41  250.41  265.41  332.45
 3591.44 3591.59 3591.59 3591.59 3591.15
                                        
BR Coef=-1 , 0 , 0 ,, 0 ,,,0.8,-1,,0,
WSPro=,,,, 1 ,,,, 0 ,,,, 0 ,,,,-1 ,-1 ,-1 , 0 , 0 , 0 , 0 , 0
Culvert=1,4,,20,0.024,0.9,1,2,3,3586.09,221.56,3584.83,250.41,Culvert #1  , 0 ,22
Culvert Bottom n=0.024
BC Design=,, 0 ,, 0 ,,,,,,

Type RM Length L Ch R = 1 ,172717  ,291.33,126.47,148.88
BEGIN DESCRIPTION:
172638.7
END DESCRIPTION:
XS GIS Cut Line= 6
  964362.2808554  813659.7010657  964244.5324095  813685.4939043
   964168.275366  813693.3431862  964145.8469443    813700.07202
  964085.2905129  813767.3572851  964013.5203827  813867.1631985
#Sta/Elev= 30
       0 3615.62   10.52  3611.9   25.46 3607.25   48.63 3601.17   59.19 3597.51
   61.96 3597.56   78.84 3596.03  165.76 3590.69  204.05 3587.24  240.24 3586.78
  250.41 3584.83  260.12 3586.95  262.23 3586.68  273.85 3586.54  284.64 3586.66
  290.87 3587.37  307.79 3588.54  318.44 3589.01  329.09 3590.26  349.91 3595.89
  360.95 3597.59  368.58 3600.74  379.22 3605.87  392.54 3614.53  397.29    3616
  398.33  3615.9  408.85 3618.84  419.61 3622.57  431.73 3625.88  434.18 3626.36
#Mann= 3 , 0 , 0
       0    .055       0  240.24     .05       0  260.12     .08       0
#XS Ineff= 2 , 0
       0  230.41    3588  270.41       0    3588
Permanent Ineff=
       F       F
Bank Sta=240.24,260.12
Exp/Cntr=0.5,0.3

Type RM Length L Ch R = 1 ,172590  ,111,200.15,181.09
BEGIN DESCRIPTION:
172512.2
END DESCRIPTION:
XS GIS Cut Line= 6
  964225.4684047  813615.9656946  964143.6039997  813608.1153885
  964096.5052358  813608.1153885  964055.0128093  813622.6945284
    964019.12672  813645.1229501  963872.2210187  813781.9354008
#Sta/Elev= 30
       0 3592.47   65.43 3587.53   86.89 3586.11   97.11 3585.71  106.28 3584.57
  118.26 3582.53  141.59 3582.27   149.2 3581.91  159.73 3580.92  168.72 3578.69
  176.61 3576.64  191.42 3579.17  205.24 3580.83  219.87 3581.43   249.3 3583.64
  267.86 3585.96  281.29 3587.11  283.82 3588.65  296.97 3594.91  314.41 3604.11
  328.85 3611.32  330.88 3612.97  334.02  3616.6  354.15 3616.55  361.96 3619.47
  366.32 3624.41  375.25 3632.27  401.43 3641.12  411.46 3645.09  416.38 3647.39
#Mann= 3 , 0 , 0
       0    .055       0  168.72     .05       0  191.42    .075       0
#Block Obstruct= 1 ,-1
   85.86  115.753599.388
Bank Sta=168.72,191.42
Exp/Cntr=0.3,0.1

Type RM Length L Ch R = 1 ,172390  ,124,205.28,250.16
BEGIN DESCRIPTION:
172312.1
END DESCRIPTION:
XS GIS Cut Line= 6
  964365.6452722  813437.6597932  964063.9835635  813407.3820896
  964005.6700767  813416.3528437  963956.3273441  813442.1456823
   963849.792597  813559.8951524  963780.2643872  813608.1153885
#Sta/Elev= 30
       0 3621.47    7.57 3618.35   18.45 3614.83   63.92 3603.07   69.33    3601
   84.76 3597.81   99.83  3594.8  112.57 3593.04  146.31 3589.53  176.38 3585.47
  285.12 3576.96  327.35 3576.52     366 3573.91  375.69 3572.56  397.62 3572.81
  417.91 3571.75  454.96 3571.03  496.49 3570.31  510.77 3571.27  526.31 3573.23
  542.63 3573.89  553.44 3575.43  563.81 3578.15  575.64 3583.17  591.75 3593.44
  601.58 3600.77   608.5  3603.9  624.09 3612.18  646.01 3618.46  662.68 3620.61
#Mann= 3 , 0 , 0
       0    .065       0  454.96     .05       0  510.77     .07       0
#Block Obstruct= 1 ,-1
  273.07  338.613589.828
Bank Sta=454.96,510.77
Exp/Cntr=0.3,0.1

Type RM Length L Ch R = 1 ,172185  ,249.26,242.74,171.18
BEGIN DESCRIPTION:
172106.8
END DESCRIPTION:
XS GIS Cut Line= 6
   964226.589877  813326.6401811  964031.4629153  813294.1185087
  963880.0713247  813290.7540918  963802.6928089  813316.5469304
  963702.8868956  813380.4677787  963691.6731968  813494.8528318
#Sta/Elev= 30
       0 3587.34   23.31 3584.71   44.08 3583.28   88.03 3579.17  169.99 3573.43
  202.34 3571.98  227.03 3570.02  265.19 3568.86  282.62 3566.32  290.88 3566.91
  309.08 3566.65  330.47 3564.37  343.47 3563.59  377.89 3564.93  391.44 3564.47
  408.15 3562.94  444.04 3562.27  468.28 3561.12  474.64 3561.85  493.053562.507
  498.92 3562.87   511.3 3572.69   522.3 3583.39  540.57 3589.82  548.77 3591.92
  555.01 3594.26  578.98 3595.98  614.15 3600.77  628.57 3603.29  667.58 3608.09
#Mann= 3 , 0 , 0
       0    .065       0  444.04     .05       0  493.05     .07       0
Bank Sta=444.04,493.05
Exp/Cntr=0.3,0.1

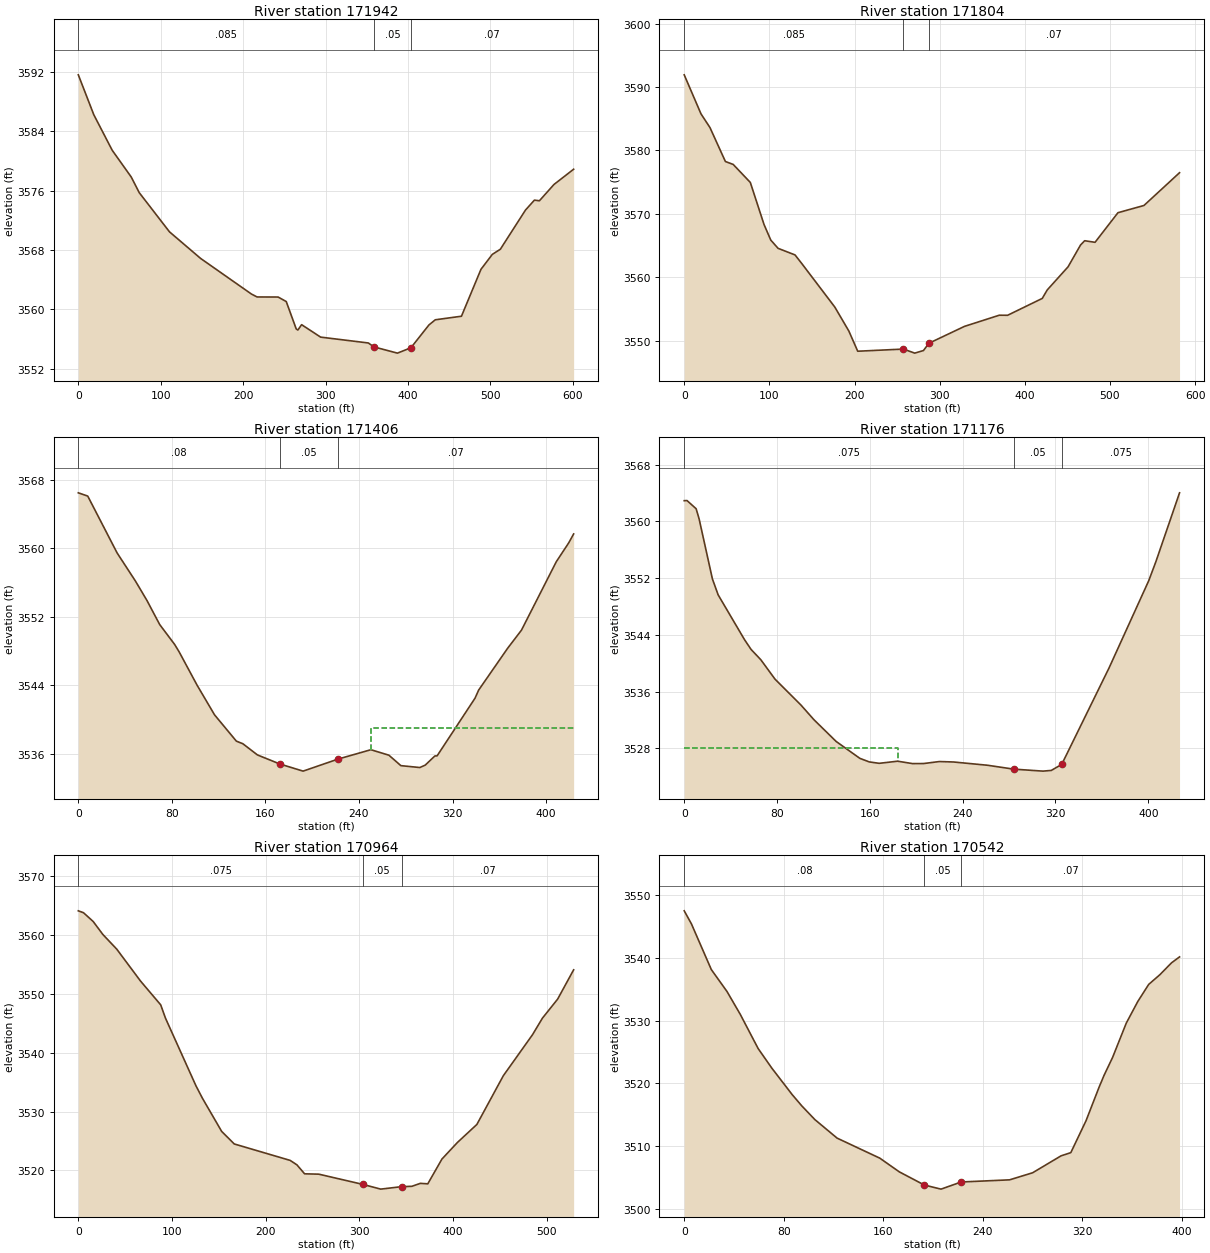
Type RM Length L Ch R = 1 ,171942  ,233.55,138.18,79.46
BEGIN DESCRIPTION:
171864.0
END DESCRIPTION:
XS GIS Cut Line= 6
  964113.3262961  812977.8786843  964040.4336695  813060.8635374
  963998.9412429  813081.0490145  963727.5582619  813123.6629133
  963667.0018305  813225.7117713  963667.0018305  813272.8115593
#Sta/Elev= 30
       0 3591.64   18.82 3586.25   41.12 3581.46   64.22 3577.85   73.93 3575.74
  110.63 3570.45  148.29 3566.87     210 3562.06  216.91 3561.66  242.45 3561.65
  252.32 3561.04  264.43 3557.34  266.44  3557.2  270.95 3557.92  294.04 3556.24
  351.92 3555.45  358.71 3554.92   387.2 3554.08  403.55  3554.8  425.44 3557.88
  433.15 3558.58   464.9 3559.06  488.57 3565.39  502.36 3567.41  512.09  3568.1
  542.61 3573.39  553.43 3574.73  559.47 3574.64  577.16 3576.84  601.01  3578.9
#Mann= 3 , 0 , 0
       0    .085       0  358.71     .05       0  403.55     .07       0
Bank Sta=358.71,403.55
Exp/Cntr=0.3,0.1

Type RM Length L Ch R = 1 ,171804  ,391.02,398.04,444.96
BEGIN DESCRIPTION:
171725.9
END DESCRIPTION:
XS GIS Cut Line= 6
  963960.8132333  812830.9729829   963735.408568  812973.3927951
  963681.5799462  813026.0999446  963626.6308763   813138.241029
   963629.994269  813201.0404049  963643.4519365  813250.3831376
#Sta/Elev= 30
       0 3591.91   19.67 3585.76   30.28 3583.58   48.35 3578.24   57.58 3577.77
   77.65 3574.93   93.76 3568.29  101.67 3565.84  110.23 3564.54  130.15  3563.5
  138.19 3562.12  176.91 3555.27  193.33  3551.5  203.78 3548.31  257.52 3548.65
   270.7 3548.01     281 3548.42  287.43 3549.57  329.17 3552.23  370.03 3553.99
  379.81 3553.98  420.51 3556.64  426.37 3557.98  450.85 3561.63  465.49 3565.07
  470.32 3565.74  482.51 3565.49  509.41 3570.16  539.95  3571.3  581.75 3576.47
#Mann= 3 , 0 , 0
       0    .085       0  257.52     .05       0  287.43     .07       0
Bank Sta=257.52,287.43
Exp/Cntr=0.3,0.1

Type RM Length L Ch R = 1 ,171406  ,230.49,230.24,254.72
BEGIN DESCRIPTION:
171327.8
END DESCRIPTION:
XS GIS Cut Line= 6
   963649.059298  812579.7744549  963540.2816063  812643.6953031
   963480.845623  812673.9740309   963452.810864  812702.0098141
  963394.4963531  812754.7159394  963340.6687555  812853.4014046
#Sta/Elev= 30
       0 3566.47    8.07 3566.09   33.19 3559.45   48.99 3556.14   58.75 3553.89
    69.6 3551.09   82.48 3548.75   86.32 3547.88  101.58 3544.01   116.5 3540.55
  135.16 3537.48  140.68 3537.18  153.18 3535.87  172.39 3534.81  192.22 3533.98
  222.19 3535.39  250.18 3536.48  265.58 3535.84  275.82 3534.62  292.04  3534.4
  296.63 3534.68  304.91 3535.75  306.79 3535.76  339.25  3542.5  342.32 3543.44
  366.99  3548.3  378.95 3550.44  408.73 3558.43   419.4 3560.64  423.54 3561.67
#Mann= 3 , 0 , 0
       0     .08       0  172.39     .05       0  222.19     .07       0
#XS Ineff= 2 , 0
       0                  250.18       0    3539
Permanent Ineff=
       F       F
Bank Sta=172.39,222.19
Exp/Cntr=0.3,0.1

Type RM Length L Ch R = 1 ,171176  ,100.89,211.54,331.23
BEGIN DESCRIPTION:
171097.6
END DESCRIPTION:
XS GIS Cut Line= 6
  963523.4595219  812383.5270451  963432.6253869  812441.8405319
  963383.2826543  812472.1182355  963310.3900277  812529.3112741
   963272.262018  812559.5889777  963172.4561047  812625.7527706
#Sta/Elev= 30
       0 3562.92    2.41 3562.94   10.25 3561.79    12.8 3560.38   24.28  3551.9
   29.22 3549.65   51.89 3543.35   57.61 3541.95   66.05 3540.49   78.25 3537.76
  100.65  3534.1   111.8 3532.04  130.98 3528.97   151.4 3526.59  159.47 3526.09
  168.06 3525.89  183.93 3526.19  196.82 3525.85  206.35 3525.86  219.87 3526.14
  232.02 3526.08  261.33 3525.62  283.96 3525.07  309.19 3524.79  316.39 3524.89
  325.38 3525.74  366.31 3539.39  400.39 3551.65   406.5 3554.31  426.92 3564.03
#Mann= 3 , 0 , 0
       0    .075       0  283.96     .05       0  325.38    .075       0
#XS Ineff= 2 , 0
       0     184    3528               0
Permanent Ineff=
       F       F
Bank Sta=283.96,325.38
Exp/Cntr=0.3,0.1

Type RM Length L Ch R = 1 ,170964  ,429.32,422.41,347.27
BEGIN DESCRIPTION:
170886.0
END DESCRIPTION:
XS GIS Cut Line= 6
  963489.8174014  812301.6626401  963381.0397097  812355.4912619
  963331.6969771  812362.2200956  963182.5483312  812366.7049606
    963138.81296  812367.8264329  962982.9365045  812315.1203076
#Sta/Elev= 30
       0 3564.08    5.52 3563.76   15.81 3562.28   26.24 3560.06      41 3557.58
   66.54 3552.13   87.93 3548.12   93.06 3545.85  125.57 3534.37   132.5 3532.25
  153.03 3526.62  166.46 3524.49  226.13  3521.7  233.37 3520.94  241.53 3519.42
  256.71 3519.36  303.57 3517.63  322.82 3516.82  345.17 3517.24  356.08  3517.3
  365.09  3517.8  373.04 3517.72  388.15 3521.93  404.64 3524.74  425.41  3527.8
  453.63 3536.07  484.84 3543.05  495.39 3545.85  511.64 3549.09   528.7 3554.06
#Mann= 3 , 0 , 0
       0    .075       0  303.57     .05       0  345.17     .07       0
Bank Sta=303.57,345.17
Exp/Cntr=0.3,0.1

Type RM Length L Ch R = 1 ,170542  ,270.15,269.71,316.47
BEGIN DESCRIPTION:
170463.6
END DESCRIPTION:
XS GIS Cut Line= 6
  963346.2761169   811908.045324  963282.3552687  811943.9303891
  963212.8270589  811950.6592229  963141.0559046  811955.1451121
  963067.0428299  811967.4802831  962975.0861984  812024.6722976
#Sta/Elev= 30
       0 3547.52    5.77 3545.45   21.79 3538.15    34.4 3534.65   45.04 3531.02
   59.45 3525.55   70.47 3522.42   86.79 3518.21   94.47 3516.42  105.04 3514.22
  122.94 3511.26  157.32 3508.06  173.04 3505.87  193.18 3503.77  206.55 3503.12
  222.78 3504.26  261.68  3504.6  280.23 3505.73  303.08 3508.43  310.93 3508.94
  323.15 3514.02  333.75 3519.42  337.74  3521.3  344.49 3524.11  355.56 3529.61
  364.82 3533.06  373.58 3535.78  382.58 3537.33  391.91 3539.22  398.39 3540.17
#Mann= 3 , 0 , 0
       0     .08       0  193.18     .05       0  222.78     .07       0
Bank Sta=193.18,222.78
Exp/Cntr=0.3,0.1

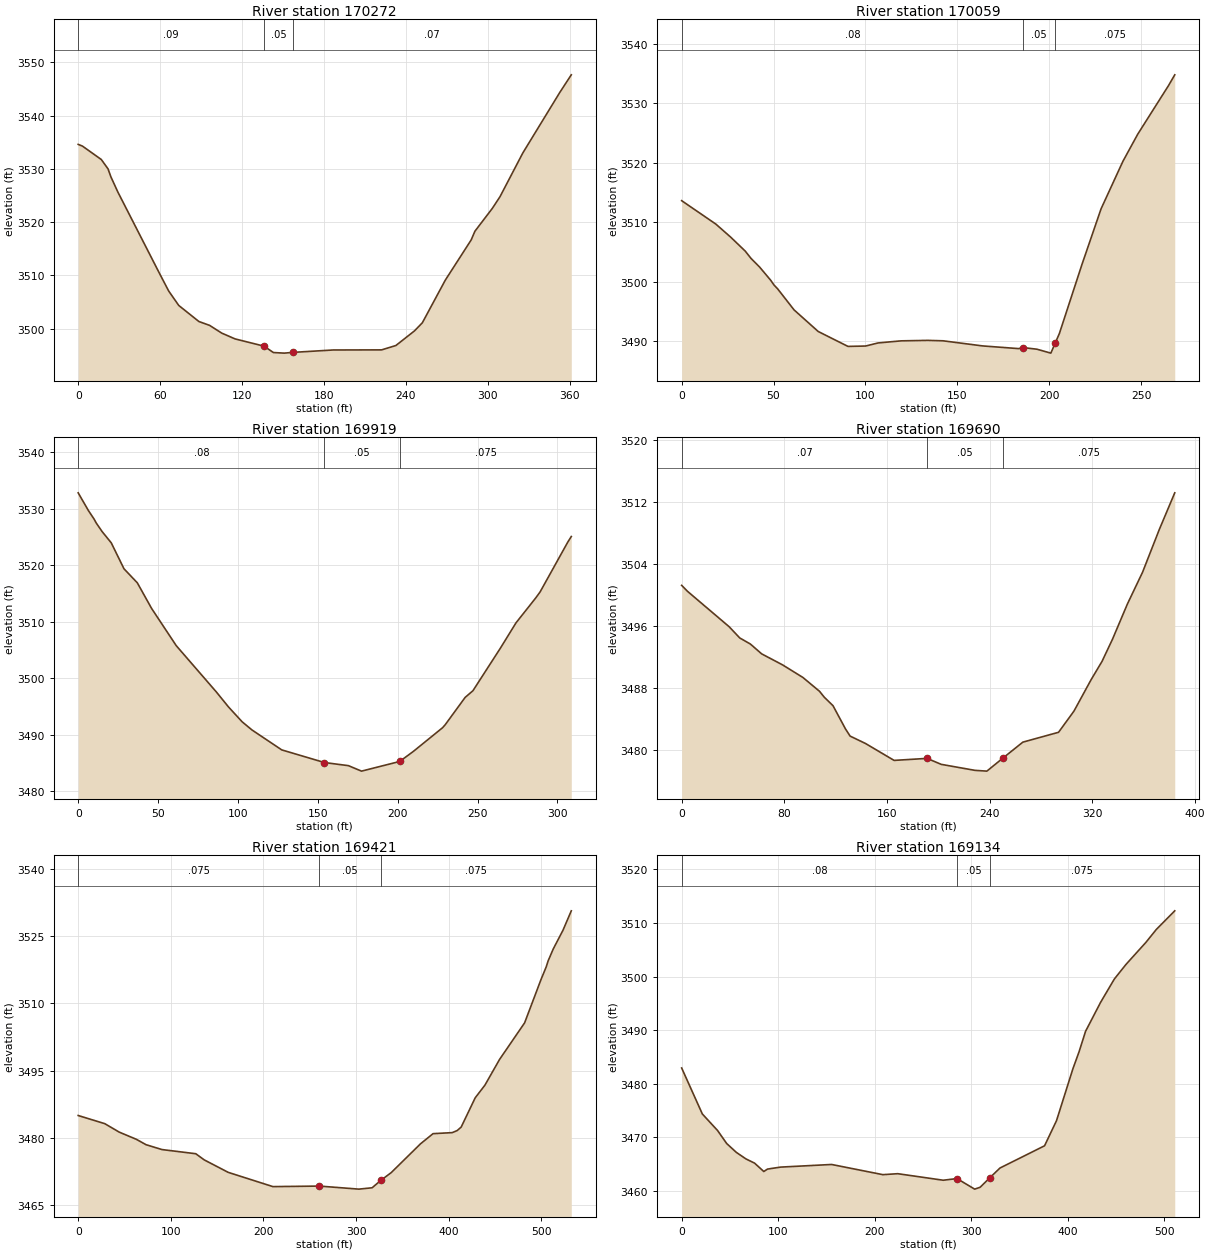
Type RM Length L Ch R = 1 ,170272  ,185.84,212.62,209.31
BEGIN DESCRIPTION:
170193.9
END DESCRIPTION:
XS GIS Cut Line= 6
  963278.9908518  811686.0040515  963169.0916878  811687.1255238
  963132.0851504  811688.2469961  963073.7706395  811692.7328852
  962963.8724996  811693.8543575  962919.0156562  811684.8825792
#Sta/Elev= 30
       0  3534.6    3.09 3534.28   16.92 3531.76   21.86    3530   23.93 3528.52
   29.02 3525.67   58.87 3510.72    66.3 3507.07   73.66 3504.37    88.4 3501.36
   96.21 3500.64  105.08 3499.19  114.85  3498.1  136.06 3496.74  142.93 3495.54
  150.86 3495.43  157.23 3495.57  186.79 3496.02  222.18 3496.04  232.64 3496.86
  246.17 3499.59     252 3501.12  268.85 3509.14  287.79 3516.68  290.47 3518.29
  303.25 3522.59  308.86 3524.78  325.61    3533  352.76 3544.39  361.07 3547.65
#Mann= 3 , 0 , 0
       0     .09       0  136.06     .05       0  157.23     .07       0
Bank Sta=136.06,157.23
Exp/Cntr=0.3,0.1

Type RM Length L Ch R = 1 ,170059  ,128.68,140.11,82.89
BEGIN DESCRIPTION:
169981.3
END DESCRIPTION:
XS GIS Cut Line= 6
  963247.5906517   811503.213285  963172.4561047  811496.4844513
  963106.2923118  811494.2415067  963054.7066346  811494.2415067
  962998.6360924  811483.0278079  962980.6935599  811483.0278079
#Sta/Elev= 30
       0 3513.62   18.59 3509.69   26.67  3507.5    34.6 3505.15   37.68 3503.95
    42.4 3502.48   48.45 3500.26    50.3 3499.44    52.2 3498.83   61.17 3495.28
   74.33 3491.65   90.51 3489.15  100.08 3489.21   106.9 3489.73  119.41 3490.08
   133.8 3490.16  142.22 3490.09  163.79 3489.23  183.28 3488.78  185.88 3488.95
  193.29 3488.68  200.92 3488.02  203.233489.659  205.57 3491.32  217.81 3502.87
  228.25 3512.25  240.16 3520.24  248.22 3524.79  264.97 3532.95  268.35 3534.75
#Mann= 3 , 0 , 0
       0     .08       0  185.88     .05       0  203.23    .075       0
Bank Sta=185.88,203.23
Exp/Cntr=0.3,0.1

Type RM Length L Ch R = 1 ,169919  ,226.59,228.63,166.82
BEGIN DESCRIPTION:
169841.2
END DESCRIPTION:
XS GIS Cut Line= 5
  963290.2045505  811375.3715885  963193.7630541  811370.8856993
  963127.5992612   811369.764227  963080.4994732  811372.0071716
  962990.7857864  811413.4995982
#Sta/Elev= 30
       0 3532.85    6.41  3529.7   10.08 3528.14   11.19 3527.55   15.02 3525.97
    20.7 3523.99   28.68 3519.39   37.01 3516.91   45.94 3512.38   61.38 3505.78
   86.48 3497.58   94.16  3494.9  102.64 3492.29  108.81 3490.84  127.45 3487.31
  154.18 3485.07  169.17 3484.52   177.4 3483.55  201.27 3485.26  209.87 3487.05
  228.09 3491.23  229.76 3491.76  242.24  3496.6  247.16  3497.8  264.39 3505.36
  274.11 3509.82  286.49 3514.24  289.16 3515.28   306.5 3524.11  308.72 3525.11
#Mann= 3 , 0 , 0
       0     .08       0  154.18     .05       0  201.27    .075       0
Bank Sta=154.18,201.27
Exp/Cntr=0.3,0.1

Type RM Length L Ch R = 1 ,169690  ,278.83,269.4,241.28
BEGIN DESCRIPTION:
169612.6
END DESCRIPTION:
XS GIS Cut Line= 6
  963247.5906517  811145.4800099  963139.9344323  811156.6947328
  963077.1350563   811161.180622   963024.428931  811183.6090437
  962991.9072587  811210.5223304   962914.529767  811293.5071835
#Sta/Elev= 30
       0 3501.25    4.64 3500.47   36.98 3495.93   45.27 3494.48   53.52  3493.7
   62.36 3492.43   78.57 3491.02   94.42  3489.4  107.38 3487.62  111.08 3486.86
  117.92 3485.76  127.57 3482.79  131.23 3481.85  143.19  3480.9  165.51 3478.72
  191.16 3478.98  202.27 3478.21  228.48 3477.44  237.77 3477.34  250.08 3478.99
   265.8 3481.07  293.63 3482.34  305.61 3485.06  318.99 3489.11  327.48 3491.46
  335.63 3494.31  347.37 3498.89  359.02 3502.92  372.21 3508.48  384.15 3513.16
#Mann= 3 , 0 , 0
       0     .07       0  191.16     .05       0  250.08    .075       0
Bank Sta=191.16,250.08
Exp/Cntr=0.3,0.1

Type RM Length L Ch R = 1 ,169421  ,282.16,287.15,338.73
BEGIN DESCRIPTION:
169343.2
END DESCRIPTION:
XS GIS Cut Line= 6
  963118.6274829  810922.3182892  962995.2716755  810939.1393494
  962865.1870344  810977.2673591  962795.6588247  811049.0385134
  962764.2596488  811099.5027183  962717.1598608  811201.5515763
#Sta/Elev= 30
       0    3485    28.7 3483.18   44.34 3481.29    62.9 3479.68   73.22 3478.49
   90.44  3477.4  126.96 3476.47  136.15 3475.09  162.03 3472.31  210.31 3469.13
  260.38 3469.25  303.07 3468.57  317.41 3468.87  326.663470.503     338 3472.25
  369.65 3478.68  383.21 3480.95  403.94 3481.18  409.31 3481.65  413.55 3482.41
  428.72 3488.95  439.14 3491.75  455.01 3497.51  482.08 3505.68  499.84 3515.38
  505.39 3518.16  507.48 3519.51  513.05 3522.19  523.52 3526.35  532.48 3530.68
#Mann= 3 , 0 , 0
       0    .075       0  260.38     .05       0  326.66    .075       0
Bank Sta=260.38,326.66
Exp/Cntr=0.3,0.1

Type RM Length L Ch R = 1 ,169134  ,221.5,222.44,237.82
BEGIN DESCRIPTION:
169056.0
END DESCRIPTION:
XS GIS Cut Line= 6
  962945.9289429  810641.9635298  962805.7520753  810735.0416336
  962728.3745837  810775.4125878  962637.5394246  810797.8410096
  962592.6825811  810830.3616577  962538.8539593  810921.1968169
#Sta/Elev= 30
       0 3482.93   21.42 3474.35   37.21 3471.26   46.66 3468.83   56.64 3467.18
   66.67 3465.95   75.48 3465.18   85.09 3463.61   88.93 3464.06  102.51 3464.43
  155.38 3464.92  208.42 3463.02  223.85  3463.2     271 3461.98  285.23 3462.29
  303.53 3460.32  309.15 3460.66  319.42 3462.47  329.78 3464.26  375.96 3468.41
  388.34  3473.1  405.24 3482.74   411.7 3485.95   418.4 3489.76  433.97 3495.17
  448.28 3499.54  460.32 3502.26  480.84 3506.35  491.67 3508.77  510.83 3512.26
#Mann= 3 , 0 , 0
       0     .08       0  285.23     .05       0  319.42    .075       0
Bank Sta=285.23,319.42
Exp/Cntr=0.5,0.3

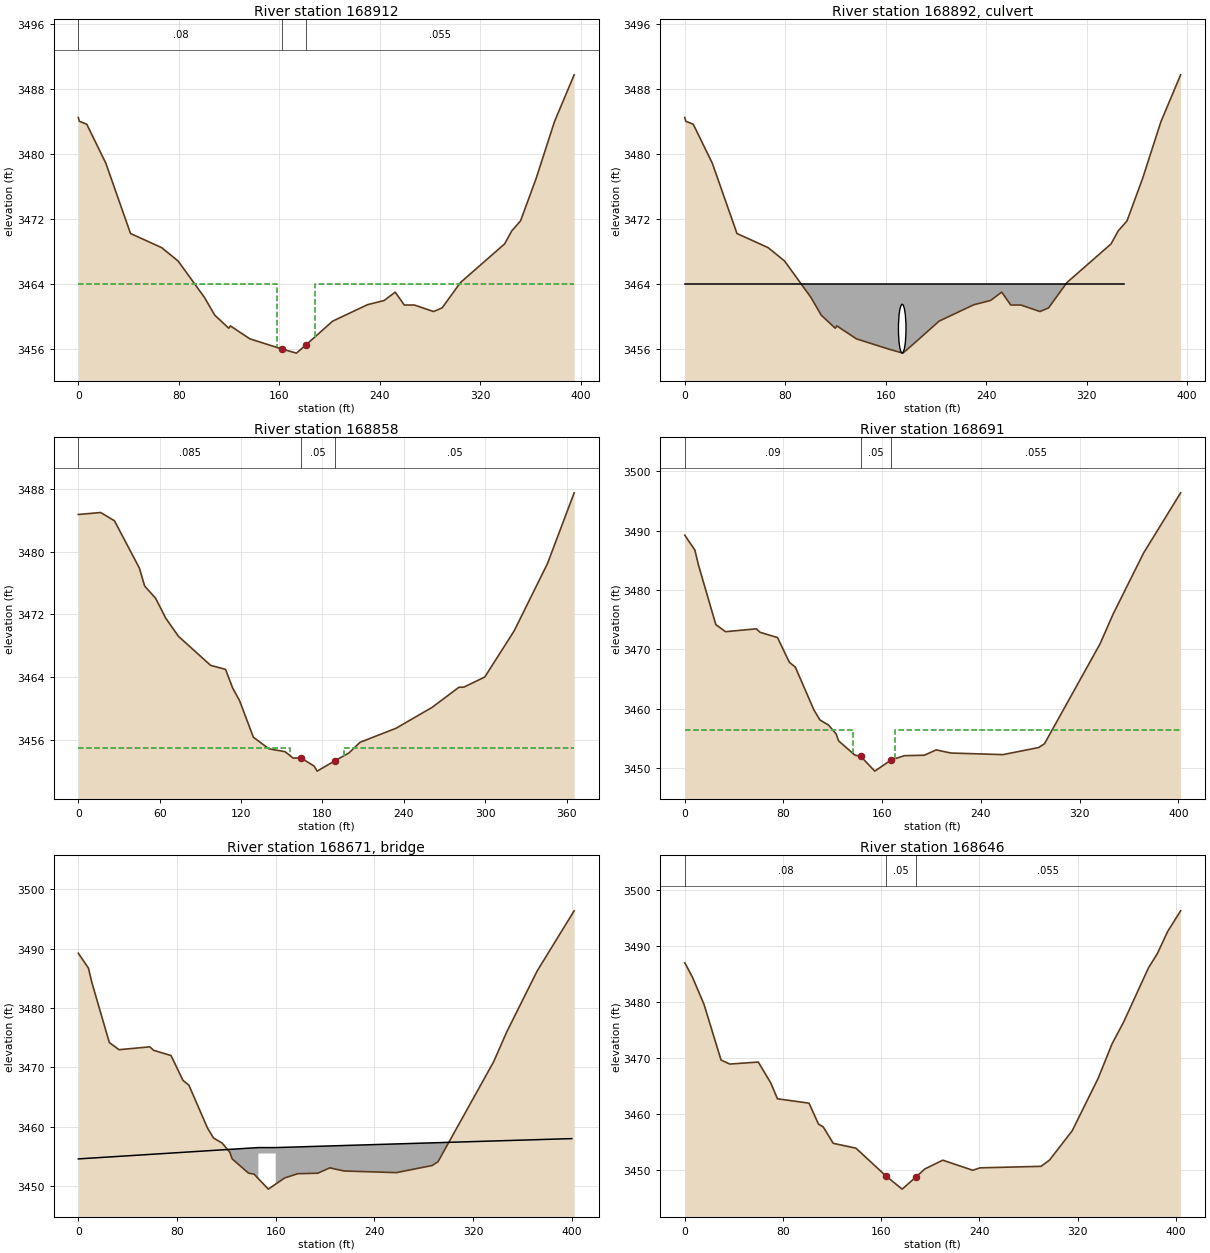
Type RM Length L Ch R = 1 ,168912  ,86.71,53.06,37.97
BEGIN DESCRIPTION:
168833.6
END DESCRIPTION:
XS GIS Cut Line= 6
  962813.6023814  810452.4439296  962730.6165041  810534.3073104
  962672.3030173  810572.4353201  962625.2032293  810594.8637418
  962531.0046775  810590.3778526  962474.9331111  810564.5860382
#Sta/Elev= 30
       0  3484.5     .76 3484.05    6.72 3483.68   21.91 3478.87   41.57  3470.2
   66.34 3468.46   79.47 3466.81  100.39 3462.33  108.65 3460.13  119.81 3458.52
  121.11 3458.81  136.64 3457.21  162.48 3455.94  173.69 3455.45   181.4 3456.48
   202.5 3459.39  230.22 3461.42  243.52 3461.94  252.36 3462.97  259.59 3461.38
  267.65 3461.38  282.88 3460.58  289.71 3461.03  304.35 3464.16  339.48 3468.92
  345.19 3470.53  352.17 3471.76  364.62 3477.01  379.17 3483.99  394.86 3489.77
#Mann= 3 , 0 , 0
       0     .08       0  162.48     .05       0   181.4    .055       0
#XS Ineff= 2 , 0
       0  158.14 3463.97  188.14       0 3463.97
Permanent Ineff=
       F       F
Bank Sta=162.48,181.4
Exp/Cntr=0.5,0.3

Type RM Length L Ch R = 2 ,168892  ,,,
Node Photo=H:\PROJ\06-0741\CE\GIS\DATA\FRENCH_BROAD_RIVER\SHAPEFILES\survey_data\photos\FBSTR_1281.JPG
BEGIN DESCRIPTION:
168806.6  FBSTR_1281
END DESCRIPTION:
Bridge Culvert--1,0,-1,-1, 0
Deck Dist Width WeirC Skew NumUp NumDn MinLoCord MaxHiCord MaxSubmerge Is_Ogee
15,15,3,0, 5, 5, , , 0.95, 0, 1,1,,
       0  158.14  173.14  188.14     350
 3463.97 3463.97 3463.97 3463.97 3463.97
                                        
       0  160.93  175.93  190.93     350
 3463.97 3463.97 3463.97 3463.97 3463.97
                                        
BR Coef=-1 , 0 , 0 ,, 0 ,,,0.8,-1,,0,
WSPro=,,,, 1 ,,,, 0 ,,,, 0 ,,,,-1 ,-1 ,-1 , 0 , 0 , 0 , 0 , 0
Culvert=1,6,,20,0.024,0.9,1,2,3,3455.47,173.14,3452.08,176,Culvert #1  , 0 ,13
Culvert Bottom n=0.024
BC Design=,, 0 ,, 0 ,,,,,,

Type RM Length L Ch R = 1 ,168858  ,145.67,167.54,99.71
BEGIN DESCRIPTION:
168780.5
END DESCRIPTION:
XS GIS Cut Line= 6
  962779.9592367  810376.1868861  962670.0600728   810513.000361
  962630.8105908   810536.550255  962556.7975161  810555.6142599
   962525.397316  810551.1283707  962493.9971159  810535.4287827
#Sta/Elev= 30
       0 3484.74   16.43 3484.99   26.64 3483.94   44.98 3477.92   48.91 3475.62
   57.01 3474.06   64.44 3471.53   73.84 3469.21   97.56 3465.51  108.56    3465
  113.78 3462.63   118.9 3461.01  129.08 3456.35  140.62 3454.87  152.41 3454.51
  158.47 3453.69  164.25 3453.71  173.87 3452.67  176.11 3452.03  189.44 3453.37
  199.48 3454.34  207.71  3455.7  234.36  3457.5  260.81 3460.15  280.67 3462.72
   284.2 3462.73   299.7 3464.02  321.44 3469.92  345.94 3478.48  365.62  3487.5
#Mann= 3 , 0 , 0
       0    .085       0  164.25     .05       0  189.44     .05       0
#XS Ineff= 2 , 0
       0     156    3455     196       0    3455
Permanent Ineff=
       F       F
Bank Sta=164.25,189.44
Exp/Cntr=0.5,0.3

Type RM Length L Ch R = 1 ,168691  ,51.15,44.96,44.3
BEGIN DESCRIPTION:
168613.0
END DESCRIPTION:
XS GIS Cut Line= 6
  962753.0449258   810257.316968  962674.5459619  810290.9590885
  962662.2107909  810305.5382283  962631.9320631  810401.9797247
  962576.9829932  810449.0795128  962458.1120508  810478.2367682
#Sta/Elev= 30
       0 3489.23    8.17 3486.73   11.05 3484.24   25.14 3474.18   33.02 3472.98
   57.98 3473.46   60.96 3472.88   75.14 3471.99   84.82 3467.81    89.6 3467.01
  104.65 3459.81  109.53 3458.11  116.54 3457.25  122.71 3455.74  124.71 3454.58
  137.88 3452.19  142.48 3452.01  154.01 3449.49  167.32 3451.38  177.98 3452.09
  194.13 3452.17  203.84 3453.07  215.63 3452.54  257.88 3452.27  286.77 3453.46
  291.56  3454.1  336.61 3470.93  347.29 3475.98  371.93 3486.24  401.92 3496.37
#Mann= 3 , 0 , 0
       0     .09       0  142.48     .05       0  167.32    .055       0
#XS Ineff= 2 , 0
       0     136 3456.49     170       0 3456.49
Permanent Ineff=
       F       F
Bank Sta=142.48,167.32
Exp/Cntr=0.5,0.3

Type RM Length L Ch R = 3 ,168671  ,,,
Node Photo=H:\PROJ\06-0741\CE\GIS\DATA\FRENCH_BROAD_RIVER\SHAPEFILES\survey_data\photos\FBSTR_1280.JPG
BEGIN DESCRIPTION:
168592.8  FBSTR_1280
END DESCRIPTION:
Bridge Culvert--1,0,-1,-1, 0
Deck Dist Width WeirC Skew NumUp NumDn MinLoCord MaxHiCord MaxSubmerge Is_Ogee
10.5,12,3,0, 7, 7, , , 0.95, 0, 1,1,,
       0     146     146     153     160     160     400
 3454.58 3456.49 3456.49 3456.49 3456.49 3456.49    3458
                 3455.49 3455.49 3455.49
       0  170.01  170.01  177.01  184.01  184.01     400
 3454.58 3456.49 3456.49 3456.49 3456.49 3456.49    3458
                 3455.49 3455.49 3455.49
BR Coef=-1 , 0 , 0 ,, 0 ,,,0.8,0,,0,
WSPro=,,,, 1 ,,,, 0 ,,,, 0 ,,,,-1 ,-1 ,-1 , 0 , 0 , 0 , 0 , 0
BC Design=,, 0 ,, 0 ,,,,,,

Type RM Length L Ch R = 1 ,168646  ,170.99,254.73,342.24
BEGIN DESCRIPTION:
168568.0
END DESCRIPTION:
XS GIS Cut Line= 6
  962746.3171163  810228.1597125  962662.2107909  810240.4959077
  962640.9038414  810255.0740234  962617.3539474  810348.1521271
  962583.7108028  810396.3723633  962453.6261617  810440.1077344
#Sta/Elev= 30
       0 3486.93    6.14 3484.41   15.64 3479.52   29.53 3469.57   36.66 3468.85
   59.84 3469.21      70 3465.49   75.48 3462.65  101.17 3461.87  108.92 3458.12
  112.67 3457.65   120.9  3454.7  139.41 3453.83  164.24 3448.79  177.01 3446.52
  188.193448.662  195.42 3450.11  210.07 3451.69  234.54 3449.89  240.44 3450.32
  290.09 3450.59  297.03  3451.7  315.52 3456.94  336.63 3466.29  347.98 3472.46
  357.45 3476.37  377.71 3486.06  384.93 3488.59  393.18 3492.49  403.83 3496.21
#Mann= 3 , 0 , 0
       0     .08       0  164.24     .05       0  188.19    .055       0
#XS Ineff= 2 , 0
       0  155.01    3450  199.01       0    3450
Permanent Ineff=
       F       F
Bank Sta=164.24,188.19
Exp/Cntr=0.5,0.3