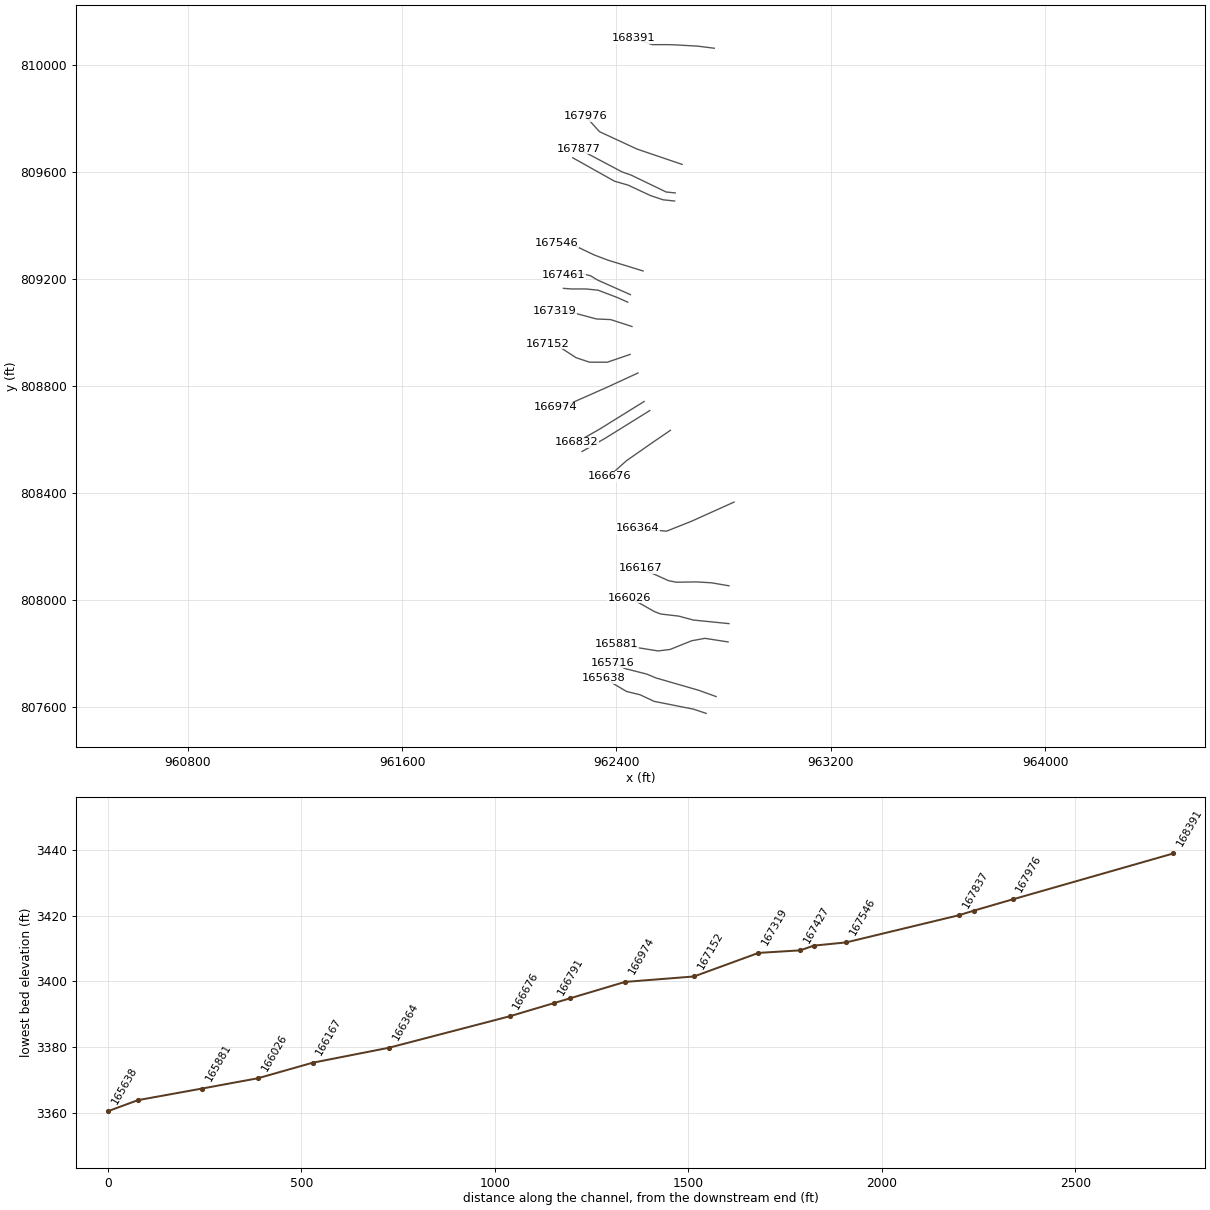
HEC-RAS study lds_big_laurel_crk.prj: lds_big_laurel_crk

--- lds_big_laurel_crk.g20 (geometry) --- (continued)

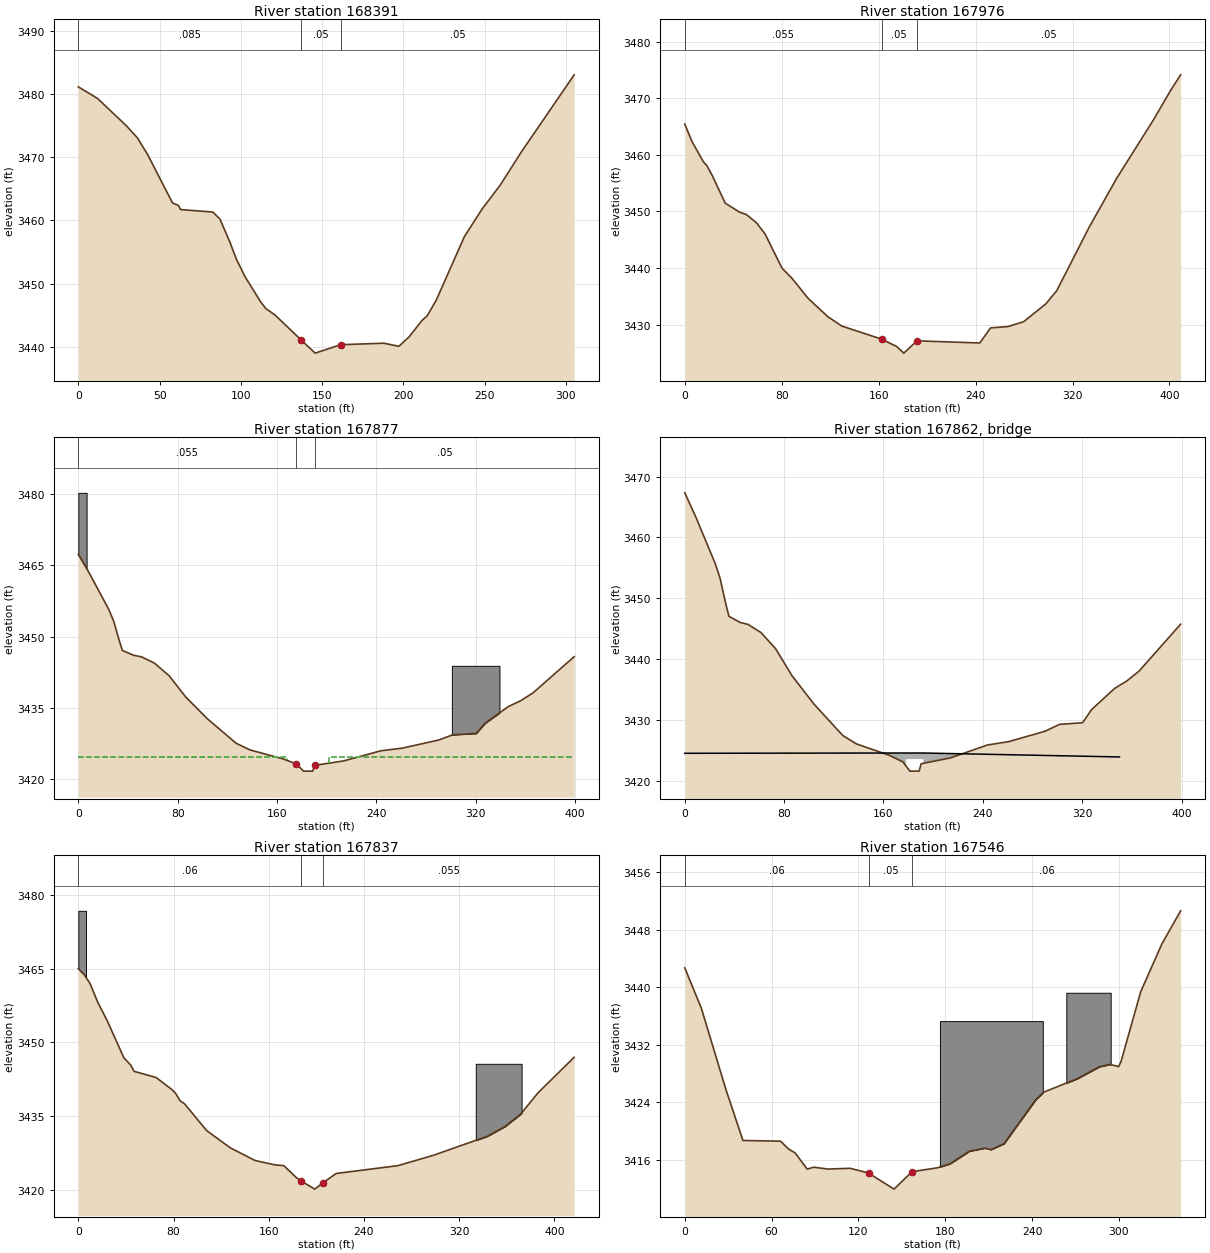
Type RM Length L Ch R = 1 ,168391  ,431.81,415.15,383.98
BEGIN DESCRIPTION:
168313.3
END DESCRIPTION:
XS GIS Cut Line= 6
  962765.3811211  810062.1900063  962703.7032174  810070.0403124
   962624.081757  810074.5251774  962594.9255257  810075.6466497
  962534.3690943  810075.6466497  962464.8408846  810099.1965437
#Sta/Elev= 30
       0 3481.13   11.83 3479.29   29.72 3474.93   36.37 3473.05   42.72 3470.38
   57.96 3462.76   61.58 3462.36   62.97 3461.71   82.74 3461.32   87.11 3460.22
   93.28 3456.55   97.21 3453.89  102.64 3451.06  112.37 3447.04  115.41 3446.04
  120.92 3445.05     137  3441.1  145.71    3439  161.38 3440.33  187.98 3440.57
  197.21 3440.08  203.55 3441.58  211.41 3444.16  214.64  3444.9  220.26  3447.4
  237.49 3457.41  248.41 3461.79  259.58 3465.58  272.41 3470.76  305.07 3483.03
#Mann= 3 , 0 , 0
       0    .085       0     137     .05       0  161.38     .05       0
Bank Sta=137,161.38
Exp/Cntr=0.3,0.1

Type RM Length L Ch R = 1 ,167976  ,111.19,99.47,94.98
BEGIN DESCRIPTION:
167898.1
END DESCRIPTION:
XS GIS Cut Line= 4
  962645.3887064  809628.2007118  962477.1760557  809685.3937505
  962336.9991881   809750.436071  962285.4135109  809807.6280855
#Sta/Elev= 30
       0 3465.41    6.14 3462.26   15.44 3458.74   18.24  3458.1   22.71 3456.33
   33.38 3451.47    45.3 3449.87   50.76 3449.47   59.18 3448.01   66.24 3446.04
   80.24    3440   88.53 3438.19   101.7 3434.69  117.92 3431.45  129.64 3429.77
  162.36 3427.48  174.89 3426.17  180.76    3425  191.64 3427.17  243.46 3426.79
  252.36 3429.45  266.65 3429.68  279.62 3430.54  297.95 3433.69  307.01 3436.03
  333.71 3447.21  356.37 3455.83  386.74 3466.15  400.94 3471.36  409.22 3474.12
#Mann= 3 , 0 , 0
       0    .055       0  162.36     .05       0  191.64     .05       0
Bank Sta=162.36,191.64
Exp/Cntr=0.5,0.3

Type RM Length L Ch R = 1 ,167877  ,37.74,39.74,40.65
BEGIN DESCRIPTION:
167798.7
END DESCRIPTION:
XS GIS Cut Line= 5
   962619.596892  809521.6659647  962585.9537474  809525.0303816
  962455.8691062  809587.8297576  962421.1055135  809600.1659528
     962258.4992  809686.5141986
#Sta/Elev= 30
       0 3467.34    9.25 3463.19    24.5 3455.72   28.46 3453.26   32.74 3449.32
   35.51 3447.06   44.55 3446.04    50.9 3445.72   61.37 3444.37   73.04 3441.75
   86.39 3437.27  103.85 3432.66  127.13 3427.47  138.29 3426.07  164.66  3424.2
  175.67 3423.11  181.28  3421.6  188.71  3421.6  190.28 3422.81   213.9 3423.77
  243.61 3425.89  260.87 3426.45  290.05 3428.15  301.68 3429.28  320.33 3429.56
  327.53 3431.71  346.21 3435.21  356.08 3436.44  365.98 3438.08  399.26 3445.75
#Mann= 3 , 0 , 0
       0    .055       0  175.67     .05       0  190.28     .05       0
#XS Ineff= 2 , 0
       0  168.19 3424.58  202.19       0 3424.58
Permanent Ineff=
       F       F
#Block Obstruct= 2 ,-1
       0    6.663480.324  300.77  339.113443.827
Bank Sta=175.67,190.28
Exp/Cntr=0.5,0.3

Type RM Length L Ch R = 3 ,167862  ,,,
Node Photo=H:\PROJ\06-0741\CE\GIS\DATA\FRENCH_BROAD_RIVER\SHAPEFILES\survey_data\photos\FBSTR_1797.JPG
BEGIN DESCRIPTION:
167777.7  FBSTR_1797
END DESCRIPTION:
Bridge Culvert--1,0,-1,-1, 0
Deck Dist Width WeirC Skew NumUp NumDn MinLoCord MaxHiCord MaxSubmerge Is_Ogee
15,11,2.6,0, 7, 7, , , 0.95, 0, 1,1,,
       0  178.19  178.19  185.19  192.19  192.19     350
 3424.53 3424.58 3424.58 3424.58 3424.58 3424.58 3423.93
                 3423.58 3423.58 3423.58
       0  191.02  191.02  198.02  205.02  205.02     350
 3424.53 3424.58 3424.58 3424.58 3424.58 3424.58 3423.93
                 3423.58 3423.58 3423.58
BR Coef=-1 , 0 , 0 ,, 0 ,,,0.8,0,,0,
WSPro=,,,, 1 ,,,, 0 ,,,, 0 ,,,,-1 ,-1 ,-1 , 0 , 0 , 0 , 0 , 0
BC Design=,, 0 ,, 0 ,,,,,,

Type RM Length L Ch R = 1 ,167837  ,278.18,291.2,328.19
BEGIN DESCRIPTION:
167758.9
END DESCRIPTION:
XS GIS Cut Line= 6
  962617.3539474  809491.3882611  962574.7400486  809495.8731261
  962527.6402606  809511.5737382  962443.5339352  809550.8232202
  962393.0697303  809565.4013358  962237.1922506  809652.8720781
#Sta/Elev= 30
       0 3465.02    5.14 3463.73    9.83    3462   16.28 3458.21   24.47 3454.33
   38.25 3446.89   44.14 3445.36   46.79 3444.13   65.36 3442.87   78.41 3440.46
   81.67 3439.68   85.46 3438.15   89.23 3437.52  107.88 3432.06  127.84 3428.54
  148.48 3425.99  165.25 3425.09  172.64 3424.94  183.43 3422.45  187.14 3421.82
  198.64 3420.16  205.85  3421.5  216.71 3423.35  268.39 3424.93  298.56 3427.06
  343.71 3430.92   358.5 3432.91   371.7 3435.43  386.41  3439.8   416.6 3446.98
#Mann= 3 , 0 , 0
       0     .06       0  187.14     .05       0  205.85    .055       0
#XS Ineff= 2 , 0
       0  181.02  3421.6  215.02       0 3421.33
Permanent Ineff=
       F       F
#Block Obstruct= 2 ,-1
       0    6.443476.787  333.92  372.443445.664
Bank Sta=187.14,205.85
Exp/Cntr=0.5,0.3

Type RM Length L Ch R = 1 ,167546  ,92.81,84.24,112.69
BEGIN DESCRIPTION:
167467.7
END DESCRIPTION:
XS GIS Cut Line= 6
  962499.6044774  809230.0975066   962368.398364  809270.4684608
  962317.9351832  809289.5324657   962242.799612  809325.4175307
  962208.0360193  809333.2678368  962175.5143469  809335.5107814
#Sta/Elev= 30
       0 3442.66   11.42 3437.06   28.38 3425.77   40.19 3418.65   66.23 3418.55
   71.53 3417.49   76.24 3416.92   84.64 3414.66   89.09 3414.93   98.96 3414.67
  114.27 3414.78  127.01 3414.12  144.61 3411.88  157.14 3414.31  174.43 3414.84
  183.32 3415.41  196.59 3417.15  207.49 3417.59  211.55 3417.38  220.56 3418.19
  242.53 3424.32  247.96 3425.36  271.26 3427.24  286.54 3428.91  293.85 3429.23
  299.93 3428.93  301.58 3429.66  315.15 3439.35  329.71 3445.97  342.72  3450.6
#Mann= 3 , 0 , 0
       0     .06       0  127.01     .05       0  157.14     .06       0
#Block Obstruct= 2 ,-1
  263.71  294.373439.205  176.34  247.453435.259
Bank Sta=127.01,157.14
Exp/Cntr=0.5,0.3

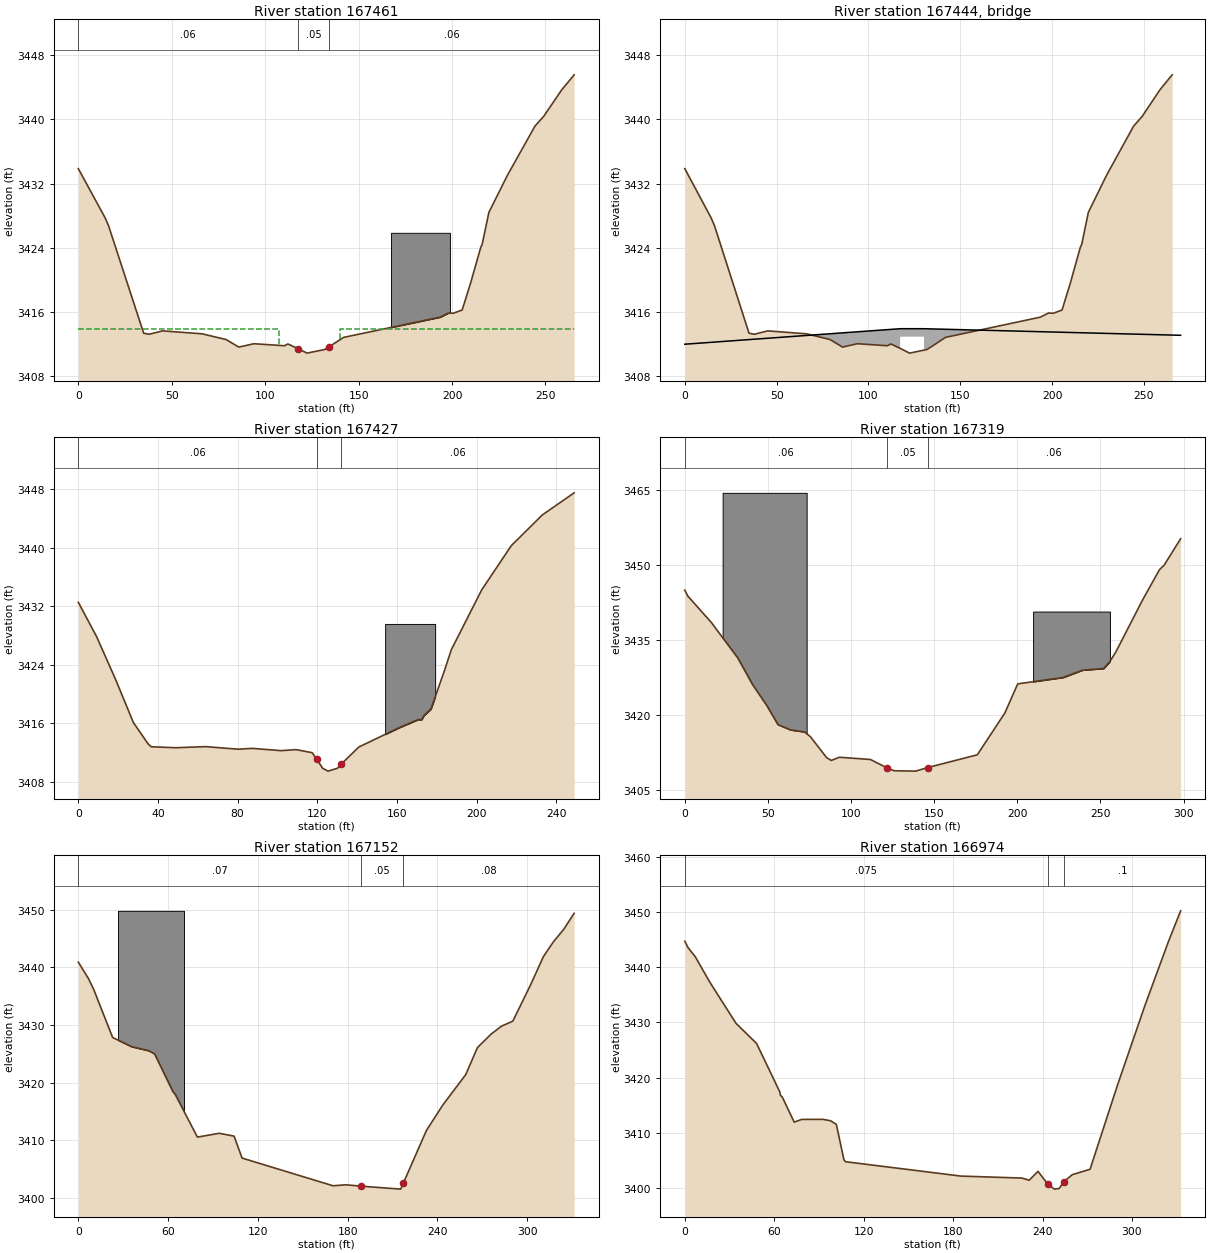
Type RM Length L Ch R = 1 ,167461  ,30.09,34.36,57.06
BEGIN DESCRIPTION:
167383.5
END DESCRIPTION:
XS GIS Cut Line= 5
  962452.5046894   809141.505292  962331.3918266  809195.3328896
  962303.3560434   809212.154974  962267.4709783  809221.1257282
  962204.6716024  809214.3979186
#Sta/Elev= 30
       0 3433.86    14.3 3427.75   16.15 3426.77   34.97 3413.37    37.9 3413.24
   45.14 3413.66   66.37 3413.29    79.1 3412.58   85.91 3411.64   93.98 3412.06
  110.34 3411.81  112.19 3412.03  117.59 3411.45   122.4 3410.89  131.87 3411.34
  134.02 3411.65  141.99 3412.85  193.63 3415.37  198.05 3415.88  200.65 3415.85
  205.44 3416.26  210.03 3419.68  215.45 3424.11  216.13 3424.41  219.74 3428.41
  229.73 3433.06  244.42 3439.16  249.05 3440.36  258.78 3443.69  265.38 3445.54
#Mann= 3 , 0 , 0
       0     .06       0  117.59     .05       0  134.02     .06       0
#XS Ineff= 2 , 0
       0  107.28 3413.93  140.28       0 3413.93
Permanent Ineff=
       F       F
#Block Obstruct= 1 ,-1
  167.38  198.883425.873
Bank Sta=117.59,134.02
Exp/Cntr=0.5,0.3

Type RM Length L Ch R = 3 ,167444  ,,,
Node Photo=H:\PROJ\06-0741\CE\GIS\DATA\FRENCH_BROAD_RIVER\SHAPEFILES\survey_data\photos\FBSTR_1796.JPG
BEGIN DESCRIPTION:
167361.5  FBSTR_1796
END DESCRIPTION:
Bridge Culvert--1,0,-1,-1, 0
Deck Dist Width WeirC Skew NumUp NumDn MinLoCord MaxHiCord MaxSubmerge Is_Ogee
10.5,14,2.6,0, 6, 7, , , 0.95, 0, 1,1,,
       0  117.28  117.28  123.28  130.28     270
    3412 3413.93 3413.93 3413.93 3413.93 3413.11
                 3412.93 3412.93 3412.93
       0  119.08  119.08  126.08  132.08  132.08     270
    3412 3413.93 3413.93 3413.93 3413.93 3413.93 3413.11
                 3412.93 3412.93 3412.93
BR Coef=-1 , 0 , 0 ,, 0 ,,,0.8,0,,0,
WSPro=,,,, 1 ,,,, 0 ,,,, 0 ,,,,-1 ,-1 ,-1 , 0 , 0 , 0 , 0 , 0
BC Design=,, 0 ,, 0 ,,,,,,

Type RM Length L Ch R = 1 ,167427  ,86.93,107.97,93.51
BEGIN DESCRIPTION:
167349.1
END DESCRIPTION:
XS GIS Cut Line= 6
  962442.4124629  809113.4695088  962402.0415086  809131.4120414
  962331.3918266  809158.3263523  962286.5349832  809162.8122414
  962232.7073856  809162.8122414  962202.4286578   809165.055186
#Sta/Elev= 30
       0 3432.54    9.19 3427.84   18.77 3421.96   27.68 3416.09   35.04 3413.19
   36.62 3412.79    48.9 3412.66    63.9 3412.81   80.26 3412.46   87.43 3412.57
  101.81 3412.26  109.37  3412.4  117.45 3411.98  119.78 3411.07  122.73 3409.85
  125.41 3409.46  130.22 3409.86  132.18 3410.45  140.87 3412.75  161.19 3415.41
  170.73 3416.51  172.43 3416.49  173.59 3417.07  177.09 3417.94  184.02 3423.29
  187.32 3426.04  202.57 3434.22  217.48 3440.29  233.08 3444.49  249.05 3447.51
#Mann= 3 , 0 , 0
       0     .06       0  119.78     .05       0  132.18     .06       0
#XS Ineff= 2 , 0
       0  104.08 3411.34  147.08       0 3410.42
Permanent Ineff=
       F       F
#Block Obstruct= 1 ,-1
  154.11  179.233429.587
Bank Sta=119.78,132.18
Exp/Cntr=0.5,0.3

Type RM Length L Ch R = 1 ,167319  ,152.22,166.63,140.45
BEGIN DESCRIPTION:
167241.1
END DESCRIPTION:
XS GIS Cut Line= 6
  962458.1120508  809022.6343497  962378.4916146  809048.4271883
  962325.7844651  809050.6701329  962262.9850892  809067.4911931
  962208.0360193  809079.8273883   962167.665065  809082.0703329
#Sta/Elev= 30
       0 3444.91    1.81 3443.74   16.07  3438.4   31.83 3431.35   40.78 3425.99
   49.27 3421.83   56.03 3417.99   63.69 3416.92   72.09 3416.53   75.63 3415.54
   85.28 3411.39   88.08 3410.82      93 3411.46  111.63 3411.01  121.82  3409.3
  125.93 3408.75  138.88 3408.68  146.03 3409.39  175.94 3411.95  192.45 3420.29
  200.24 3426.15  227.53 3427.43  239.14 3428.89  251.84 3429.22  255.71 3430.64
  259.26 3432.54  275.15 3442.84  285.52 3449.03  288.28 3449.91  298.21  3455.2
#Mann= 3 , 0 , 0
       0     .06       0  121.82     .05       0  146.03     .06       0
#Block Obstruct= 2 ,-1
   22.75   73.293464.401  209.48  255.693440.632
Bank Sta=121.82,146.03
Exp/Cntr=0.3,0.1

Type RM Length L Ch R = 1 ,167152  ,84.54,178.58,225.44
BEGIN DESCRIPTION:
167074.5
END DESCRIPTION:
XS GIS Cut Line= 6
  962451.3832171  808918.3425472  962366.1554194  808889.1863159
  962299.9926507  808889.1863159  962249.5284458  808906.0073761
  962178.8787638  808951.9856918  962141.8722264  808958.7135014
#Sta/Elev= 30
       0 3440.89    6.79 3438.02   10.32 3436.12   22.93 3427.81    35.5 3426.23
   47.13 3425.51   50.96 3424.96   63.19 3418.42   64.71 3417.95   79.58 3410.53
   94.19 3411.19  104.11 3410.69  109.42 3406.89  170.23 3402.08   178.7 3402.25
  188.853402.019  215.43  3401.5  217.313402.596  232.62 3411.67  243.75 3416.15
  258.93 3421.38  266.71 3426.05   275.7 3428.36  282.74 3429.77  290.37 3430.64
  302.48 3437.07  310.82 3441.85  317.48  3444.4  324.43 3446.59  331.37 3449.36
#Mann= 3 , 0 , 0
       0     .07       0  188.85     .05       0  217.31     .08       0
#Block Obstruct= 1 ,-1
   26.52   70.643449.788
Bank Sta=188.85,217.31
Exp/Cntr=0.3,0.1

Type RM Length L Ch R = 1 ,166974  ,115.56,141.8,144.12
BEGIN DESCRIPTION:
166895.9
END DESCRIPTION:
XS GIS Cut Line= 4
  962480.5404726  808848.8153616   962363.913499  808794.9867398
  962217.0067734  808729.9444193  962174.3928746  808720.9736651
#Sta/Elev= 30
       0  3444.7    2.12 3443.58    7.07 3441.88   16.82 3437.28   34.36 3429.84
   48.17  3426.2   63.77 3417.42   64.18  3416.8   65.35 3416.53    73.4 3411.96
   78.44 3412.45   92.68 3412.46   97.83 3412.21  101.69 3411.55  106.76 3405.14
  107.88 3404.79  185.26 3402.19  226.26 3401.83  231.03 3401.44  236.97 3403.05
  243.36  3400.8  248.03 3399.83   251.2 3399.95  254.37 3401.21  260.01 3402.45
  271.89 3403.42  290.52 3418.83  308.76 3433.11   324.4 3444.58  332.66 3450.21
#Mann= 3 , 0 , 0
       0    .075       0  243.36     .05       0  254.37      .1       0
Bank Sta=243.36,254.37
Exp/Cntr=0.3,0.1

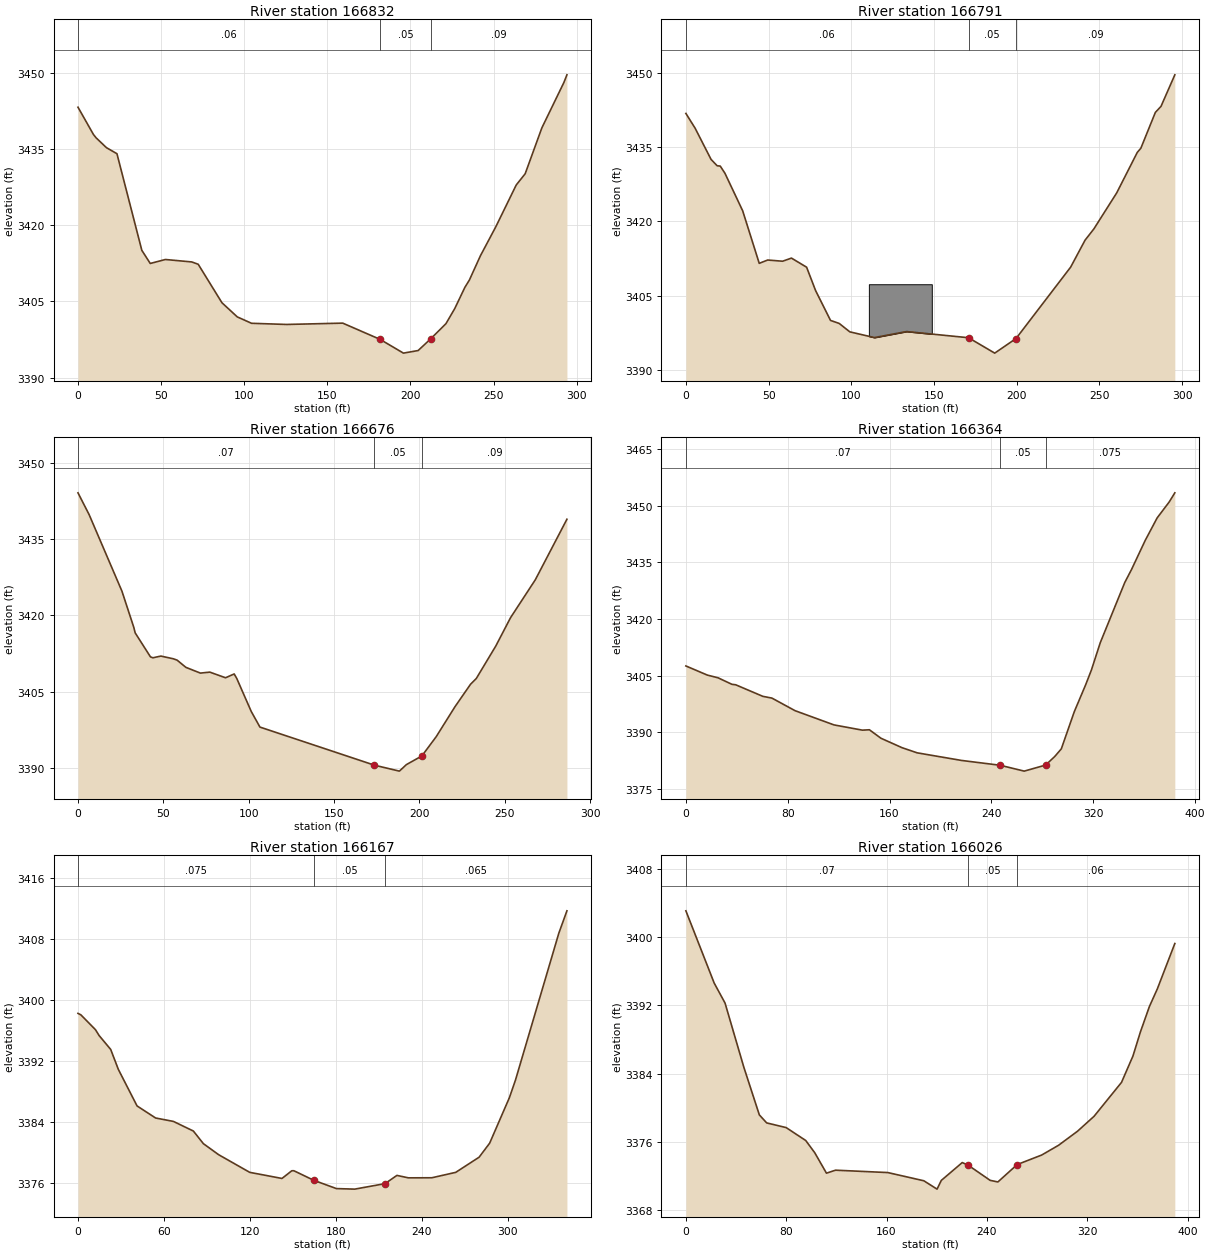
Type RM Length L Ch R = 1 ,166832  ,40.16,41.49,41.85
BEGIN DESCRIPTION:
166754.1
END DESCRIPTION:
XS GIS Cut Line= 3
  962503.6253908  808742.4444826  962337.9690824  808639.4697699
  962251.9403794  808590.3103647
#Sta/Elev= 30
       0 3443.22    9.29 3437.86   10.88  3437.2   17.13 3435.26   23.44 3434.07
   38.41 3415.06   43.47 3412.48    52.6 3413.26   68.44 3412.78   72.33 3412.32
   86.61 3404.75   95.82 3401.97  104.41 3400.71  125.43 3400.48  159.28 3400.74
  181.72 3397.55  195.79 3394.84  204.64 3395.35  212.14 3397.64  221.35 3400.63
  226.68 3403.62  232.77 3407.79  235.46 3409.22  242.11    3414  251.44 3419.75
  263.63 3427.91  269.03 3430.13  279.07 3439.16  292.33 3448.09  294.14 3449.59
#Mann= 3 , 0 , 0
       0     .06       0  181.72     .05       0  212.14     .09       0
Bank Sta=181.72,212.14
Exp/Cntr=0.3,0.1

Type RM Length L Ch R = 1 ,166791  ,107.57,114.49,125.13
BEGIN DESCRIPTION:
166712.6
END DESCRIPTION:
XS GIS Cut Line= 3
  962524.7418436  808708.4725776  962358.4566913  808605.1066298
  962271.7868544  808555.5805698
#Sta/Elev= 30
       0 3441.81    5.57 3438.83   15.22 3432.52   18.89 3431.24   20.77 3431.17
   23.63 3429.71   34.33 3422.14   44.35 3411.52   49.44 3412.19   58.47 3411.95
   63.82 3412.58   72.99 3410.74   78.42 3406.02   87.44 3399.99   92.69 3399.38
    99.1 3397.68  114.01 3396.52  133.43 3397.74   170.9 3396.49  186.73 3393.38
  199.61 3396.33  232.62 3410.75  241.36 3416.21  246.66 3418.47  260.47 3425.75
  272.91 3433.93  275.08 3434.78  283.84 3442.01  287.28 3443.25  295.62 3449.61
#Mann= 3 , 0 , 0
       0     .06       0   170.9     .05       0  199.61     .09       0
#Block Obstruct= 1 ,-1
  110.62  148.683407.298
Bank Sta=170.9,199.61
Exp/Cntr=0.3,0.1

Type RM Length L Ch R = 1 ,166676  ,328.78,312.15,275.38
BEGIN DESCRIPTION:
166598.1
END DESCRIPTION:
XS GIS Cut Line= 4
  962601.6533353  808634.6243951  962534.3690943  808588.6460794
  962437.9265737  808521.3608142  962372.8842532  808463.0473274
#Sta/Elev= 30
       0 3444.15    6.51 3439.87   25.76 3424.78    32.7 3417.66    33.5 3416.58
   42.45 3411.86   43.85 3411.67   48.55 3412.01   55.84 3411.48   58.07 3411.21
   63.21 3409.79    71.7 3408.66   77.23 3408.85   86.44 3407.74   91.52 3408.49
   93.05 3407.58  101.54 3401.08   106.6 3398.03  173.68 3390.53   188.3 3389.36
  192.38 3390.64  201.47 3392.35  209.86 3396.14  220.86 3402.04  229.97 3406.46
  233.33 3407.59  244.72 3413.96  253.41 3419.57   267.9 3427.02  286.44 3438.95
#Mann= 3 , 0 , 0
       0     .07       0  173.68     .05       0  201.47     .09       0
Bank Sta=173.68,201.47
Exp/Cntr=0.3,0.1

Type RM Length L Ch R = 1 ,166364  ,257.99,196.82,161.97
BEGIN DESCRIPTION:
166286.0
END DESCRIPTION:
XS GIS Cut Line= 4
  962839.3941958  808366.6048068  962680.1533234  808294.8336525
  962587.0752197  808257.8271151   962478.297528  808267.9203658
#Sta/Elev= 30
       0 3407.59   16.89 3405.17   25.25 3404.46   36.12 3402.74   39.12 3402.61
   60.47 3399.55   67.58 3399.09   85.75 3395.76  116.31    3392  138.64 3390.61
  144.15 3390.71  153.23 3388.47  169.72 3385.98  181.65 3384.61  216.46  3382.6
  246.91 3381.32  265.77 3379.77  282.63 3381.38  289.75 3383.64  294.91 3385.66
   305.1 3395.49  314.04 3402.62  318.52 3406.49  325.48 3413.72  344.76 3429.67
  350.07 3433.11  360.74 3440.75  370.18 3446.75  379.66 3450.97  384.08 3453.39
#Mann= 3 , 0 , 0
       0     .07       0  246.91     .05       0  282.63    .075       0
Bank Sta=246.91,282.63
Exp/Cntr=0.3,0.1

Type RM Length L Ch R = 1 ,166167  ,145.65,141.5,119.6
BEGIN DESCRIPTION:
166089.2
END DESCRIPTION:
XS GIS Cut Line= 6
   962820.330191  808053.7293993  962755.2878704   808064.943098
  962699.2173282  808068.3075149   962624.081757  808067.1860426
  962594.9255257  808072.7934041  962490.6337232  808119.8931921
#Sta/Elev= 30
       0 3398.26       2 3398.07   12.17 3396.13   14.78 3395.35   22.85 3393.53
    28.2 3390.91   41.26 3386.12   54.21 3384.54   66.67 3384.09   80.58 3382.83
    87.6 3381.17   98.28 3379.72  119.97 3377.41  142.47 3376.61  149.36 3377.62
  150.82 3377.62  164.65 3376.37   180.5 3375.28  193.27 3375.21  214.46 3375.93
  222.76 3377.01  230.78 3376.69  247.15  3376.7  263.86 3377.41  280.18  3379.4
  287.54 3381.24  301.33 3387.21  305.56 3389.51  335.85 3408.78   341.5 3411.71
#Mann= 3 , 0 , 0
       0    .075       0  164.65     .05       0  214.46    .065       0
Bank Sta=164.65,214.46
Exp/Cntr=0.3,0.1

Type RM Length L Ch R = 1 ,166026  ,59.78,144.56,175.37
BEGIN DESCRIPTION:
165947.7
END DESCRIPTION:
XS GIS Cut Line= 6
   962820.330191  807912.4300352   962686.881133  807925.8877027
  962633.0535354  807940.4658184  962565.7682702  807948.3161244
  962542.2183762  807957.2868786  962449.1412967  808009.9940281
#Sta/Elev= 30
       0 3403.09   22.58 3394.62   31.22 3392.28   46.19 3384.77   58.56 3379.18
   64.41 3378.24   79.94 3377.69   95.53 3376.18  102.77 3374.74  112.07 3372.35
  119.32  3372.7     161 3372.42  189.71 3371.46  200.26 3370.48  203.64  3371.5
  220.33 3373.59  225.03 3373.29  242.57 3371.51  248.76 3371.32  264.14 3373.36
  283.62 3374.47  297.16 3375.62   312.3 3377.27  325.42 3379.01  347.34 3382.99
  356.43 3386.07  362.38 3388.89  369.52 3391.86  375.91 3393.95  389.84 3399.26
#Mann= 3 , 0 , 0
       0     .07       0  225.03     .05       0  264.14     .06       0
Bank Sta=225.03,264.14
Exp/Cntr=0.3,0.1

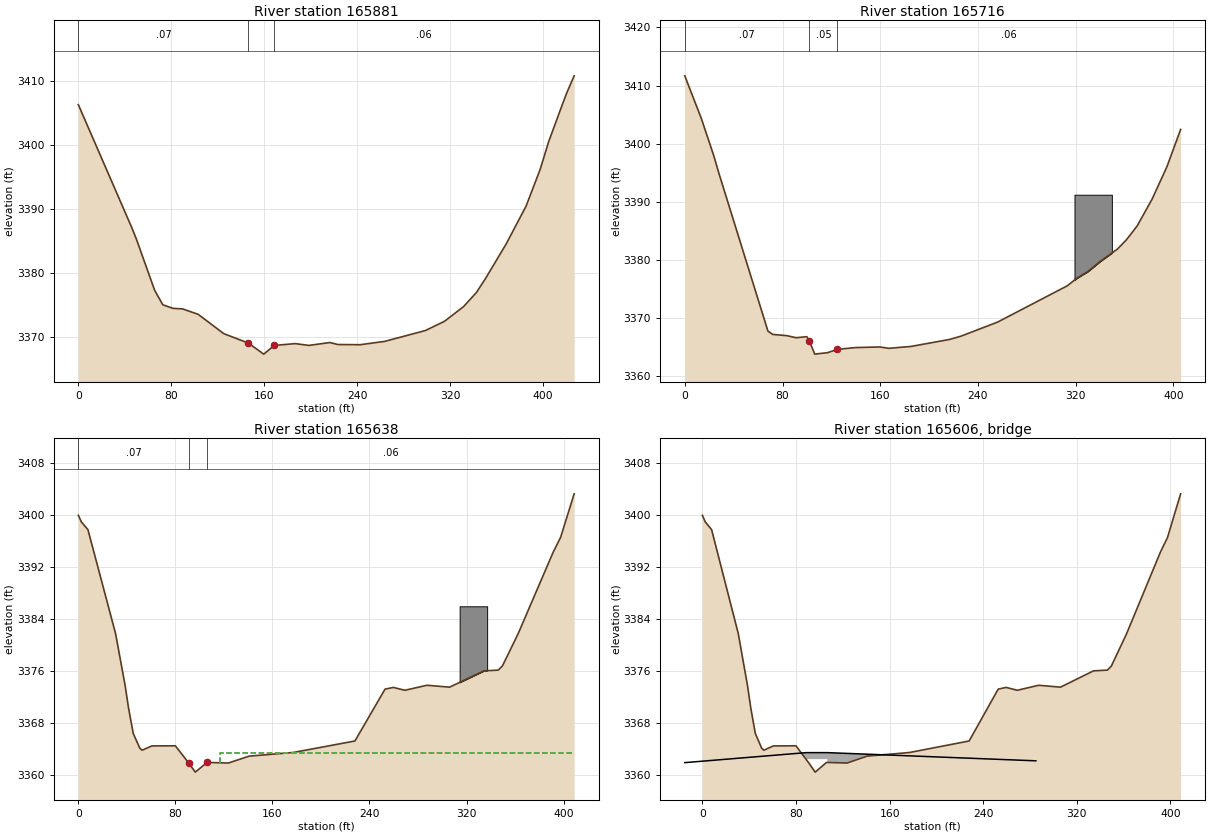
Type RM Length L Ch R = 1 ,165881  ,202.74,165.31,79.95
BEGIN DESCRIPTION:
165803.1
END DESCRIPTION:
XS GIS Cut Line= 6
  962816.9657741  807844.0232978  962730.6165041  807857.4809653
  962681.2747957  807848.5091869  962600.5328872  807815.9885387
  962555.6760438  807810.3811773  962402.0415086  807835.0525436
#Sta/Elev= 30
       0 3406.29   46.07 3387.06    49.9 3385.33   65.68 3377.31   72.72 3375.04
   81.42 3374.49   89.65  3374.4   103.1 3373.56  125.14 3370.54  146.38 3369.06
  159.58 3367.34  168.69  3368.7   186.7 3368.98  198.44  3368.7  216.36 3369.15
  223.36 3368.84  242.57 3368.81  263.67 3369.33  298.64 3371.02  315.06 3372.46
  331.53 3374.76  342.53 3376.95  350.32 3379.12  368.12 3384.52  385.34 3390.45
  397.49 3396.21  404.67 3400.46  414.05 3405.09  420.18 3408.07  426.69 3410.79
#Mann= 3 , 0 , 0
       0     .07       0  146.38     .05       0  168.69     .06       0
Bank Sta=146.38,168.69
Exp/Cntr=0.3,0.1

Type RM Length L Ch R = 1 ,165716  ,72.98,77.65,84.14
BEGIN DESCRIPTION:
165637.8
END DESCRIPTION:
XS GIS Cut Line= 6
  962772.1099549  807639.9255819  962707.0676343  807663.4754759
  962547.8257377  807709.4537916  962513.0621449  807724.0319073
  962433.4406845  807744.2173844  962387.4623688  807766.6458061
#Sta/Elev= 30
       0 3411.67   13.62 3404.29    23.7 3397.95   28.03 3394.84   68.08 3367.77
   72.01  3367.2   83.41 3366.99   91.18 3366.63   99.91 3366.81  102.02 3366.07
   106.4 3363.81  116.92 3364.06  124.99 3364.63  139.92 3364.94  159.65 3365.04
  167.22 3364.81  185.11 3365.13  216.47 3366.32     226 3366.89  256.06 3369.31
  313.28 3375.57  321.13 3376.88  330.23 3378.05  340.12 3379.76  354.22 3381.87
  361.48 3383.44  370.48 3385.88  382.66 3390.48  394.72 3396.01  405.98 3402.45
#Mann= 3 , 0 , 0
       0     .07       0  102.02     .05       0  124.99     .06       0
#Block Obstruct= 1 ,-1
  319.07  349.673391.225
Bank Sta=102.02,124.99
Exp/Cntr=0.5,0.3

Type RM Length L Ch R = 1 ,165638  ,46.21,49.71,84.96
BEGIN DESCRIPTION:
165560.2
END DESCRIPTION:
XS GIS Cut Line= 6
  962735.1023933  807577.1262059  962688.0026053  807592.8257939
  962541.0969039  807621.9830494  962488.3907786  807646.6544157
  962437.9265737  807658.9895867   962352.698776  807709.4537916
#Sta/Elev= 30
       0 3399.94     2.5 3398.92    7.92 3397.73   30.71 3381.73   38.58 3373.75
   41.34 3370.35   45.24 3366.39   50.68 3364.12   52.58  3363.8    60.6 3364.46
   79.96 3364.48   91.04 3361.83   96.43 3360.43  106.11 3361.92  123.72 3361.83
   140.8 3362.89  177.08 3363.45  227.99 3365.22  252.83  3373.2  259.69 3373.46
  269.14 3373.02  287.36 3373.79  306.05  3373.5  334.28 3376.01  346.12 3376.12
  349.55 3376.76  362.41 3381.67  391.52 3394.31  397.46  3396.5   408.7 3403.24
#Mann= 3 , 0 , 0
       0     .07       0   91.04     .05       0  106.11     .06       0
#XS Ineff= 2 , 0
       0    78.8 3363.43   116.8       0 3363.43
Permanent Ineff=
       F       F
#Block Obstruct= 1 ,-1
   314.3  336.993385.942
Bank Sta=91.04,106.11
Exp/Cntr=0.5,0.3

Type RM Length L Ch R = 3 ,165606  ,,,
Bridge Culvert--1,0,-1,-1, 0
Deck Dist Width WeirC Skew NumUp NumDn MinLoCord MaxHiCord MaxSubmerge Is_Ogee
24,14,2.6,0, 7, 7, , , 0.95, 0, 1,1,,
     -15    88.8    88.8    97.8   106.8   106.8     285
 3361.89 3363.43 3363.43 3363.43 3363.43 3363.43 3362.17
                 3362.43 3362.43 3362.43
       5   103.8   103.8   112.8   121.8   121.8     305
 3361.89 3363.43 3363.43 3363.43 3363.43 3363.43 3362.17
                 3362.43 3362.43 3362.43
BR Coef=-1 , 0 , 0 ,, 0 ,,,0.8,-1,,0,
WSPro=,,,, 1 ,,,, 0 ,,,, 0 ,,,,-1 ,-1 ,-1 , 0 , 0 , 0 , 0 , 0
BC Design=,, 0 ,, 0 ,,,,,,