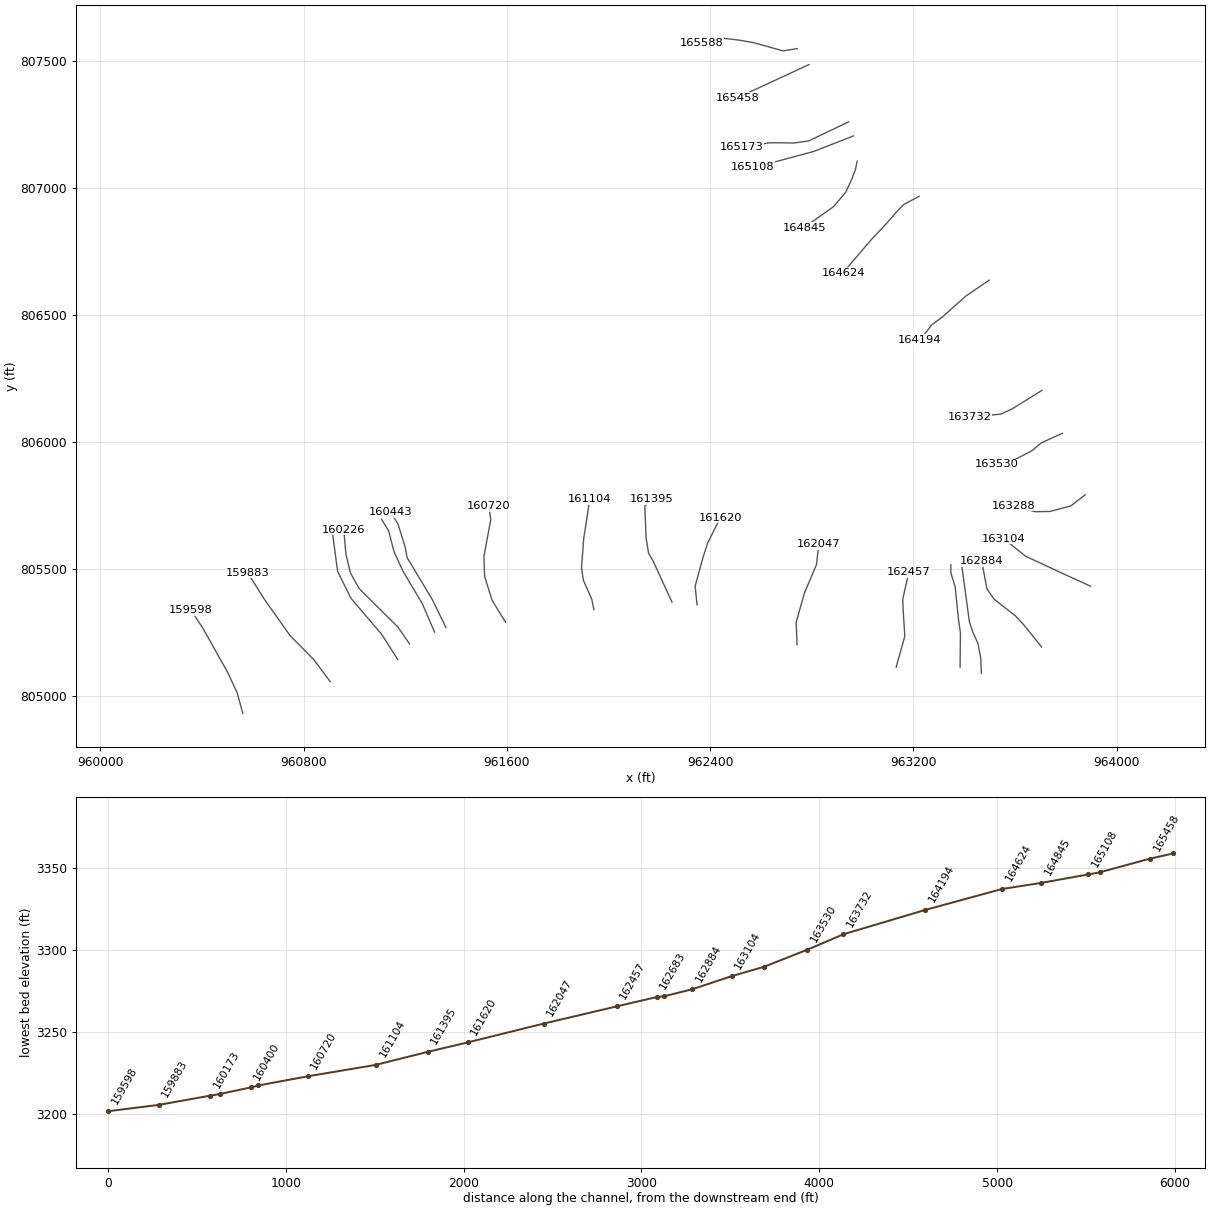
HEC-RAS study lds_big_laurel_crk.prj: lds_big_laurel_crk

--- lds_big_laurel_crk.g20 (geometry) --- (continued)

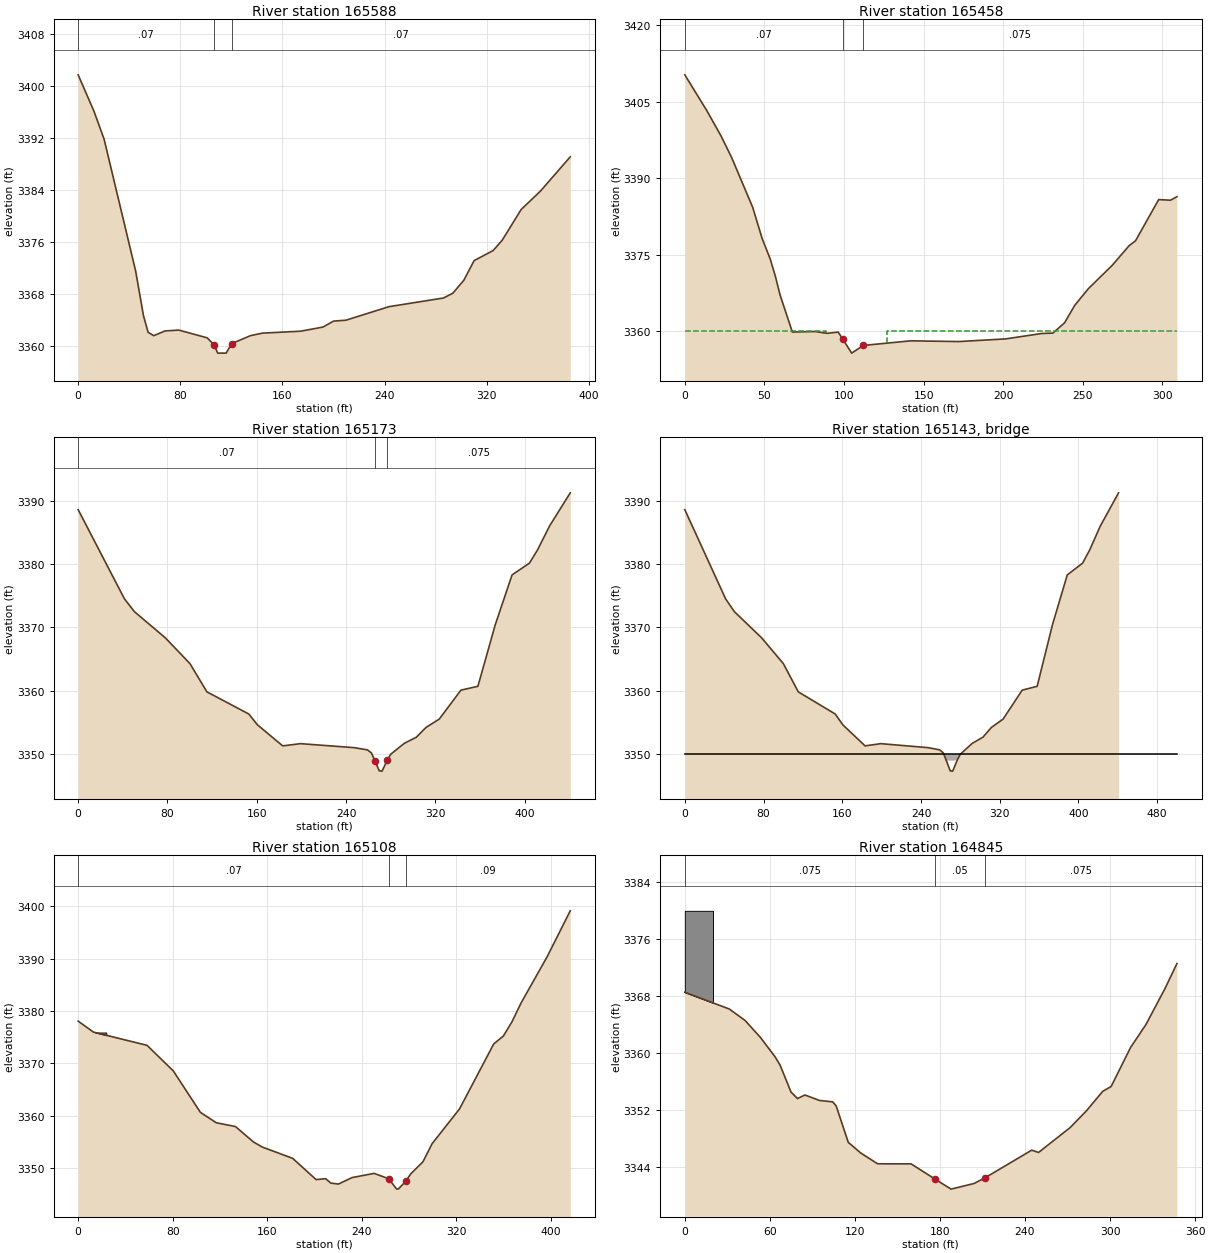
Type RM Length L Ch R = 1 ,165588  ,88.45,130.81,240.32
XS GIS Cut Line= 6
  962742.9526994  807549.0904227   962686.881133  807540.1196686
  962574.7400486  807571.5188445  962519.7899545  807581.6120951
  962455.8691062   807589.461377  962366.1554194  807569.2758999
#Sta/Elev= 30
       0 3401.67   12.39 3396.08   20.32 3391.79   45.02 3371.55   51.19 3364.65
    54.8 3362.11   59.22 3361.59   68.09 3362.32   78.82 3362.45  101.08 3361.26
  106.36  3360.2  109.36 3358.91  115.93 3358.91  120.21 3360.36  134.88 3361.59
   144.3 3361.98  174.28 3362.28  191.69 3362.91  200.07 3363.83  209.78 3363.97
  243.49 3366.05   286.2 3367.38  293.53 3368.12  302.16 3370.12  310.14 3373.12
  325.06 3374.67   332.2 3376.27  347.04 3380.98  362.13 3383.81  385.48 3389.07
#Mann= 3 , 0 , 0
       0     .07       0  106.36     .05       0  120.21     .07       0
#XS Ineff= 2 , 0
       0    88.8    3360   136.8       0    3360
Permanent Ineff=
       F       F
Bank Sta=106.36,120.21
Exp/Cntr=0.5,0.3

Type RM Length L Ch R = 1 ,165458  ,272.59,284.72,207.06
BEGIN DESCRIPTION:
165379.6
END DESCRIPTION:
XS GIS Cut Line= 2
  962788.9310151  807486.2910468  962508.5762557  807356.2064057
#Sta/Elev= 30
       0 3410.32   13.78 3403.33   22.88 3398.26   29.49 3394.05   42.65 3384.33
   48.62 3378.18   53.62 3374.23   56.89 3370.81    59.8 3367.19   67.55 3359.88
   81.83 3359.97   89.45 3359.62    96.3 3359.87    99.3 3358.46   104.8 3355.74
  112.11 3357.25   141.8 3358.15  172.14 3358.01  201.44 3358.53  224.18 3359.59
  231.21 3359.67  238.54  3361.7  244.92 3365.13  253.39 3368.36  268.49 3372.98
  279.01  3376.8  283.07 3377.77   297.6 3385.85  305.04 3385.73  309.06 3386.42
#Mann= 3 , 0 , 0
       0     .07       0    99.3     .05       0  112.11    .075       0
#XS Ineff= 2 , 0
       0    88.8    3360   126.8       0    3360
Permanent Ineff=
       F       F
Bank Sta=99.3,112.11
Exp/Cntr=0.5,0.3

Type RM Length L Ch R = 1 ,165173  ,50.61,64.79,85.65
XS GIS Cut Line= 6
  962945.5080068  807260.8064958  962787.0014682  807185.4630169
  962729.4274362  807177.6444603  962670.4318485  807178.3552382
  962636.6391742  807178.3787942   962523.297756  807163.4278787
#Sta/Elev= 30
       0 3388.56   41.47  3374.5   50.41 3372.48      78 3368.37  100.11  3364.3
  115.34 3359.84  152.86 3356.35  160.55 3354.65  183.18 3351.33  199.13 3351.68
  247.22 3351.05  259.07  3350.7  262.63 3350.22  265.95 3348.92  269.65  3347.4
  272.21 3347.35  276.75 3349.06  279.93 3350.01  291.98 3351.72  302.91  3352.7
  311.54 3354.24   323.4 3355.55  342.78 3360.11  358.01 3360.72  373.54 3370.41
  388.61 3378.28  404.11 3380.12  411.34 3382.19  422.15 3385.97  440.72 3391.21
#Mann= 3 , 0 , 0
       0     .07       0  265.95     .05       0  276.75    .075       0
#XS Ineff= 2 , 0
       0     250    3350     292       0    3350
Permanent Ineff=
       F       F
Bank Sta=265.95,276.75
Exp/Cntr=0.5,0.3

Type RM Length L Ch R = 3 ,165143  ,,,
Bridge Culvert--1,0,-1,-1, 0
Deck Dist Width WeirC Skew NumUp NumDn MinLoCord MaxHiCord MaxSubmerge Is_Ogee
20,12,2.6,0, 6, 6, , , 0.95, 0, 1,1,,
       0     260     260     282     282     500
    3350    3350    3350    3350    3350    3350
                    3349    3349
       0     260     260     282     282     500
    3350    3350    3350    3350    3350    3350
                    3349    3349
BR Coef=-1 , 0 , 0 ,, 0 ,,,0.8,0,,0,
WSPro=,,,, 1 ,,,, 0 ,,,, 0 ,,,,-1 ,-1 ,-1 , 0 , 0 , 0 , 0 , 0
BC Design=,, 0 ,, 0 ,,,,,,

Type RM Length L Ch R = 1 ,165108  ,159.32,262.69,282.3
XS GIS Cut Line= 4
  962963.9882315  807205.3647974  962807.6140266  807144.2368761
  962656.5071569  807103.6211438  962566.6552063  807084.5305104
#Sta/Elev= 30
       0 3378.07   12.97 3375.98   58.28 3373.46   80.54 3368.57  103.39 3360.69
  116.84 3358.71  133.09 3357.98  148.14 3355.07  155.74 3354.08  181.47 3351.92
  201.25 3347.88   209.3 3348.05   213.8  3347.2  220.17 3347.03  231.69 3348.26
  250.33 3349.06  262.67 3348.04  269.26  3346.1  270.74 3346.06  277.05 3347.55
  281.23 3348.94  291.63 3351.27  299.36 3354.71  322.59 3361.35  351.51 3373.73
  359.67 3375.24  366.94 3377.95  374.57 3381.51   396.6 3390.31  416.23 3399.09
#Mann= 3 , 0 , 0
       0     .07       0  262.67     .05       0  277.05     .09       0
#XS Ineff= 2 , 0
       0     250    3348     292       0    3348
Permanent Ineff=
       F       F
#Block Obstruct= 1 ,-1
   14.46    23.83375.905
Bank Sta=262.67,277.05
Exp/Cntr=0.5,0.3

Type RM Length L Ch R = 1 ,164845  ,221.5,220.91,218.26
BEGIN DESCRIPTION:
164767.4
END DESCRIPTION:
XS GIS Cut Line= 6
  962978.4506153  807106.1303741  962971.7217815  807072.4872294
  962956.0221936  807032.1162752  962933.5937719   806983.896039
  962886.4939838  806927.8244727  962769.8670103  806844.8396196
#Sta/Elev= 30
       0  3368.5   31.39 3366.16   42.55 3364.55   53.47 3362.15   63.67 3359.47
   67.22  3358.3   74.95 3354.52   79.54 3353.61   84.73 3354.11   95.07 3353.34
  104.34 3353.15   106.8 3352.58  115.32 3347.48   124.1 3345.99  135.98 3344.47
  159.64 3344.46  176.413342.341  187.83 3340.92  204.04 3341.71  211.473342.466
  244.75 3346.38  249.58 3346.06  271.83 3349.54  283.53 3351.93  294.82 3354.62
  300.78  3355.3  314.49 3360.77  325.23 3363.95  338.72    3369  347.18 3372.52
#Mann= 3 , 0 , 0
       0    .075       0  176.41     .05       0  211.47    .075       0
#Block Obstruct= 1 ,-1
       0   19.923379.915
Bank Sta=176.41,211.47
Exp/Cntr=0.3,0.1

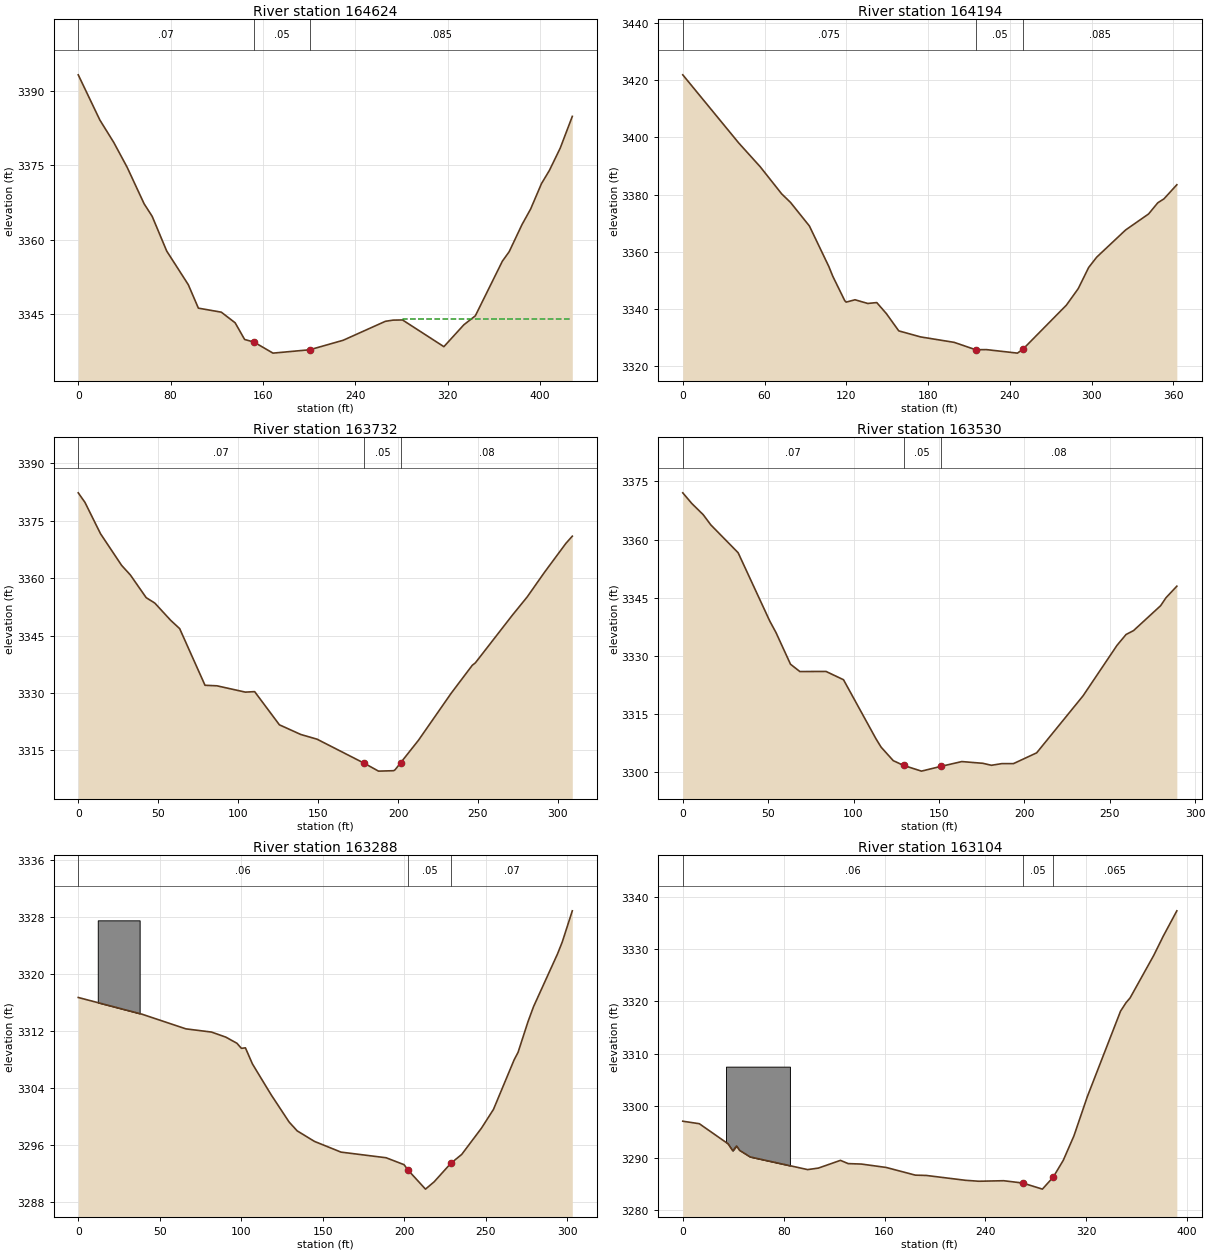
Type RM Length L Ch R = 1 ,164624  ,435.34,430.44,405.66
BEGIN DESCRIPTION:
164546.5
END DESCRIPTION:
XS GIS Cut Line= 6
  963222.9192854  806968.1954269   963162.362854  806935.6747787
    963138.81296  806912.1248847  963092.8356685  806859.4177352
  963035.6426298  806798.8613038  962923.5005212  806667.6551904
#Sta/Elev= 30
       0 3393.26   18.72 3384.16   30.82 3379.62    42.3 3374.66   57.06 3367.28
   64.04 3364.75   76.62 3357.76   95.31 3350.99  104.04 3346.26   123.9 3345.45
  135.88 3343.31  144.09 3339.95  152.16 3339.43  168.67  3337.2  200.54 3337.88
  229.45 3339.79     266 3343.61  272.76 3343.85  280.87 3343.88  316.67  3338.5
  333.96 3342.91  343.88 3344.71  367.31 3355.72  373.23 3357.64   384.2 3363.04
  391.81 3366.24  401.17 3371.34  408.07 3374.02   417.4 3378.49  427.88 3384.89
#Mann= 3 , 0 , 0
       0     .07       0  152.16     .05       0  200.54    .085       0
#XS Ineff= 2 , 0
       0                  280.87       0    3344
Permanent Ineff=
       F       F
Bank Sta=152.16,200.54
Exp/Cntr=0.3,0.1

Type RM Length L Ch R = 1 ,164194  ,475.74,461.72,431.47
BEGIN DESCRIPTION:
164116.1
END DESCRIPTION:
XS GIS Cut Line= 5
  963497.9524283  806637.7820362  963405.5912475  806574.5873284
  963314.4457631  806493.1643431  963271.9107258  806461.5664772
  963225.7306475  806402.0178346
#Sta/Elev= 30
       0 3421.92   41.09 3398.04   56.77 3389.76    72.6 3380.22   79.02 3377.26
    92.9    3369  107.18 3354.78  110.08 3351.37  118.84 3342.85  119.86 3342.34
  126.39 3343.16   135.7 3341.87  142.32 3342.18   149.4  3338.3  158.46 3332.27
  174.44 3330.16  199.13 3328.25  214.81 3325.68  222.82 3325.71  245.57 3324.48
   249.83325.968  281.44 3341.28  290.14 3347.07  297.77 3354.46  303.69 3358.09
  324.86 3367.59  341.75 3373.21  348.49 3377.11  353.03  3378.5  362.47 3383.43
#Mann= 3 , 0 , 0
       0    .075       0  214.81     .05       0   249.8    .085       0
Bank Sta=214.81,249.8
Exp/Cntr=0.3,0.1

Type RM Length L Ch R = 1 ,163732  ,177.71,202.43,205.87
BEGIN DESCRIPTION:
163654.4
END DESCRIPTION:
XS GIS Cut Line= 4
  963705.7648291  806203.9279329  963590.3136091  806132.2264225
  963544.1335308  806110.3510556  963422.6048527  806099.4138843
#Sta/Elev= 30
       0 3382.29    4.22 3379.78   13.93  3371.6   27.12 3363.34   32.62 3360.82
    42.5  3354.9   47.88 3353.49   57.76 3349.01   63.45  3346.8   79.29 3332.01
   86.76 3331.87  104.54 3330.22  110.33 3330.35  125.82 3321.68  139.22 3319.15
  149.34 3317.93  178.96 3311.62  187.81 3309.58  197.22 3309.69  198.15 3309.92
  201.713311.797  212.81 3317.65  233.28 3329.94  246.45 3337.23  248.36 3337.86
  271.56 3350.34   280.8 3355.09  291.45 3361.43     305 3369.08  309.02 3370.96
#Mann= 3 , 0 , 0
       0     .07       0  178.96     .05       0  201.71     .08       0
Bank Sta=178.96,201.71
Exp/Cntr=0.3,0.1

Type RM Length L Ch R = 1 ,163530  ,267.29,241.96,191.79
BEGIN DESCRIPTION:
163451.9
END DESCRIPTION:
XS GIS Cut Line= 5
  963785.9731421  806035.0045042  963703.3344604  805997.3312285
  963666.8758569   805966.949059  963600.0361082  805931.7061521
  963527.1189013  805912.2611539
#Sta/Elev= 30
       0 3372.07    5.28 3369.32   11.96 3366.43   16.42 3363.79   32.41  3356.6
   50.94 3338.95    54.6 3335.96   63.08  3327.8   68.57  3325.9   83.87 3325.93
   94.12 3323.79  113.09 3308.57  116.14 3306.37  123.27 3302.88  129.29 3301.66
  139.77 3300.18   151.1  3301.4  163.42 3302.65  175.72  3302.2  180.74 3301.69
  186.85 3302.12  193.65 3302.12  207.22  3304.9  234.39 3319.63  254.27 3332.67
  259.59 3335.48  263.96 3336.48  279.83 3342.92  282.95 3344.97  289.31 3347.95
#Mann= 3 , 0 , 0
       0     .07       0  129.29     .05       0   151.1     .08       0
Bank Sta=129.29,151.1
Exp/Cntr=0.3,0.1

Type RM Length L Ch R = 1 ,163288  ,263,183.83,156.34
BEGIN DESCRIPTION:
163210.0
END DESCRIPTION:
XS GIS Cut Line= 5
  963875.9039542  805793.1638687  963820.0013768  805749.4141592
  963738.5773673  805727.5387923  963679.0287247    805726.32412
  963593.9596743  805749.4141592
#Sta/Elev= 30
       0 3316.67   39.05 3314.33   66.03 3312.27   81.75 3311.82   90.52 3311.11
   97.33 3310.25  100.07 3309.54  102.53 3309.61  106.86 3307.34  118.25 3303.05
  129.35  3299.2  134.27 3297.97  144.89 3296.49  161.15 3294.99   188.8  3294.2
  199.82 3293.23   202.3 3292.46  212.97  3289.8  218.25 3290.82  228.52 3293.42
   235.2 3294.67  247.33 3298.36  254.66 3300.98  267.31 3307.92  269.74 3308.98
  275.81 3313.26  279.24 3315.39  293.92 3322.77  296.86 3324.46  303.01 3328.82
#Mann= 3 , 0 , 0
       0     .06       0   202.3     .05       0  228.52     .07       0
#Block Obstruct= 1 ,-1
   11.97   37.663327.486
Bank Sta=202.3,228.52
Exp/Cntr=0.3,0.1

Type RM Length L Ch R = 1 ,163104  ,258.57,220.22,173.66
BEGIN DESCRIPTION:
163026.1
END DESCRIPTION:
XS GIS Cut Line= 4
  963896.5636246  805433.4416446  963782.3270769   805485.699181
   963641.355449  805551.3242574  963555.0707021  805620.5943749
#Sta/Elev= 30
       0 3297.04   13.13 3296.56   35.87 3292.72   39.62 3291.38   42.68 3292.29
   44.94 3291.48   53.41  3290.2   99.01 3287.77  107.53 3288.06  125.02 3289.54
  131.14 3288.92  141.68 3288.83  161.33 3288.18   184.4 3286.71  193.07 3286.65
  224.23 3285.72  234.76 3285.54  254.41 3285.64  269.58  3285.2  285.16 3284.03
  293.75 3286.33  301.72 3289.55   310.2 3294.25  320.75 3301.72  347.15 3318.13
  351.48 3319.74  354.71 3320.66  373.49 3328.82  381.03  3332.5  391.77 3337.34
#Mann= 3 , 0 , 0
       0     .06       0  269.58     .05       0  293.75    .065       0
#Block Obstruct= 1 ,-1
   34.27   84.973307.493
Bank Sta=269.58,293.75
Exp/Cntr=0.3,0.1

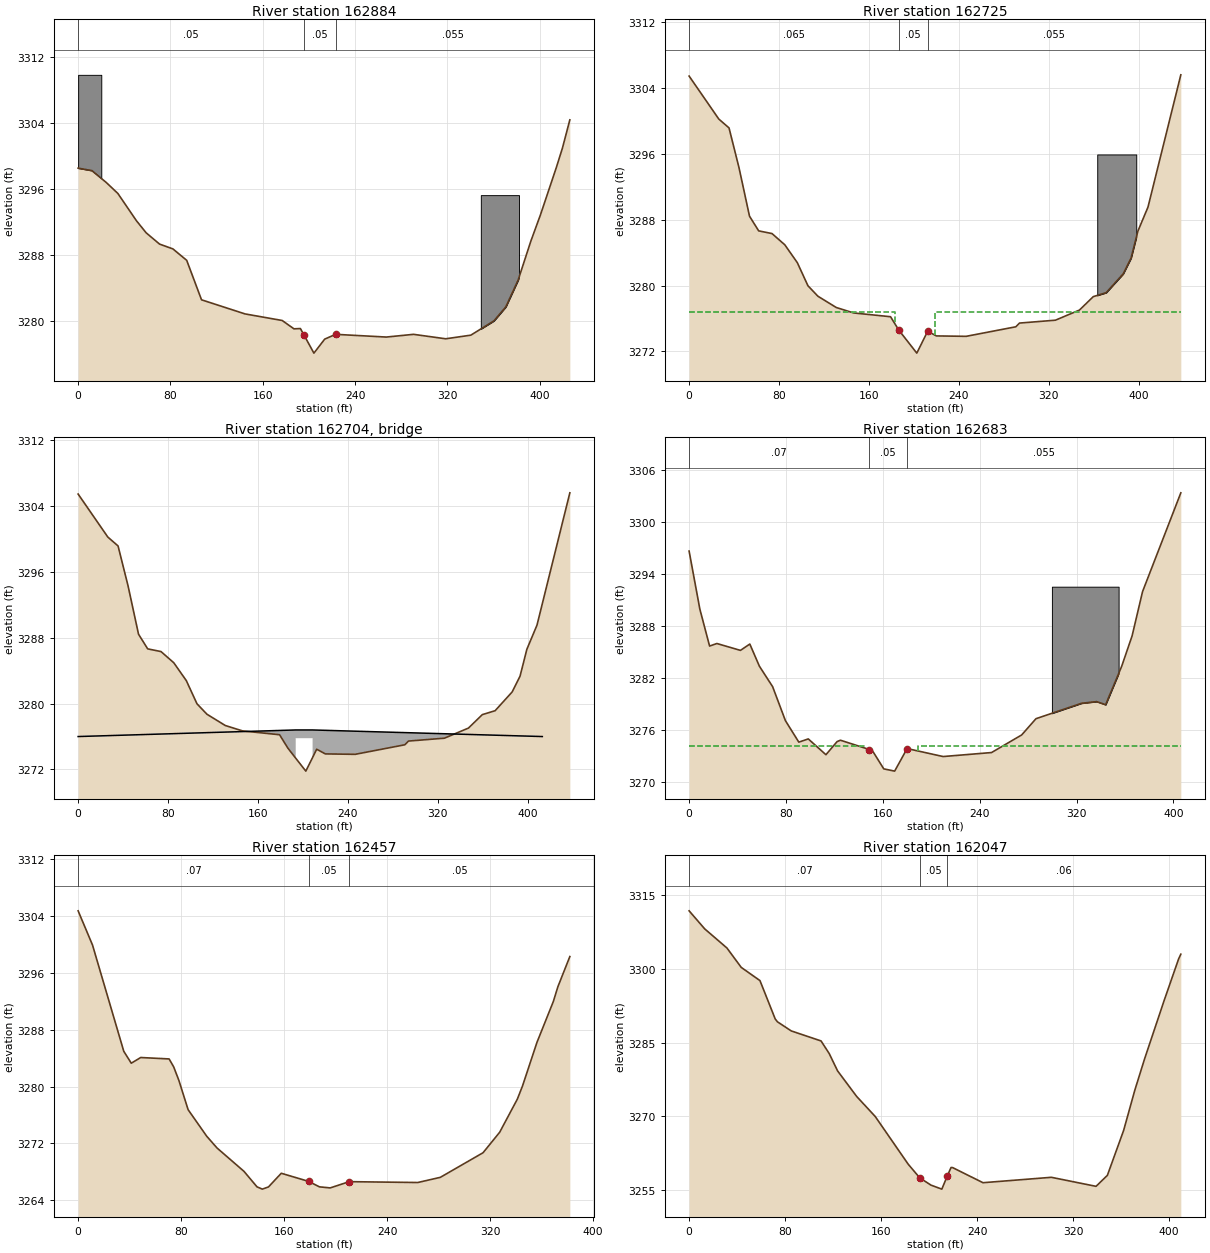
Type RM Length L Ch R = 1 ,162884  ,214.51,158.44,84.41
BEGIN DESCRIPTION:
162805.9
END DESCRIPTION:
XS GIS Cut Line= 6
  963704.5501568   805194.032402  963634.0633187  805281.5318212
  963601.2507805  805316.7747281  963517.3974264  805382.3998046
  963489.4456257  805422.5044732  963468.7859552  805530.6635628
#Sta/Elev= 30
       0 3298.54   11.94 3298.24   24.45 3296.79   34.47 3295.46   50.51 3292.16
   58.95 3290.69   70.58 3289.32   82.12 3288.74   94.09 3287.35  106.93 3282.56
  144.59 3280.85  176.82 3280.05  186.98 3279.04   192.6 3279.07  195.483278.347
   204.3 3276.09  213.65 3277.79  223.13 3278.37  266.99 3278.04  290.62 3278.37
  318.47 3277.83  340.28 3278.27  360.32 3280.01  370.56  3281.7  381.22 3284.94
  392.24 3289.67  400.61 3292.88  414.34 3298.61  419.61 3300.96  426.06  3304.4
#Mann= 3 , 0 , 0
       0     .05       0  195.48     .05       0  223.13    .055       0
#Block Obstruct= 2 ,-1
       0   20.063309.864  348.92  381.993295.264
Bank Sta=195.48,223.13
Exp/Cntr=0.5,0.3

Type RM Length L Ch R = 1 ,162725  ,77.94,42.86,38.49
BEGIN DESCRIPTION:
162647.5
END DESCRIPTION:
XS GIS Cut Line= 6
  963467.5702588  805090.7330256    963465.13989  805147.8512995
  963454.2027187  805207.3999421  963432.3273518  805256.0114133
   963420.174484   805293.684689  963389.7933387  805518.5117192
#Sta/Elev= 30
       0 3305.45   26.41 3300.23   35.52 3299.15   44.46 3294.28   53.74 3288.43
   61.89 3286.65   73.76 3286.32   85.12 3284.96   96.27 3282.79  105.74 3279.98
  114.61 3278.71  130.95 3277.34  146.38 3276.68  179.22 3276.22  186.593274.595
  202.58  3271.8  212.26 3274.46  219.94 3273.89   246.5 3273.84  290.69    3275
  293.95 3275.45  325.91  3275.8  347.29 3277.03  359.59 3278.66  371.02 3279.14
  386.16 3281.42  393.19 3283.34  399.22 3286.59  408.27 3289.54  437.48  3305.6
#Mann= 3 , 0 , 0
       0    .065       0  186.59     .05       0  212.26    .055       0
#XS Ineff= 2 , 0
       0  183.58  3276.8  218.58       0  3276.8
Permanent Ineff=
       F       F
#Block Obstruct= 1 ,-1
   363.1  397.82 3295.93
Bank Sta=186.59,212.26
Exp/Cntr=0.5,0.3

Type RM Length L Ch R = 3 ,162704  ,,,
Node Photo=H:\PROJ\06-0741\CE\GIS\DATA\FRENCH_BROAD_RIVER\SHAPEFILES\survey_data\photos\FBSTR_1793.JPG
BEGIN DESCRIPTION:
162626  FBSTR_1793
END DESCRIPTION:
Bridge Culvert--1,0,-1,-1, 0
Deck Dist Width WeirC Skew NumUp NumDn MinLoCord MaxHiCord MaxSubmerge Is_Ogee
14,11,3,0, 7, 7, , , 0.95, 0, 1,1,,
       0  193.58  193.58  200.58  208.58  208.58     413
    3276  3276.8  3276.8  3276.8  3276.8  3276.8    3276
                  3275.8  3275.8  3275.8
       0  159.26  159.26  166.26  174.26  174.26     400
    3276  3276.8  3276.8  3276.8  3276.8  3276.8    3276
                  3275.8  3275.8  3275.8
BR Coef=-1 , 0 , 0 ,, 0 ,,,0.8,0,,0,
WSPro=,,,, 1 ,,,, 0 ,,,, 0 ,,,,-1 ,-1 ,-1 , 0 , 0 , 0 , 0 , 0
BC Design=,, 0 ,, 0 ,,,,,,

Type RM Length L Ch R = 1 ,162683  ,235.52,225.14,191.87
BEGIN DESCRIPTION:
162604.6
END DESCRIPTION:
XS GIS Cut Line= 6
  963383.7169048  805115.0387612   963384.931577  805249.9349794
  963377.6404709  805299.7611229  963364.2719066  805431.0112758
  963347.2583013   805485.699181  963347.2583013  805517.2960227
#Sta/Elev= 30
       0 3296.63    8.88 3289.94   16.91 3285.69   22.97 3285.98    42.4 3285.19
   50.13 3285.92   58.04 3283.37   68.97 3281.01   79.55 3277.09   90.59 3274.62
   98.43 3274.99  112.99 3273.17  122.19 3274.68  124.98 3274.84  148.87 3273.77
  151.49 3273.61  160.75 3271.54  169.75 3271.28  180.01 3273.88  209.73 3272.96
  249.76 3273.42  274.65 3275.45  286.45 3277.32  324.13  3279.1  336.55 3279.29
  343.96 3278.93  357.23 3283.36  365.82 3286.86  374.45 3291.96  406.06 3303.34
#Mann= 3 , 0 , 0
       0     .07       0  148.87     .05       0  180.01    .055       0
#XS Ineff= 2 , 0
       0  144.26  3274.2  189.26       0  3274.2
Permanent Ineff=
       F       F
#Block Obstruct= 1 ,-1
  299.59  354.683292.528
Bank Sta=148.87,180.01
Exp/Cntr=0.5,0.3

Type RM Length L Ch R = 1 ,162457  ,429.83,410.42,364.52
BEGIN DESCRIPTION:
162379.5
END DESCRIPTION:
XS GIS Cut Line= 5
  963132.1537702  805115.0387612  963166.1820049  805236.5664151
  963161.3202433  805310.6982942  963157.6752023  805379.9694359
  963181.9799137   805489.344222
#Sta/Elev= 30
       0 3304.72   11.17 3299.91   35.45 3284.97   41.27 3283.29    48.6 3284.09
   70.67 3283.89    74.2 3282.78   78.24 3280.88   85.43 3276.75   99.88 3273.02
  107.86 3271.37  128.82 3268.08  138.94  3265.9  143.08 3265.58  147.84 3265.89
  157.78 3267.81     179 3266.67  187.44  3265.9  195.78 3265.75  210.51 3266.63
  263.81 3266.51  281.34 3267.24   314.5  3270.7   327.4 3273.58   341.1 3278.23
  345.05 3280.04  356.34 3286.21  369.07 3291.96   372.6 3294.04   381.9 3298.29
#Mann= 3 , 0 , 0
       0     .07       0     179     .05       0  210.51     .05       0
Bank Sta=179,210.51
Exp/Cntr=0.3,0.1

Type RM Length L Ch R = 1 ,162047  ,424.75,427.18,421.93
BEGIN DESCRIPTION:
161969.1
END DESCRIPTION:
XS GIS Cut Line= 5
  962742.0493765  805202.5392046  962738.4043355  805291.2543202
  962771.2168737  805406.7055402  962818.6126485  805518.5117192
  962827.1194511  805597.5043358
#Sta/Elev= 30
       0 3311.86   12.99 3308.18   31.51 3304.28   43.43 3300.32   59.03 3297.63
   71.75  3289.8    73.6 3289.22   85.12 3287.36  109.93 3285.32  116.75 3282.74
  123.71 3279.21  139.56 3274.01  155.06 3269.91  182.56 3260.17  192.22 3257.38
  201.57  3255.9  210.56 3255.09  215.03 3257.72  218.23  3259.5  219.49 3259.49
  244.85  3256.4  301.81  3257.5  339.06 3255.66   348.5  3257.9  362.04 3267.06
  371.41 3275.31   379.5 3281.66  395.62 3293.44  407.87 3302.06   409.7 3303.01
#Mann= 3 , 0 , 0
       0     .07       0  192.22     .05       0  215.03     .06       0
Bank Sta=192.22,215.03
Exp/Cntr=0.3,0.1

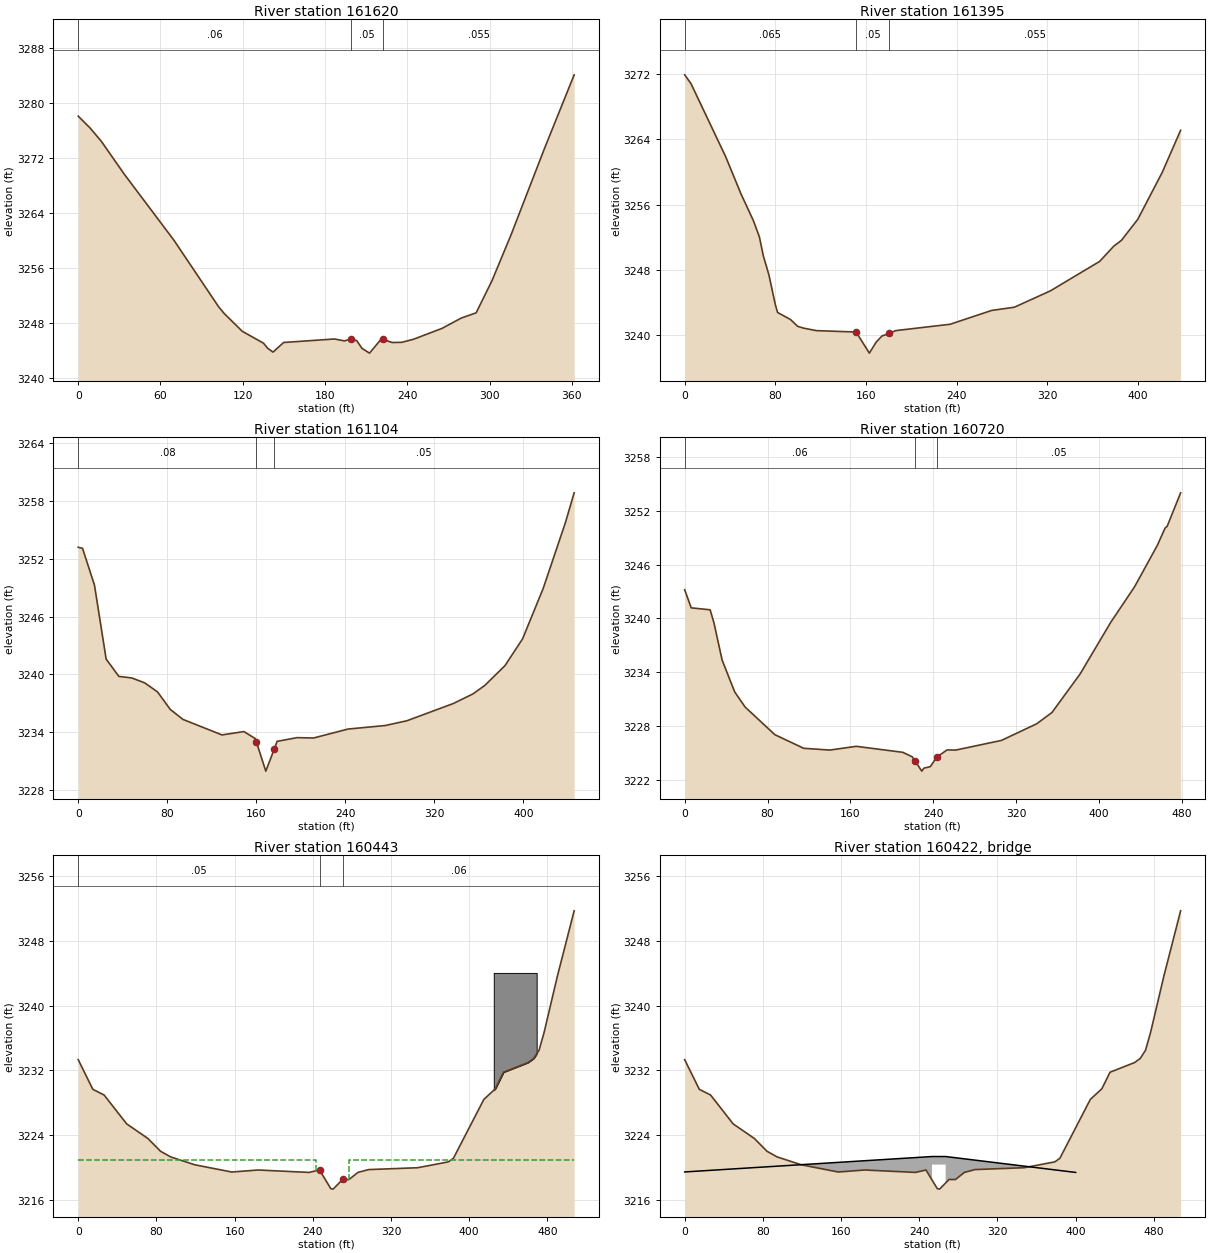
Type RM Length L Ch R = 1 ,161620  ,120.35,225.12,285.87
BEGIN DESCRIPTION:
161541.9
END DESCRIPTION:
XS GIS Cut Line= 5
  962348.2999418  805359.3097654  962341.0078114  805433.4416446
  962371.3899809  805545.2478235  962390.8349791  805604.7964661
  962439.4454261  805702.0183844
#Sta/Elev= 30
       0 3278.13    8.62 3276.42   16.92 3274.45   33.71 3269.65   69.78 3260.07
  102.27 3250.41  106.47 3249.39  119.65  3246.8  135.11 3245.07  138.18 3244.33
  142.07 3243.77  149.83 3245.17  186.87 3245.68  194.18  3245.4  198.81 3245.68
   203.1 3245.44  206.96 3244.32  212.46 3243.62  220.87 3245.64  222.29 3245.62
  228.91 3245.17  235.89 3245.19  244.41 3245.63  265.41 3247.23  279.29 3248.72
  290.22 3249.49  301.84  3254.2  315.87 3260.95  340.01  3273.4  361.69 3284.15
#Mann= 3 , 0 , 0
       0     .06       0  198.81     .05       0  222.29    .055       0
Bank Sta=198.81,222.29
Exp/Cntr=0.3,0.1

Type RM Length L Ch R = 1 ,161395  ,292.06,290.14,227.46
BEGIN DESCRIPTION:
161316.7
END DESCRIPTION:
XS GIS Cut Line= 6
  962249.8623271  805370.2469368  962175.7304479  805531.8792593
  962157.5011462  805563.4761011  962147.7786472  805624.2404401
  962142.9179097  805748.1984627  962168.4383176  805776.1502635
#Sta/Elev= 30
       0 3271.86    5.59 3270.78   36.17 3261.86   49.57 3257.35   60.67 3254.03
   65.92 3252.07   69.44 3249.73   74.32 3247.43   80.08 3243.74   82.02 3242.81
    93.4 3241.95   99.83 3241.11  104.81  3240.9  116.34 3240.59  151.35 3240.42
  163.05 3237.84  169.06 3239.19  174.24 3239.94   180.5 3240.24  186.22 3240.59
  234.38 3241.37  271.03 3243.06     291 3243.45  322.84 3245.45  366.31 3249.05
  378.92 3250.93  385.54 3251.62  399.97 3254.19  421.54 3259.92  437.82 3265.08
#Mann= 3 , 0 , 0
       0    .065       0  151.35     .05       0   180.5    .055       0
Bank Sta=151.35,180.5
Exp/Cntr=0.3,0.1

Type RM Length L Ch R = 1 ,161104  ,385.76,384.59,396.21
BEGIN DESCRIPTION:
161026.6
END DESCRIPTION:
XS GIS Cut Line= 6
  961942.3966151  805341.0804637  961933.8898125  805382.3998046
  961901.0772742  805456.5316837   961893.786168  805505.1431549
  961902.2929707  805620.5943749  961926.5987063  805776.1502635
#Sta/Elev= 30
       0 3253.19    3.87 3253.09   14.64 3249.25    25.1 3241.58   36.54 3239.78
   48.12 3239.62   59.72 3239.11   71.27 3238.17   82.71 3236.35   94.16 3235.31
  129.18  3233.7  148.93 3234.05     159 3233.33  160.19 3232.94  168.55 3229.94
  176.15 3232.23  178.69 3233.03  196.66 3233.42  211.41 3233.38  242.46 3234.31
  275.99 3234.68  295.31 3235.17  336.98 3236.96  354.68 3237.96   365.3 3238.84
  383.48  3240.9  399.28 3243.68  417.78 3248.91  437.75 3255.75  445.62 3258.85
#Mann= 3 , 0 , 0
       0     .08       0  160.19     .05       0  176.15     .05       0
Bank Sta=160.19,176.15
Exp/Cntr=0.3,0.1

Type RM Length L Ch R = 1 ,160720  ,218.08,277.07,345.94
BEGIN DESCRIPTION:
160642.0
END DESCRIPTION:
XS GIS Cut Line= 6
  961594.8272587  805291.2543202    961541.35505  805378.7547636
   961512.188577  805472.3306167  961509.7582082  805551.3242574
  961536.4943126   805694.726254  961529.2021822  805746.9837904
#Sta/Elev= 30
       0 3243.19    6.31 3241.17   24.57 3240.95   28.28 3239.49   36.13 3235.35
    48.3 3231.78   58.32  3230.1   87.06 3227.01  114.93 3225.49  140.16 3225.29
  165.56 3225.71  210.61 3225.04  219.83 3224.53  222.43 3224.08  228.94 3222.94
  230.96 3223.27  237.17 3223.44  243.45 3224.51  253.39 3225.31  261.69 3225.29
  305.91 3226.37  339.96 3228.23  354.67 3229.49  381.88  3233.8  411.31 3239.54
  434.39 3243.52  456.36 3248.14  463.81 3250.07  465.89 3250.28  478.85 3254.01
#Mann= 3 , 0 , 0
       0     .06       0  222.43     .05       0  243.45     .05       0
Bank Sta=222.43,243.45
Exp/Cntr=0.5,0.3

Type RM Length L Ch R = 1 ,160443  ,44.53,42.73,45.16
BEGIN DESCRIPTION:
160365
END DESCRIPTION:
XS GIS Cut Line= 6
  961360.2787536  805270.5946498  961306.8065449  805379.9694359
  961207.1542579  805546.4624958  961199.8621275  805586.5671644
  961171.9113509  805676.4969523  961142.7438537  805725.1084235
#Sta/Elev= 30
       0 3233.33   14.97 3229.67    26.5 3228.97   49.58 3225.41   71.28 3223.61
   84.23 3222.03   94.67 3221.33  119.37 3220.36  157.15 3219.47   184.3 3219.72
   236.2 3219.42  246.88 3219.72  258.47 3217.42  260.78 3217.36  270.49 3218.55
  277.01 3218.54   286.2 3219.42  297.08 3219.77   347.3    3220  378.64 3220.72
  383.87 3221.16  415.06 3228.43  426.84 3229.74   435.2 3231.78  460.26 3232.97
  466.12 3233.48  471.51 3234.49  476.62 3236.66  490.23 3243.61  507.42 3251.69
#Mann= 3 , 0 , 0
       0     .05       0  246.88     .05       0  270.49     .06       0
#XS Ineff= 2 , 0
       0  243.02    3221  277.02       0    3221
Permanent Ineff=
       F       F
#Block Obstruct= 1 ,-1
  425.17  469.063244.031
Bank Sta=246.88,270.49
Exp/Cntr=0.5,0.3

Type RM Length L Ch R = 3 ,160422  ,,,
Node Photo=H:\PROJ\06-0741\CE\GIS\DATA\FRENCH_BROAD_RIVER\SHAPEFILES\survey_data\photos\FBSTR_1792.JPG
BEGIN DESCRIPTION:
160341  FBSTR_1792
END DESCRIPTION:
Bridge Culvert--1,0,-1,-1, 0
Deck Dist Width WeirC Skew NumUp NumDn MinLoCord MaxHiCord MaxSubmerge Is_Ogee
17,11,2.6,0, 7, 7, , , 0.95, 0, 1,1,,
       0  253.02  253.02  260.02  267.02  267.02     400
 3219.48 3221.38 3221.38 3221.38 3221.38 3221.38 3219.42
                 3220.38 3220.38 3220.38
       0  251.79  251.79  258.79  265.79  265.79     400
 3219.71 3221.38 3221.38 3221.38 3221.38 3221.38 3219.13
                 3220.38 3220.38 3220.38
BR Coef=-1 , 0 , 0 ,, 0 ,,,0.8,-1,,0,
WSPro=,,,, 1 ,,,, 0 ,,,, 0 ,,,,-1 ,-1 ,-1 , 0 , 0 , 0 , 0 , 0
BC Design=,, 0 ,, 0 ,,,,,,

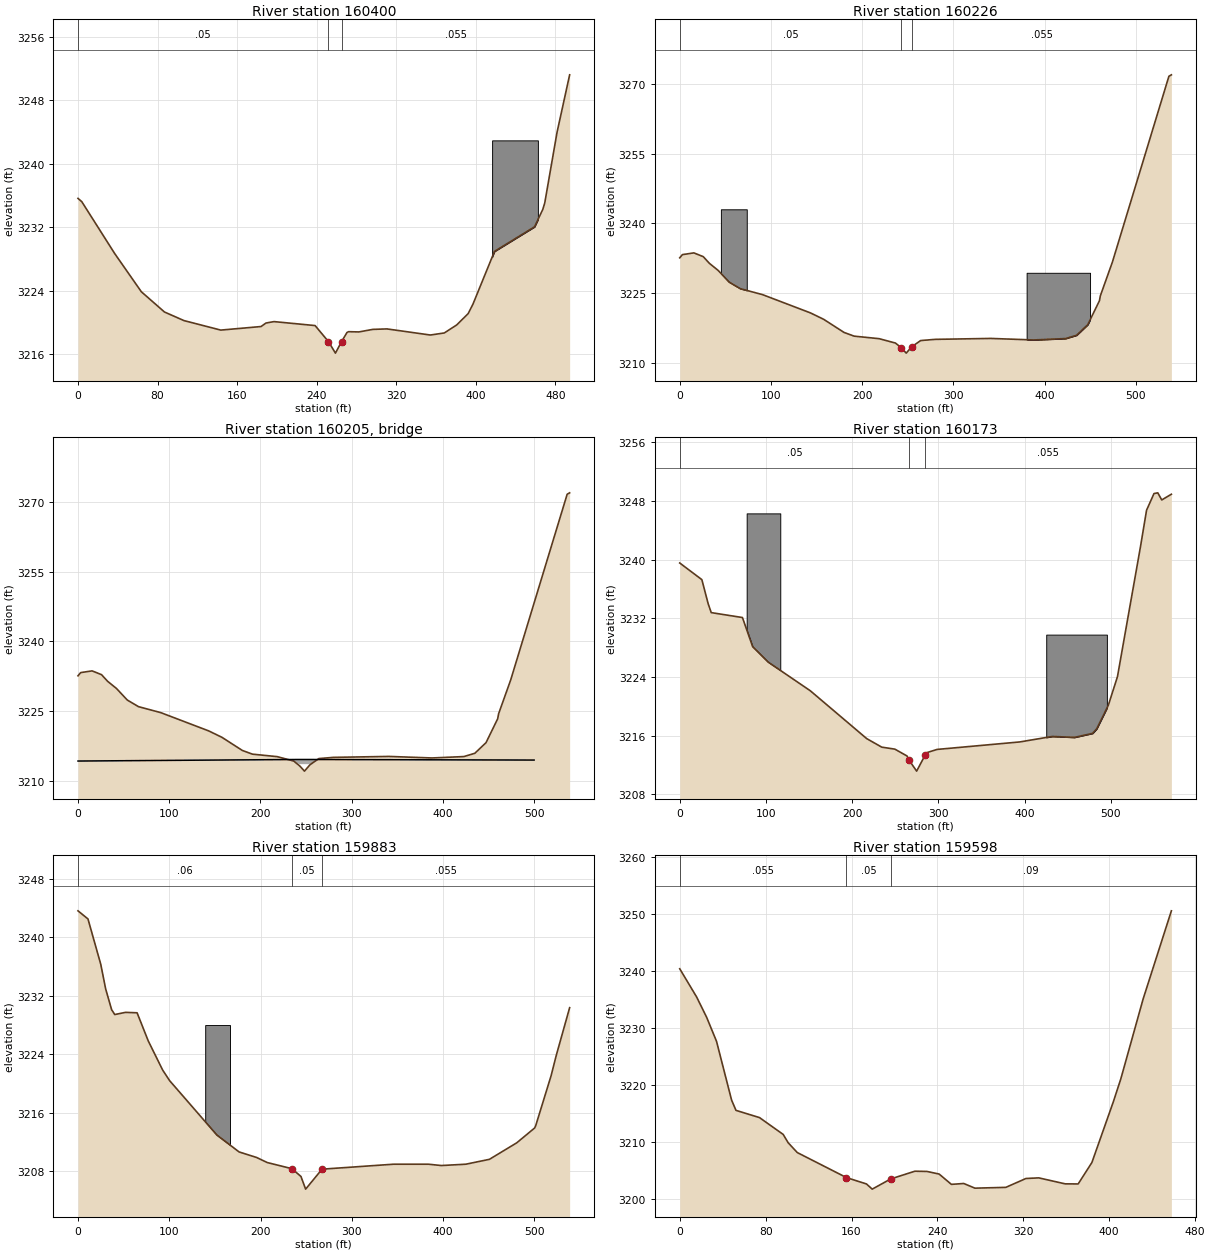
Type RM Length L Ch R = 1 ,160400  ,124.95,174.54,182.8
BEGIN DESCRIPTION:
160322.2
END DESCRIPTION:
XS GIS Cut Line= 6
  961315.3133475  805252.3653481  961267.9175728  805362.9558306
  961191.3553249  805491.7756149  961156.1124179  805568.3378627
  961134.2370511  805652.1922409  961106.2862745  805697.1566228
#Sta/Elev= 30
       0 3235.66    3.83 3235.24    36.9 3228.71   63.68  3223.9   86.92 3221.35
  106.49 3220.27  143.55 3219.07  184.01 3219.52  188.97 3219.96  197.03 3220.14
  238.35 3219.64   251.8 3217.62  258.79 3216.17  264.92 3217.61   270.4 3218.77
  271.97 3218.87   282.4 3218.84  296.37 3219.16  310.58 3219.22   354.2 3218.45
  368.21 3218.71  380.69 3219.72  392.24 3221.15  397.13 3222.37  418.66 3228.98
  458.95 3232.08  467.22 3234.27  469.19 3235.08  481.52 3243.96  494.22 3251.22
#Mann= 3 , 0 , 0
       0     .05       0   251.8     .05       0  264.92    .055       0
#XS Ineff= 2 , 0
       0  241.79    3218  275.79       0    3218
Permanent Ineff=
       F       F
#Block Obstruct= 1 ,-1
  416.28   462.33242.966
Bank Sta=251.8,264.92
Exp/Cntr=0.5,0.3

Type RM Length L Ch R = 1 ,160226  ,71.1,52.55,42.3
BEGIN DESCRIPTION:
160147.7
END DESCRIPTION:
XS GIS Cut Line= 6
  961216.8757328  805206.1852698  961170.6956545  805273.0250185
  961018.7858311  805423.7191455  960984.7586206  805484.4834845
  960966.5293189  805558.6153636  960958.0225162  805655.8372819
#Sta/Elev= 30
       0 3232.61    2.95  3233.3   15.49 3233.67   25.78 3232.86   32.53 3231.42
   42.12  3229.9      54 3227.41   66.32 3225.98   90.85 3224.69  143.27 3220.77
  157.69  3219.4  180.11 3216.57  191.19 3215.77  218.49 3215.23  236.43 3214.29
  243.07 3213.24  248.27 3212.12  254.18 3213.47  264.07 3214.82  280.02 3215.08
  340.89 3215.28  388.08 3214.95  423.01 3215.25  435.03 3215.96  447.28 3218.24
  460.07 3223.38  461.08 3224.45  474.32 3231.72  536.22 3271.64  538.94 3271.95
#Mann= 3 , 0 , 0
       0     .05       0  243.07     .05       0  254.18    .055       0
#XS Ineff= 2 , 0
       0  228.27 3214.62  266.27       0 3214.62
Permanent Ineff=
       F       F
#Block Obstruct= 2 ,-1
    45.1   73.473243.042  380.25  449.793229.394
Bank Sta=243.07,254.18
Exp/Cntr=0.5,0.3

Type RM Length L Ch R = 3 ,160205  ,,,
Node Photo=H:\PROJ\06-0741\CE\GIS\DATA\FRENCH_BROAD_RIVER\SHAPEFILES\survey_data\photos\FBSTR_1244.JPG
BEGIN DESCRIPTION:
160128.2  FBSTR_1244
END DESCRIPTION:
Bridge Culvert--1,0,-1,-1, 0
Deck Dist Width WeirC Skew NumUp NumDn MinLoCord MaxHiCord MaxSubmerge Is_Ogee
10,14,2.6,0, 7, 7, 3214.62, , 0.95, 0, 1,1,,
       0  238.27  238.27  246.27  256.27  256.27     500
 3214.29 3214.62 3214.62 3214.62 3214.62 3214.62  3214.5
                 3213.62 3213.62 3213.62
       0   265.7   265.7   274.7   283.7   283.7     510
 3214.29 3214.62 3214.62 3214.62 3214.62 3214.62  3214.5
                 3213.62 3213.62 3213.62
BR Coef=-1 , 0 , 0 ,, 0 ,,,0.8,-1,,0,
WSPro=,,,, 1 ,,,, 0 ,,,, 0 ,,,,-1 ,-1 ,-1 , 0 , 0 , 0 , 0 , 0
BC Design=,, 0 ,, 0 ,,,,,,

Type RM Length L Ch R = 1 ,160173  ,283.64,290.34,351.14
BEGIN DESCRIPTION:
160095.1
END DESCRIPTION:
XS GIS Cut Line= 6
  961170.6956545  805144.2052343  961106.2862745  805245.0742419
  961028.5083302  805336.2197263  960985.9732928  805386.0458698
  960933.7167806  805491.7756149  960914.2717825  805637.6090044
#Sta/Elev= 30
       0 3239.56   25.65 3237.29   32.92 3234.02   36.53 3232.79    72.7 3232.12
   84.53 3228.15  102.37 3226.06  151.41 3222.13  216.85  3215.6  234.27 3214.44
  249.41 3214.17  263.49 3213.24  265.99 3212.65   274.7 3211.17  284.48 3213.34
  286.42 3213.69  298.41 3214.13  394.23 3215.15  432.01  3215.9  457.68 3215.77
  478.74 3216.32  483.48 3216.94  496.89 3220.13  507.54 3224.05  534.17 3241.74
  541.29 3246.76  549.91 3249.03   554.3 3249.13   558.9 3248.16  570.07 3248.94
#Mann= 3 , 0 , 0
       0     .05       0  265.99     .05       0  284.48    .055       0
#XS Ineff= 2 , 0
       0   255.7 3213.71   293.7       0 3213.71
Permanent Ineff=
       F       F
#Block Obstruct= 2 ,-1
    77.6  116.573246.327  424.95  495.283229.792
Bank Sta=265.99,284.48
Exp/Cntr=0.5,0.3

Type RM Length L Ch R = 1 ,159883  ,338.78,285.03,269.85
BEGIN DESCRIPTION:
159804.8
END DESCRIPTION:
XS GIS Cut Line= 5
  960904.5503076  805057.9215116  960840.1399034  805144.2052343
  960746.5640503   805238.997808  960646.9107391  805379.9694359
  960580.0709903   805485.699181
#Sta/Elev= 30
       0 3243.61   10.92  3242.5   24.92  3236.3   30.32 3232.91   36.84 3230.08
   40.26 3229.41   52.02 3229.71   64.74 3229.65   76.94 3225.81   92.71 3221.82
  100.39 3220.36  152.08 3212.92  176.52  3210.6  195.74 3209.84  207.29 3209.15
  234.34 3208.31  244.27 3207.24  249.37 3205.51  267.36 3208.24  345.55 3208.92
  383.95 3208.92     398 3208.74   424.8 3208.92  450.73 3209.59  480.66 3211.85
  500.25 3213.88  501.39 3214.18  518.28 3221.03   523.9  3223.8   538.6 3230.35
#Mann= 3 , 0 , 0
       0     .06       0  234.34     .05       0  267.36    .055       0
#Block Obstruct= 1 ,-1
  139.35  166.513227.971
Bank Sta=234.34,267.36
Exp/Cntr=0.3,0.1

Type RM Length L Ch R = 1 ,159598  ,355.04,323.1,209.38
BEGIN DESCRIPTION:
159519.7
END DESCRIPTION:
XS GIS Cut Line= 6
  960560.6259922  804932.7477925  960538.7516495  805012.9561055
  960499.8626773  805096.8094595  960470.6951801  805147.8512995
  960406.2858001  805263.3025195  960356.4596566  805339.8657915
#Sta/Elev= 30
       0 3240.41   15.76 3235.44   25.01  3231.9   34.25 3227.66   48.29 3217.32
   52.39 3215.51   74.29 3214.24   96.35 3211.28  100.97 3209.82  109.48 3208.09
  155.29 3203.69  173.91 3202.57  179.28 3201.66  196.47 3203.45  218.99 3204.81
  230.28 3204.77  241.61 3204.31     253  3202.5  264.52 3202.65  274.93 3201.83
   303.7 3201.97  322.45 3203.53   334.4 3203.64  358.93 3202.59   371.1 3202.57
  383.88 3206.34  403.81    3217   410.8 3221.04  431.63 3235.12  457.91  3250.6
#Mann= 3 , 0 , 0
       0    .055       0  155.29     .05       0  196.47     .09       0
Bank Sta=155.29,196.47
Exp/Cntr=0.3,0.1