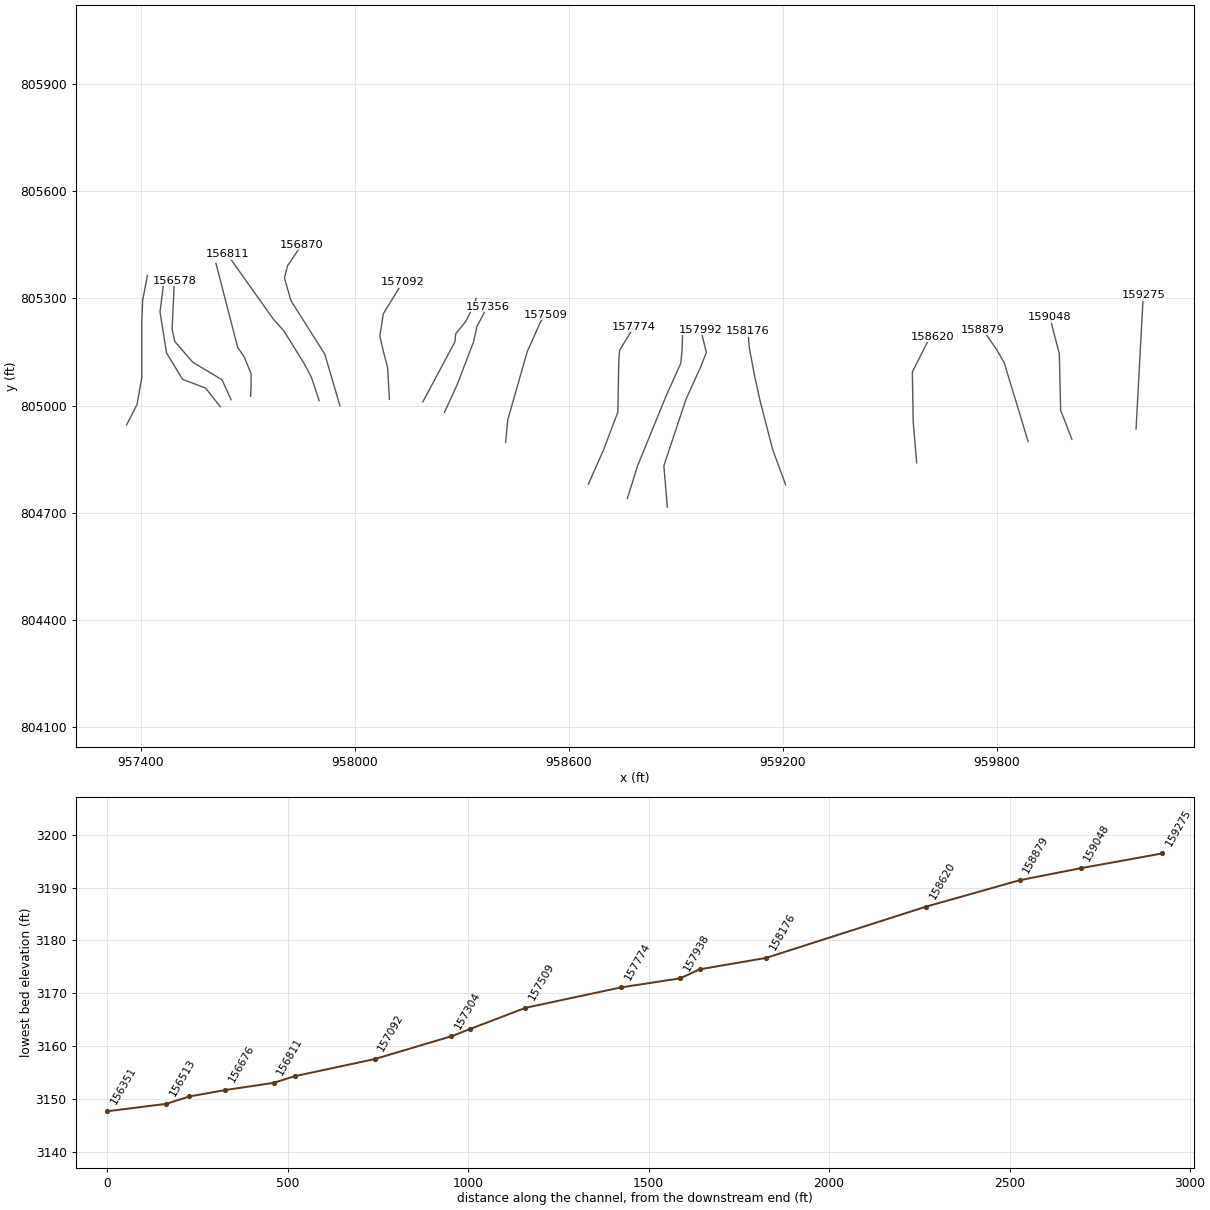
HEC-RAS study lds_big_laurel_crk.prj: lds_big_laurel_crk

--- lds_big_laurel_crk.g20 (geometry) --- (continued)

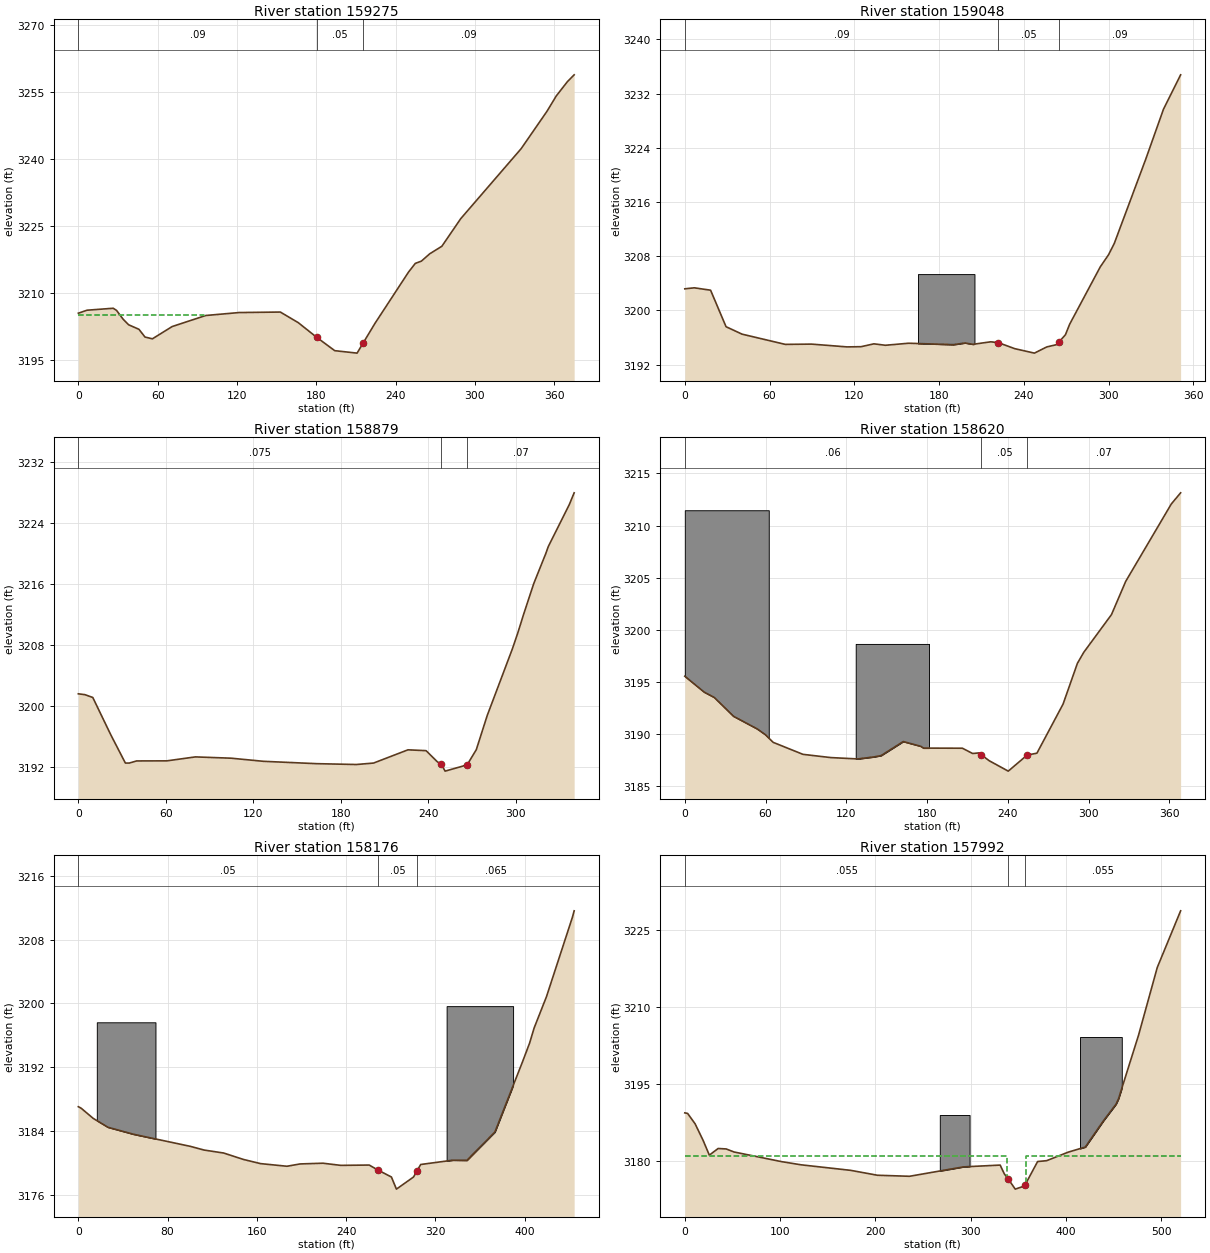
Type RM Length L Ch R = 1 ,159275  ,214.73,226.46,245.87
XS GIS Cut Line= 2
  960189.9358714  804934.6916778  960210.1326144  805309.2869802
#Sta/Elev= 30
       0 3205.41    6.53 3206.08   26.38 3206.52   28.88 3206.05   33.81  3204.1
      38 3202.83   45.87 3201.81   50.43 3200.08   56.04 3199.68   71.01 3202.43
   96.41  3204.9  121.65 3205.56  152.84 3205.67  166.44 3203.29  180.34 3200.02
  193.99 3197.03   210.9 3196.48  215.61  3198.8  224.46 3203.15   249.8  3214.6
  254.96 3216.56  259.58 3217.07   265.8 3218.69  275.05 3220.39  289.34 3226.57
  335.05 3242.23  354.62 3250.61  361.62 3254.03     370 3257.21  375.14 3258.75
#Mann= 3 , 0 , 0
       0     .09       0  180.34     .05       0  215.61     .09       0
#XS Ineff= 2 , 0
       0   95.18    3205               0
Permanent Ineff=
       F       F
Bank Sta=180.34,215.61
Exp/Cntr=0.3,0.1

Type RM Length L Ch R = 1 ,159048  ,116.08,169.49,182.69
BEGIN DESCRIPTION:
158970.2
END DESCRIPTION:
XS GIS Cut Line= 4
  960010.1049724  804906.0116882  959978.5081307  804987.4346734
  959974.8620655  805145.4209307  959948.1259611  805247.5046106
#Sta/Elev= 30
       0 3203.17    6.68 3203.32   18.25 3202.97   29.19 3197.58   40.53 3196.48
   71.13 3194.97    89.7 3195.01   114.8  3194.6  124.72 3194.63  133.82 3195.05
  141.97 3194.84  158.38 3195.14  190.12 3194.93  198.38 3195.18  203.85 3194.98
  216.55 3195.35  221.84 3195.23  233.48 3194.34  247.42 3193.68  256.23  3194.6
  263.09 3194.93  264.94 3195.36  269.37 3196.39  272.37 3197.95  294.05 3206.42
  299.91 3208.21  303.96 3209.88  326.26 3222.34  338.77 3229.69  350.89 3234.76
#Mann= 3 , 0 , 0
       0     .09       0  221.84     .05       0  264.94     .09       0
#Block Obstruct= 1 ,-1
     165     2053205.346
Bank Sta=221.84,264.94
Exp/Cntr=0.3,0.1

Type RM Length L Ch R = 1 ,158879  ,301.2,258.54,190.1
BEGIN DESCRIPTION:
158800.7
END DESCRIPTION:
XS GIS Cut Line= 4
  959887.3626463  804899.9352543  959820.5218734  805119.9005229
  959801.0778994  805153.9277334  959760.9732308  805212.2617037
#Sta/Elev= 30
       0 3201.56    4.52 3201.45    9.91 3201.08   22.29 3196.16   32.25 3192.46
   34.93 3192.46   39.97 3192.74   60.68 3192.75   80.26 3193.27  104.69  3193.1
  126.87 3192.69  163.41 3192.38   190.6 3192.27  202.37 3192.46  225.97  3194.2
  238.37 3194.09  246.13 3192.62  248.71 3192.35  251.42  3191.4   266.5 3192.22
   272.8 3194.22  280.29 3198.71  297.49 3207.45  301.17 3209.52  305.52 3212.18
  312.16 3216.04  320.38 3219.97  322.13 3220.91  336.54 3226.43  339.88 3227.98
#Mann= 3 , 0 , 0
       0    .075       0  248.71     .05       0   266.5     .07       0
Bank Sta=248.71,266.5
Exp/Cntr=0.3,0.1

Type RM Length L Ch R = 1 ,158620  ,392.85,443.83,487.34
BEGIN DESCRIPTION:
158542.2
END DESCRIPTION:
XS GIS Cut Line= 5
  959575.0361969  804840.3866117  959565.3136978  804955.8378317
  959562.8833291  805094.3790908  959606.6330387  805180.6638377
  959618.7859065  805192.8167055
#Sta/Elev= 30
       0 3195.53   14.35 3194.01   21.92 3193.49   36.13 3191.69   53.83 3190.47
   59.81 3189.92   65.69 3189.18   87.81 3188.03  108.49 3187.72  128.57 3187.59
  140.21 3187.78  145.81 3187.91  162.27 3189.26  175.37  3188.8  177.32 3188.63
  206.23 3188.62  213.86 3188.11  218.48 3188.17  220.363187.985  226.12 3187.42
   240.3 3186.42  254.42 3187.97  261.58 3188.14     281 3192.85  291.67 3196.77
  296.41 3197.83     317 3201.45  327.56 3204.64  361.43 3212.07  368.35 3213.14
#Mann= 3 , 0 , 0
       0     .06       0  220.36     .05       0  254.42     .07       0
#Block Obstruct= 2 ,-1
       0   62.383211.468  126.98  181.443198.633
Bank Sta=220.36,254.42
Exp/Cntr=0.3,0.1

Type RM Length L Ch R = 1 ,158176  ,308.92,184.23,122.56
BEGIN DESCRIPTION:
158098.3
END DESCRIPTION:
XS GIS Cut Line= 6
  959208.0218423  804778.4076004  959171.5632389  804876.8441909
  959136.3203319  805012.9561055  959120.5224231  805084.6576159
  959105.9391866   805162.434536  959102.2931214  805208.6156385
#Sta/Elev= 30
       0 3187.05    2.53 3186.86   13.28 3185.59   26.51 3184.47   49.48 3183.59
  100.27 3182.08  112.78 3181.61  130.24 3181.24  148.06 3180.43  163.37 3179.91
  187.03 3179.58  198.85 3179.87   219.3 3179.96  235.28 3179.69  260.75 3179.73
  268.173179.134  280.64 3178.23  285.15 3176.71  300.46 3178.23  303.723179.028
  306.88  3179.8  335.66 3180.34   348.3 3180.32  373.41 3183.87  398.13 3192.67
  404.51 3195.03  408.59 3196.93  419.63 3200.85  442.93 3210.83  444.45 3211.62
#Mann= 3 , 0 , 0
       0     .05       0  268.17     .05       0  303.72    .065       0
#Block Obstruct= 2 ,-1
  330.12  389.713199.663   16.56   69.153197.637
Bank Sta=268.17,303.72
Exp/Cntr=0.5,0.3

Type RM Length L Ch R = 1 ,157992  ,67.75,54.59,66.44
BEGIN DESCRIPTION:
157914.1
END DESCRIPTION:
XS GIS Cut Line= 6
  958876.2514189  804716.4275649  958866.5289198  804831.8798091
  958928.5079311   805017.816843   958969.827272  805108.9623273
   958985.626205  805149.0669959   958969.827272  805212.2617037
#Sta/Elev= 30
       0 3189.38    2.95 3189.28   10.86 3187.24   19.29    3184   25.75 3181.15
   34.97 3182.45   43.43 3182.36   51.63 3181.77  101.81 3179.88  122.14 3179.27
   174.2 3178.19  202.11 3177.24  235.75 3177.04  292.29 3178.87  330.85 3179.22
  335.17 3177.52  339.57 3176.44  346.68 3174.54  356.26 3175.14  357.22 3175.44
  370.14 3179.91  379.64 3180.08  402.14 3181.73  420.15 3182.73  439.26 3187.85
  452.41 3191.08  455.03 3192.13  476.01 3204.49  495.67 3217.68  520.17 3228.71
#Mann= 3 , 0 , 0
       0    .055       0  339.57     .05       0  357.22    .055       0
#XS Ineff= 2 , 0
       0     338    3181     358       0    3181
Permanent Ineff=
       F       F
#Block Obstruct= 2 ,-1
  267.52  298.76 3188.96  414.63  458.443204.147
Bank Sta=339.57,357.22
Exp/Cntr=0.5,0.3

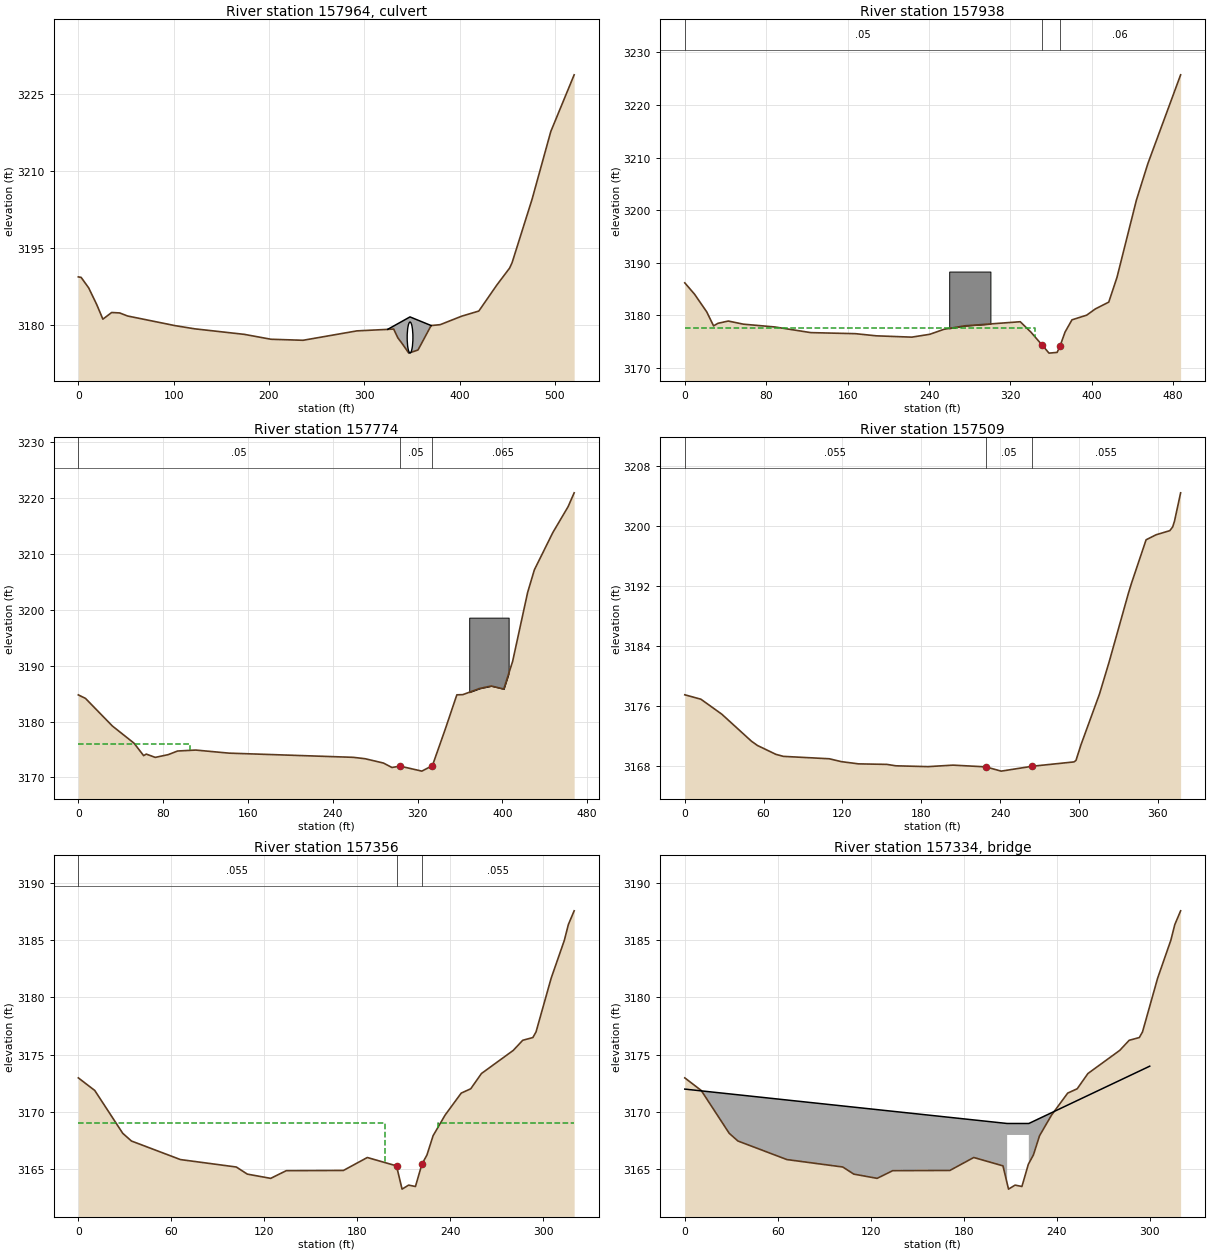
Type RM Length L Ch R = 2 ,157964  ,,,
Node Photo=H:\PROJ\06-0741\CE\GIS\DATA\FRENCH_BROAD_RIVER\SHAPEFILES\survey_data\photos\FBSTR_1790.JPG
BEGIN DESCRIPTION:
157883.1  FBSTR_1790
END DESCRIPTION:
Bridge Culvert--1,0,-1,-1, 0
Deck Dist Width WeirC Skew NumUp NumDn MinLoCord MaxHiCord MaxSubmerge Is_Ogee
19,15,3,0, 3, 3, , , 0.95, 0, 1,1,,
  324.59  347.93  370.14
 3179.17 3181.59 3179.91
                        
  329.67     364  381.95
  3178.8 3179.89 3179.37
                        
BR Coef=-1 , 0 , 0 ,, 0 ,,,0.8,-1,,0,
WSPro=,,,, 1 ,,,, 0 ,,,, 0 ,,,,-1 ,-1 ,-1 , 0 , 0 , 0 , 0 , 0
Culvert=1,6,,16,0.024,0.5,1,2,1,3174.59,348,3172.89,359,Culvert #1  , 0 ,20
Culvert Bottom n=0.024
BC Design=,, 0 ,, 0 ,,,,,,

Type RM Length L Ch R = 1 ,157938  ,108.4,163.79,167.12
BEGIN DESCRIPTION:
157859.5
END DESCRIPTION:
XS GIS Cut Line= 6
  958764.4452399  804740.7333005  958792.3970407  804830.6641126
  958871.3896573  805023.8932769  958913.9246946  805118.6848264
  958917.5707598  805155.1434298  958918.7854321  805198.8931394
#Sta/Elev= 30
       0 3186.19    9.61 3184.03   21.54 3180.68   28.28 3178.01   32.58  3178.5
   42.75 3178.93   57.75 3178.33   88.26 3177.81  123.86 3176.73  167.66 3176.53
  188.15 3176.12  223.02 3175.87  240.73 3176.41  254.87 3177.37  274.98 3178.02
  329.67  3178.8   340.1 3176.83  350.77 3174.45  357.94 3172.83  365.91 3172.97
  368.71 3174.15   373.7 3176.84  380.47 3179.16  394.96 3180.05  403.48 3181.24
  416.64 3182.53  424.73 3187.24  443.77  3201.9  455.02 3208.84  487.26 3225.75
#Mann= 3 , 0 , 0
       0     .05       0  350.77     .05       0  368.71     .06       0
#XS Ineff= 2 , 0
       0     344 3177.53     374       0 3176.84
Permanent Ineff=
       F       F
#Block Obstruct= 1 ,-1
  259.84  300.343188.344
Bank Sta=350.77,368.71
Exp/Cntr=0.5,0.3

Type RM Length L Ch R = 1 ,157774  ,282.89,264.37,248.35
BEGIN DESCRIPTION:
157695.7
END DESCRIPTION:
XS GIS Cut Line= 6
  958655.0704539  804780.8379691  958697.6054912  804876.8441909
  958737.7091356   804982.573936  958740.1405285  805123.5455639
  958742.5708972  805155.1434298  958782.6745417  805220.7685063
#Sta/Elev= 30
       0 3184.77    6.75 3184.14   32.11  3179.2   52.56 3176.12   61.61 3173.89
   64.08 3174.17   72.59 3173.58   84.74 3174.07    93.6 3174.72  110.75 3174.89
  142.08 3174.34  259.33 3173.59  270.52 3173.34  287.73 3172.57  295.85 3171.77
  303.323172.018  324.02 3171.12  333.97  3172.1  345.92 3178.53  357.03 3184.78
  362.63 3184.81   378.6 3185.92  389.53 3186.36  401.29 3185.82  409.62 3190.75
   423.8 3203.11  430.14 3207.15  447.57 3213.83  461.97 3218.46  467.68 3220.94
#Mann= 3 , 0 , 0
       0     .05       0  303.32     .05       0  333.97    .065       0
#XS Ineff= 2 , 0
       0     105    3176               0
Permanent Ineff=
       F       F
#Block Obstruct= 1 ,-1
  368.69  405.883198.597
Bank Sta=303.32,333.97
Exp/Cntr=0.3,0.1

Type RM Length L Ch R = 1 ,157509  ,171.43,152.85,158.62
BEGIN DESCRIPTION:
157431.4
END DESCRIPTION:
XS GIS Cut Line= 5
  958422.9523175  804897.5038614  958429.0287514  804960.6985691
  958483.7166565  805151.4973647  958520.1752599  805232.9213741
  958534.7584964  805254.7957168
#Sta/Elev= 30
       0 3177.45   12.26 3176.86   28.18 3174.86   50.77 3171.25   55.37 3170.68
   69.35  3169.5   75.07 3169.23  109.99 3168.91  119.07 3168.53   132.2 3168.23
   153.8 3168.16  160.67 3167.97  185.15 3167.86  204.24 3168.06  229.08 3167.83
   240.9 3167.26  264.49 3167.91  296.29 3168.49   297.8 3168.69  301.62 3170.78
  315.73 3177.57  323.07 3181.85  337.67 3190.97  339.99  3192.3  351.18 3198.14
  358.79 3198.81  369.23 3199.36  371.43 3199.86  372.81 3200.63  377.47 3204.41
#Mann= 3 , 0 , 0
       0    .055       0  229.08     .05       0  264.49    .055       0
Bank Sta=229.08,264.49
Exp/Cntr=0.5,0.3

Type RM Length L Ch R = 1 ,157356  ,65.9,52.42,36.1
BEGIN DESCRIPTION:
157278.5
END DESCRIPTION:
XS GIS Cut Line= 5
  958251.5985201  804981.3582395   958286.841427  805057.9215116
  958333.0225295   805178.233469  958342.7440044  805221.9831786
  958371.9104775  805276.6710837
#Sta/Elev= 30
       0 3172.98   10.61 3171.88   28.67 3168.14   34.27 3167.47   65.87 3165.85
  101.94  3165.2  109.04 3164.58  124.12 3164.21  134.18 3164.88  171.06  3164.9
  186.48 3166.03  205.31  3165.3   208.9 3163.27  213.13 3163.62  217.54  3163.5
  221.69 3165.44  224.96 3166.25  228.92 3167.93  236.66 3169.73  247.07 3171.65
  253.23 3172.03  260.13 3173.36  280.67 3175.38  286.75 3176.26  293.29  3176.5
  295.35 3176.99  305.11 3181.68  313.63 3184.99   316.2 3186.36  319.95 3187.56
#Mann= 3 , 0 , 0
       0    .055       0  205.31     .05       0  221.69    .055       0
#XS Ineff= 2 , 0
       0     198    3169     232       0    3169
Permanent Ineff=
       F       F
Bank Sta=205.31,221.69
Exp/Cntr=0.5,0.3

Type RM Length L Ch R = 3 ,157334  ,,,
Node Photo=H:\PROJ\06-0741\CE\GIS\DATA\FRENCH_BROAD_RIVER\SHAPEFILES\survey_data\photos\FBSTR_1789.JPG
BEGIN DESCRIPTION:
157256  FBSTR_1789
END DESCRIPTION:
Bridge Culvert--1,0,-1,-1, 0
Deck Dist Width WeirC Skew NumUp NumDn MinLoCord MaxHiCord MaxSubmerge Is_Ogee
15,12,2.6,0, 6, 6, , , 0.95, 0, 1,1,,
       0     208     208     222     222     300
    3172    3169    3169    3169    3169    3174
                    3168    3168
       0     195     195     209     209     300
    3172    3169    3169    3169    3169    3174
                    3168    3168
BR Coef=-1 , 0 , 0 ,, 0 ,,,0.8,0,,0,
WSPro=,,,, 1 ,,,, 0 ,,,, 0 ,,,,-1 ,-1 ,-1 , 0 , 0 , 0 , 0 , 0
BC Design=,, 0 ,, 0 ,,,,,,

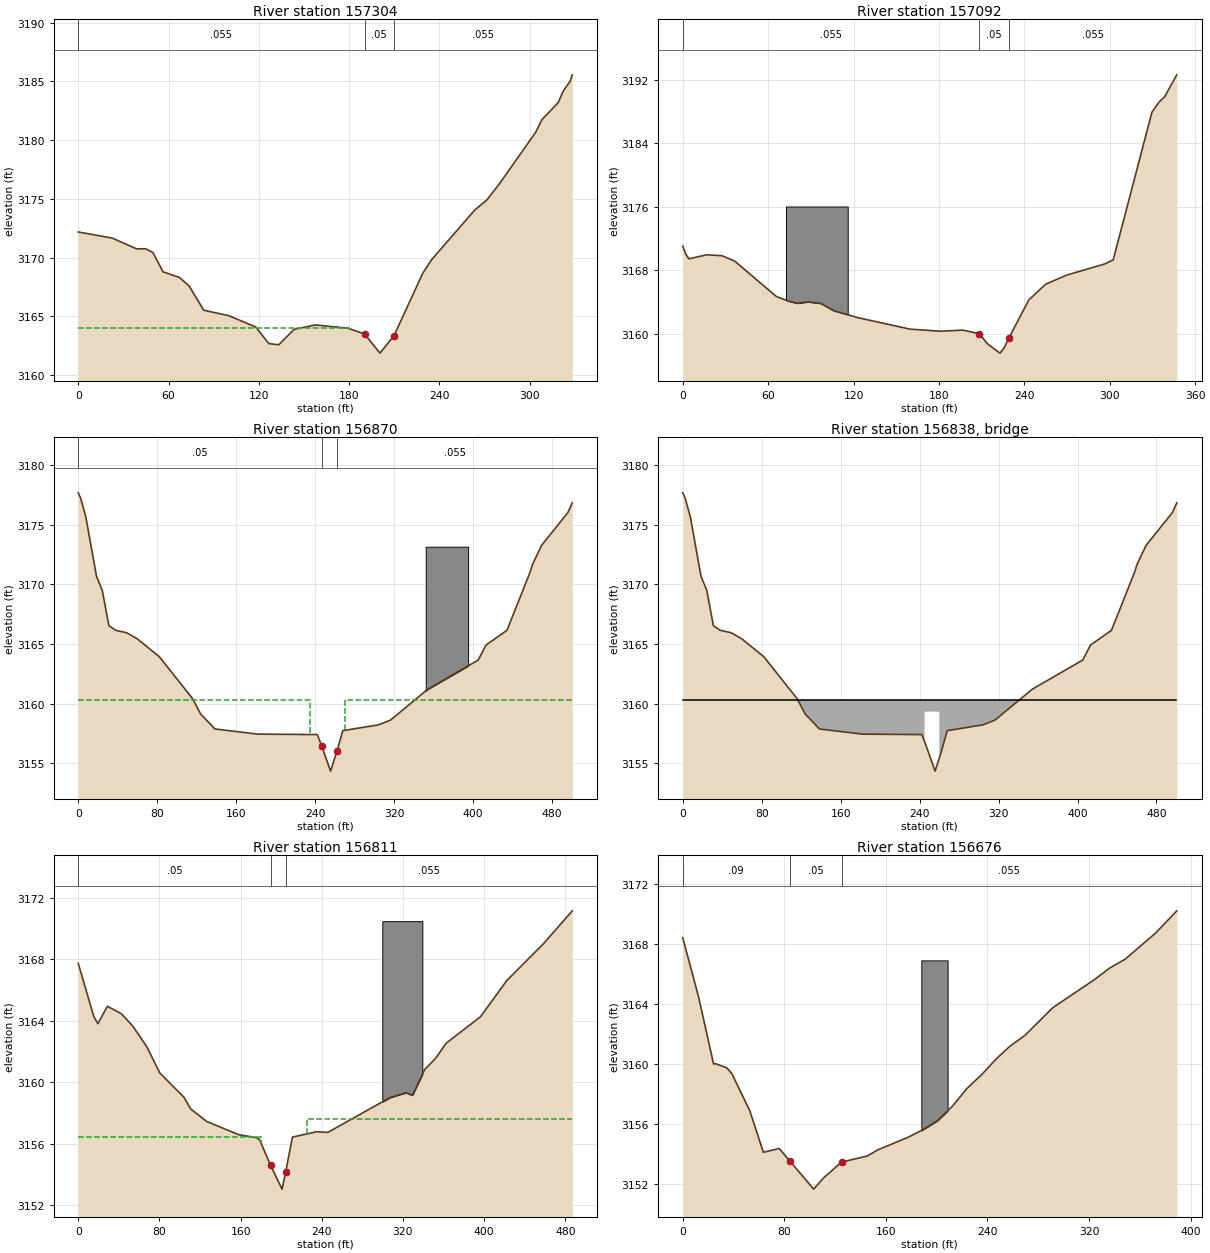
Type RM Length L Ch R = 1 ,157304  ,112.83,212.48,215.85
BEGIN DESCRIPTION:
157226.1
END DESCRIPTION:
XS GIS Cut Line= 6
  958190.8341811  805010.5247126  958280.7649931   805178.233469
  958283.1953619  805201.3235081  958311.1471627  805235.3517428
  958334.2372018  805281.5318212  958340.3136357  805299.7611229
#Sta/Elev= 30
       0 3172.19   22.57 3171.67   38.88 3170.75   44.79 3170.76   49.66 3170.44
   56.35  3168.8   67.23 3168.32   73.68  3167.6   83.42 3165.53  100.27 3165.06
  118.03  3164.1  126.68 3162.69   133.3 3162.59  143.48  3163.9  157.62 3164.28
  179.28    3164   190.3 3163.51  200.54 3161.88  209.94 3163.37  229.04 3168.68
  234.95 3169.84  263.61 3174.06  271.69 3174.92  280.37 3176.36  304.01 3180.66
  308.23 3181.75  319.09  3183.2  322.33 3184.17  327.08 3185.04  328.41 3185.56
#Mann= 3 , 0 , 0
       0    .055       0   190.3     .05       0  209.94    .055       0
#XS Ineff= 2 , 0
       0     180    3164     224       0    3164
Permanent Ineff=
       F       F
Bank Sta=190.3,209.94
Exp/Cntr=0.5,0.3

Type RM Length L Ch R = 1 ,157092  ,152.21,221.95,315.96
BEGIN DESCRIPTION:
157013.6
END DESCRIPTION:
XS GIS Cut Line= 6
   958097.258328   805017.816843  958092.3965663  805105.3172863
  958079.0290263  805157.5737986  958070.5222236  805195.2470742
  958080.2447227  805257.2260855  958134.9316037  805345.9422254
#Sta/Elev= 30
       0 3171.04    2.24    3170    4.37 3169.44   16.77 3169.95   27.52 3169.84
   36.49 3169.16   65.68 3164.71   73.54 3164.16   80.24 3163.84    88.2 3164.02
   97.06 3163.82  105.81 3162.93  123.26 3162.02  159.88 3160.58   181.3 3160.32
  196.82 3160.46  208.33 3160.01  214.08 3158.74  222.93 3157.56   225.8 3158.22
  229.21 3159.48  243.15 3164.26  255.05 3166.25  269.73 3167.39  296.57  3168.8
  302.45 3169.31  329.68 3187.92  334.59 3189.18  338.71  3189.9  347.15 3192.63
#Mann= 3 ,-1 , 0
       0    .055       0  208.33     .05       0  229.21    .055       0
#Block Obstruct= 1 ,-1
   72.53  115.913176.039
Bank Sta=208.33,229.21
Exp/Cntr=0.5,0.3

Type RM Length L Ch R = 1 ,156870  ,57.33,58.63,127.71
BEGIN DESCRIPTION:
156791.7
END DESCRIPTION:
XS GIS Cut Line= 6
  957958.7160446  804999.5875413  957916.1820315  805144.2052343
   957821.390482   805293.684689  957803.1611803  805356.8793967
  957811.6679829  805390.9076314  957851.7716273  805450.4552498
#Sta/Elev= 30
       0  3177.7    2.52 3177.23    7.73 3175.66   18.52 3170.68   24.34 3169.51
   31.05 3166.54   37.96 3166.15   48.94 3165.95   59.76 3165.44   82.06 3163.94
  115.87 3160.41     124 3159.12  138.55 3157.86  181.96 3157.43  242.27 3157.39
  246.64 3156.44   255.7 3154.32  262.04 3155.97  268.07 3157.72  304.39 3158.21
  316.49 3158.61  354.15  3161.2  405.28 3163.65  413.18 3164.91  434.42 3166.15
  458.05 3171.07  460.24 3171.67  469.54 3173.29  496.16 3176.04  500.63 3176.86
#Mann= 3 , 0 , 0
       0     .05       0  246.64     .05       0  262.04    .055       0
#XS Ineff= 2 , 0
       0     235 3160.32     270       0 3160.32
Permanent Ineff=
       F       F
#Block Obstruct= 1 ,-1
  352.12  395.073173.173
Bank Sta=246.64,262.04
Exp/Cntr=0.5,0.3

Type RM Length L Ch R = 3 ,156838  ,,,
BEGIN DESCRIPTION:
156762  FBSTR_1242
END DESCRIPTION:
Bridge Culvert--1,0,-1,-1, 0
Deck Dist Width WeirC Skew NumUp NumDn MinLoCord MaxHiCord MaxSubmerge Is_Ogee
20,15,2.6,0, 6, 6, , , 0.95, 0, 1,1,,
       0     245     245     260     260     500
 3160.32 3160.32 3160.32 3160.32 3160.32 3160.32
                 3159.32 3159.32
       0     195     195     210     210     500
 3160.32 3160.32 3160.32 3160.32 3160.32 3160.32
                 3159.32 3159.32
BR Coef=-1 , 0 , 0 ,, 0 ,,,0.8,0,,0,
WSPro=,,,, 1 ,,,, 0 ,,,, 0 ,,,,-1 ,-1 ,-1 , 0 , 0 , 0 , 0 , 0
BC Design=,, 0 ,, 0 ,,,,,,

Type RM Length L Ch R = 1 ,156811  ,176.17,134.61,62.1
BEGIN DESCRIPTION:
156733.0
END DESCRIPTION:
XS GIS Cut Line= 6
  957900.3830985  805014.1707778  957878.5077316  805079.7958543
  957857.8480612  805118.6848264  957801.9454838  805208.6156385
  957771.5633143   805242.642849  957642.7445542  805423.7191455
#Sta/Elev= 30
       0 3167.74   15.32 3164.28   19.31 3163.81   28.75 3164.95   42.51 3164.46
   53.62 3163.67   67.65 3162.31   80.27 3160.62  104.24 3159.03   110.7 3158.28
  126.58 3157.46  158.49 3156.59  175.74 3156.41  178.74 3156.27  189.49 3154.62
  200.87 3153.06  204.43 3154.17   211.1 3156.44  234.92 3156.79  246.07 3156.75
  307.24 3159.01     323 3159.33  329.32 3159.16  341.47 3160.83  352.32 3161.57
  362.74 3162.55   396.4 3164.26   422.4 3166.62  458.48 3169.01  486.94 3171.15
#Mann= 3 , 0 , 0
       0     .05       0  189.49     .05       0  204.43    .055       0
#XS Ineff= 2 , 0
       0     180 3156.42     225       0 3157.63
Permanent Ineff=
       F       F
#Block Obstruct= 1 ,-1
  299.66  339.153170.478
Bank Sta=189.49,204.43
Exp/Cntr=0.5,0.3

Type RM Length L Ch R = 1 ,156676  ,68.86,98.29,135.71
BEGIN DESCRIPTION:
156598.4
END DESCRIPTION:
XS GIS Cut Line= 6
  957708.3696307  805026.3236456   957709.584303  805054.2754464
   957709.584303  805089.5183533   957690.140329  805136.9141281
  957671.9110273  805163.6502325  957611.1466883  805398.1987376
#Sta/Elev= 30
       0  3168.4    12.4 3164.49   24.27 3160.01   25.88 3160.03   34.73 3159.75
   38.73 3159.36   52.82 3156.89   63.51 3154.14   75.95 3154.39   84.31 3153.56
  103.12 3151.69  110.93 3152.44   125.1 3153.49  145.33 3153.89  153.33 3154.29
  177.34 3155.13  188.87 3155.63  200.55 3156.24  212.48 3157.21  223.92 3158.39
  235.52 3159.31  247.15 3160.37  257.56 3161.18  269.61 3161.92  291.41 3163.75
  323.76 3165.59  336.32 3166.39  348.32 3166.97  372.24  3168.7   389.1 3170.19
#Mann= 3 , 0 , 0
       0     .09       0   84.31     .05       0   125.1    .055       0
#Block Obstruct= 1 ,-1
  187.89  208.593166.896
Bank Sta=84.31,125.1
Exp/Cntr=0.5,0.3

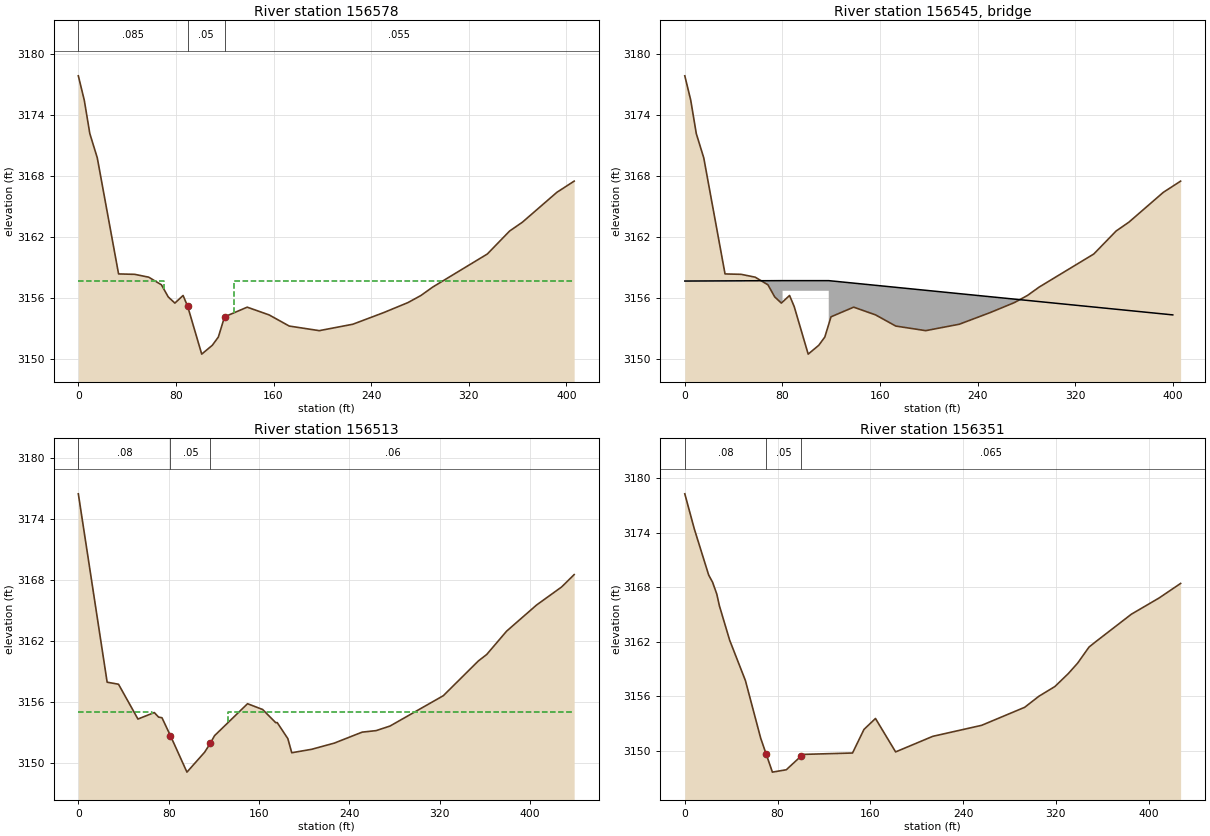
Type RM Length L Ch R = 1 ,156578  ,37.42,64.92,37.01
BEGIN DESCRIPTION:
156500.1
END DESCRIPTION:
XS GIS Cut Line= 6
  957653.6817256  805016.6011465  957628.1613177  805072.5047481
  957546.7373082  805121.1151951  957495.6954683  805179.4491654
  957488.4043621   805213.476376   957494.480796  805349.5872664
#Sta/Elev= 30
       0 3177.87    4.86 3175.48    9.43 3172.18   15.54  3169.8   32.99 3158.38
   46.23 3158.34   57.71 3158.06   68.12 3157.31   73.69 3156.12   79.14 3155.51
   85.87 3156.26   89.663155.177  101.14 3150.49  109.82 3151.36  114.77 3152.17
  119.86 3154.16  138.43 3155.11  156.36 3154.35  172.93 3153.25  197.52  3152.8
     225 3153.43   250.2 3154.57  270.19 3155.56  280.85 3156.26  290.52 3157.09
  335.25 3160.34  353.53  3162.6  364.01 3163.47  392.27 3166.41  406.43 3167.51
#Mann= 3 , 0 , 0
       0    .085       0   89.66     .05       0  119.86    .055       0
#XS Ineff= 2 , 0
       0      70 3157.72     128       0 3157.72
Permanent Ineff=
       F       F
Bank Sta=89.66,119.86
Exp/Cntr=0.5,0.3

Type RM Length L Ch R = 3 ,156545  ,,,
BEGIN DESCRIPTION:
156470  FBSTR_1240
END DESCRIPTION:
Bridge Culvert--1,0,-1,-1, 0
Deck Dist Width WeirC Skew NumUp NumDn MinLoCord MaxHiCord MaxSubmerge Is_Ogee
14,38,2.6,0, 6, 6, , , 0.95, 0, 1,1,,
       0      80      80     118     118     400
 3157.68 3157.72 3157.72 3157.72 3157.72 3154.35
                 3156.72 3156.72
       0      80      80     118     118     400
 3157.68 3157.72 3157.72 3157.72 3157.72 3154.35
                 3156.72 3156.72
BR Coef=-1 , 0 , 0 ,, 0 ,,,0.8,0,,0,
WSPro=,,,, 1 ,,,, 0 ,,,, 0 ,,,,-1 ,-1 ,-1 , 0 , 0 , 0 , 0 , 0
BC Design=,, 0 ,, 0 ,,,,,,

Type RM Length L Ch R = 1 ,156513  ,249.63,162.42,58.21
BEGIN DESCRIPTION:
156435.2
END DESCRIPTION:
XS GIS Cut Line= 6
  957623.2995561  804997.1571725  957581.9802152  805049.4136848
  957517.5708352  805073.7194204  957472.6054291  805147.8512995
  957454.3761274  805262.0878472  957466.5289952  805359.3097654
#Sta/Elev= 30
       0  3176.5   25.52 3157.94   35.59 3157.74    52.8 3154.31   67.28 3154.95
   71.09  3154.5   74.07 3154.44   81.583152.674    96.2 3149.08  111.85 3151.04
  117.06 3151.95  120.63 3152.67  149.87 3155.82  163.26 3155.25  174.85 3153.95
  176.17 3153.96  185.57 3152.38  189.04 3150.99  206.71 3151.33  226.75 3151.94
  251.38 3153.02  263.76 3153.17  276.06 3153.62  323.27 3156.61  354.27 3160.03
  361.69 3160.67  379.34 3162.97  405.81 3165.54  428.01 3167.32  439.16 3168.54
#Mann= 3 , 0 , 0
       0     .08       0   81.58     .05       0  117.06     .06       0
#XS Ineff= 2 , 0
       0      65    3155     133       0    3155
Permanent Ineff=
       F       F
Bank Sta=81.58,117.06
Exp/Cntr=0.5,0.3

Type RM Length L Ch R = 1 ,156351  ,204.62,286.4,275.27
BEGIN DESCRIPTION:
156272.8
END DESCRIPTION:
XS GIS Cut Line= 6
  957360.8002743  804946.1153326  957389.9667474  805003.2336064
  957403.3342875  805079.7958543  957403.3342875  805234.1360464
  957405.7646562  805294.9003854  957419.1332204  805364.1705029
#Sta/Elev= 30
       0 3178.25    8.22 3174.39    20.6 3169.33   23.94 3168.55   27.57 3167.25
   29.87 3165.94   38.68 3162.18   52.29 3157.74   65.46 3151.41   70.273149.636
   75.55 3147.69   87.54 3147.95  100.18 3149.44  102.81 3149.64  144.64 3149.79
  154.51 3152.38  164.43 3153.58   181.8 3149.91  213.83 3151.62     256 3152.83
  293.12 3154.81  305.33 3156.02  319.15 3157.09  330.71 3158.51  338.83 3159.67
  348.54 3161.42  353.74 3161.95  385.07 3165.03  408.96 3166.81  427.56 3168.41
#Mann= 3 , 0 , 0
       0     .08       0   70.27     .05       0  100.18    .065       0
Bank Sta=70.27,100.18
Exp/Cntr=0.3,0.1