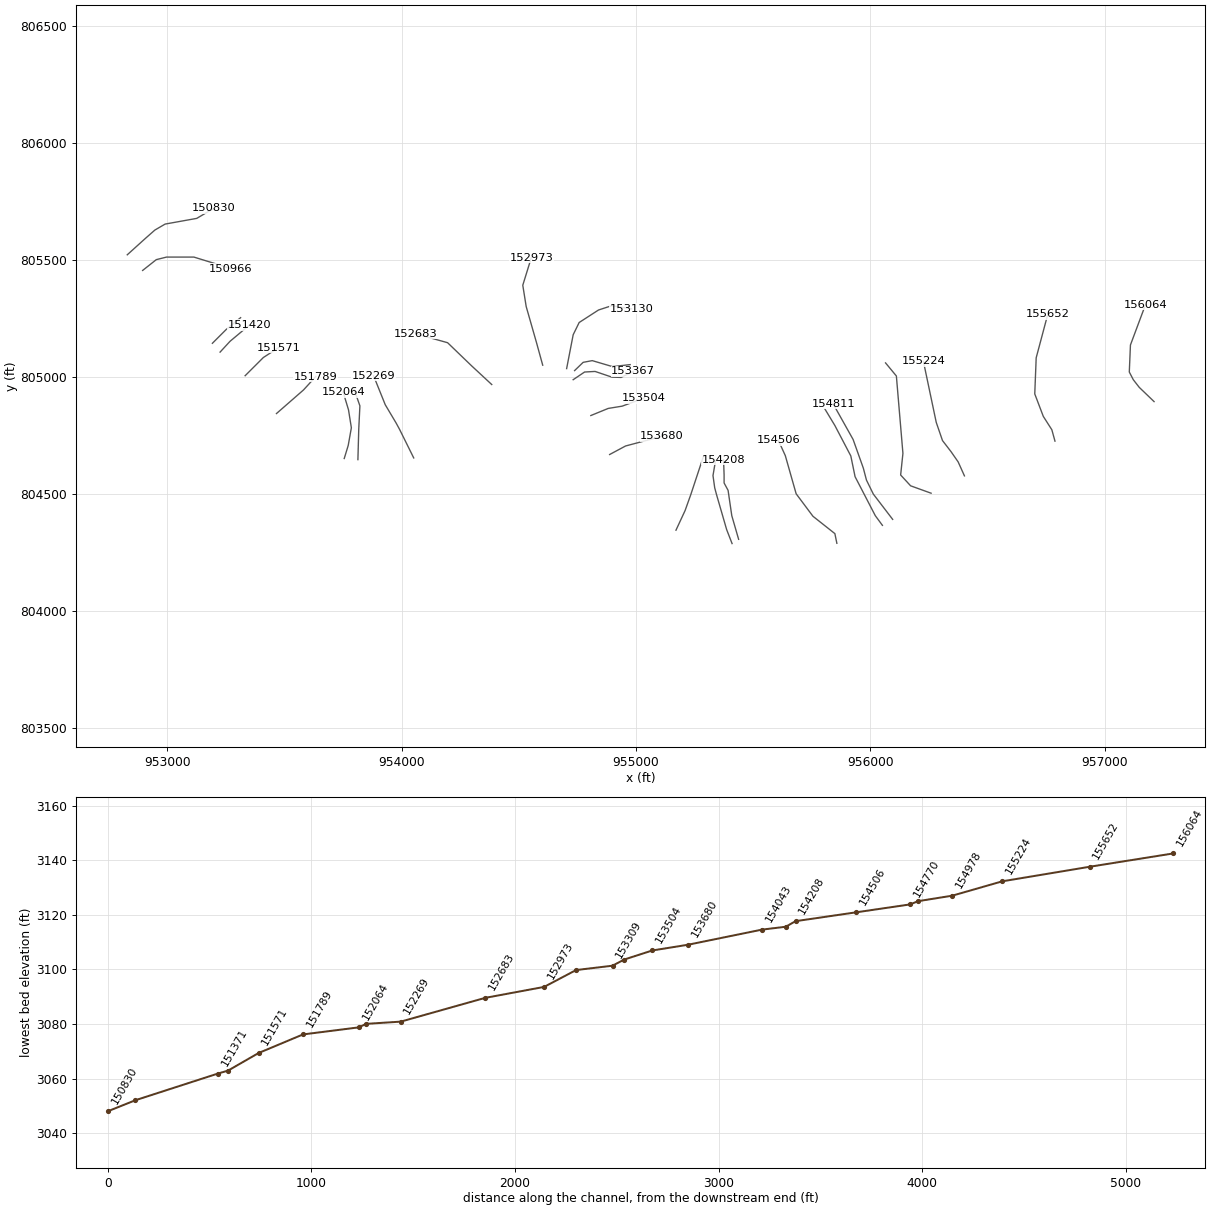
HEC-RAS study lds_big_laurel_crk.prj: lds_big_laurel_crk

--- lds_big_laurel_crk.g20 (geometry) --- (continued)

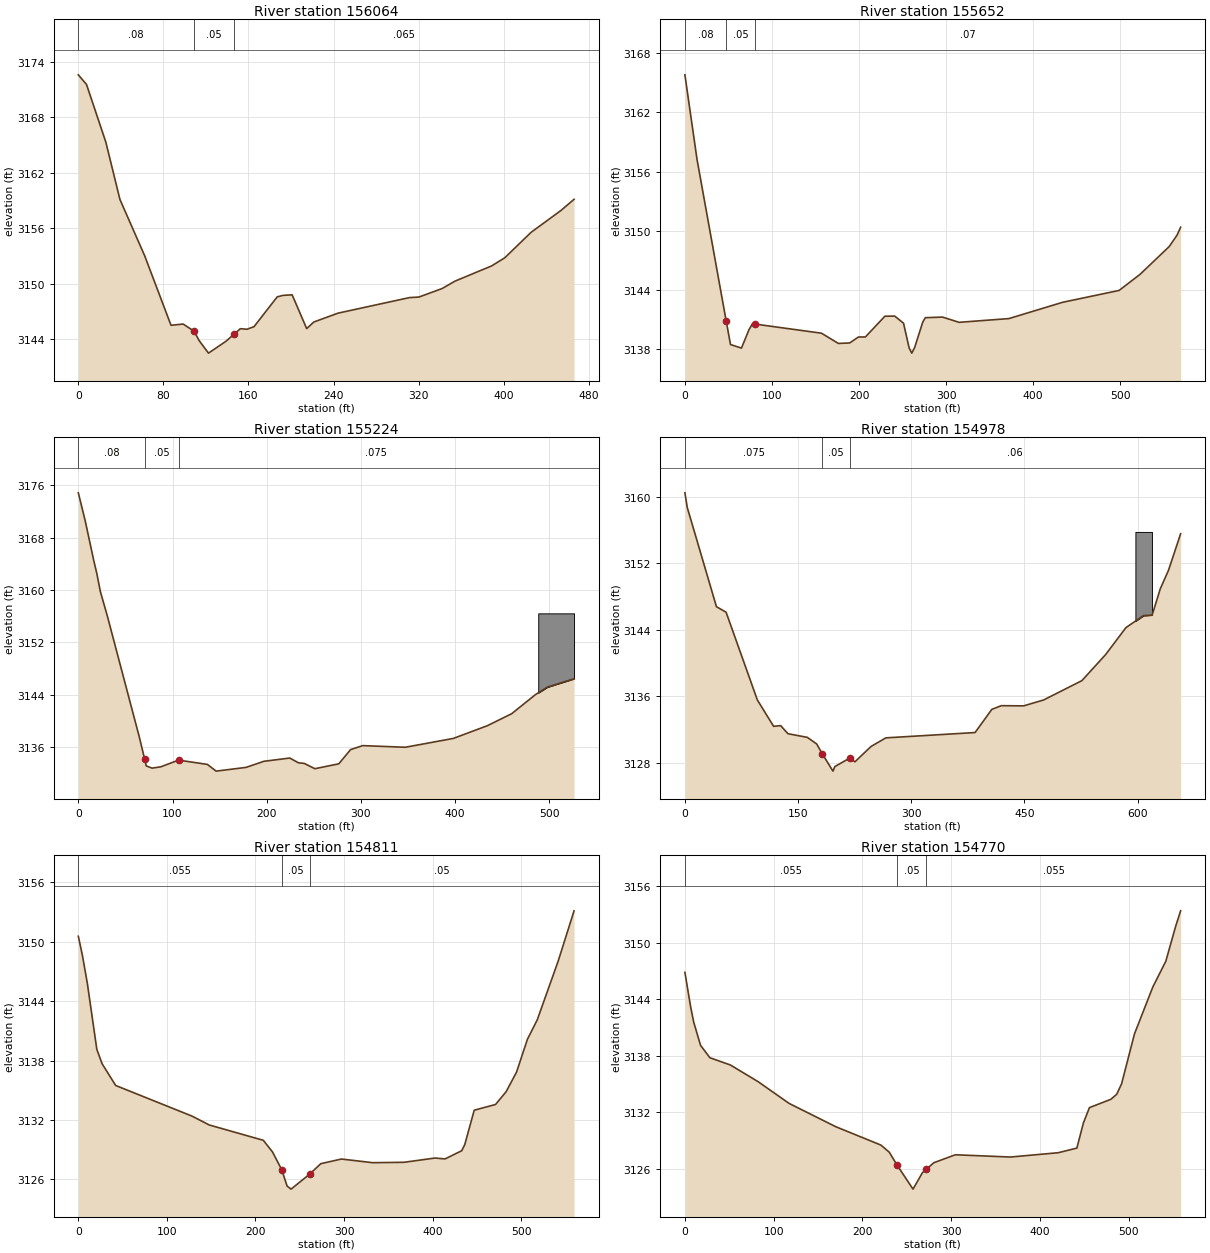
Type RM Length L Ch R = 1 ,156064  ,449.82,412.1,444.03
BEGIN DESCRIPTION:
155986.4
END DESCRIPTION:
XS GIS Cut Line= 6
  957211.3208197  804896.2891891  957148.1261119  804957.0525039
   957122.605704  804989.8650422  957105.5910746  805022.6775804
  957110.4528362  805138.1298246  957174.8622162  805310.6982942
#Sta/Elev= 30
       0 3172.58    7.71 3171.54   25.87 3165.31   39.12 3159.12   62.51    3153
   87.16 3145.52   98.63 3145.65  108.85 3144.88  113.61 3143.87  122.39 3142.51
  138.84 3143.79   146.2 3144.53  152.36 3145.15  158.64 3145.09  165.24 3145.37
  187.05 3148.59  192.52 3148.75  201.08 3148.81  214.76 3145.16  221.43 3145.87
  244.29 3146.83  311.42 3148.51  320.34 3148.57  342.17 3149.49  354.26 3150.29
  388.62 3151.93  401.05 3152.81  425.77 3155.56  453.84 3157.92   466.2 3159.13
#Mann= 3 , 0 , 0
       0     .08       0  108.85     .05       0   146.2    .065       0
Bank Sta=108.85,146.2
Exp/Cntr=0.3,0.1

Type RM Length L Ch R = 1 ,155652  ,420.26,427.8,484.48
BEGIN DESCRIPTION:
155574.3
END DESCRIPTION:
XS GIS Cut Line= 6
  956788.4038877  804727.3657604  956775.0363476  804775.9762075
  956738.5777442  804833.0944813  956702.1191408  804929.1017273
  956708.1955747  805083.4419194  956758.0217182  805270.5946498
#Sta/Elev= 30
       0  3165.8   13.98  3157.2    47.53140.822   52.37 3138.48   64.97 3138.12
   73.59 3139.99   77.37 3140.55   79.93 3140.56   156.8 3139.63  176.29 3138.59
  189.22 3138.64  199.23 3139.24  207.28 3139.25  229.69 3141.35  241.01 3141.36
  251.08 3140.64  257.52 3138.13  260.53 3137.61   263.8 3138.17  273.14 3140.75
  276.12  3141.2   295.9 3141.26  314.88 3140.73  372.11 3141.11  433.81 3142.76
  498.63 3143.96  522.68 3145.59  556.21 3148.41  565.08 3149.55  569.28 3150.36
#Mann= 3 , 0 , 0
       0     .08       0    47.5     .05       0   79.93     .07       0
Bank Sta=47.5,79.93
Exp/Cntr=0.3,0.1

Type RM Length L Ch R = 1 ,155224  ,215.12,246.55,139.75
BEGIN DESCRIPTION:
155146.5
END DESCRIPTION:
XS GIS Cut Line= 6
  956401.9455592  804579.1020022  956375.2094548  804638.6506448
  956344.8272853  804682.4003544  956308.3697061  804729.7961292
  956281.6336017  804807.5740734  956226.9456966  805067.6429865
#Sta/Elev= 30
       0 3174.86    7.27 3170.61   16.36 3164.52   19.63 3162.53   23.33  3159.8
   30.94 3155.95   64.91 3137.43   70.29 3134.21   72.09  3133.1   78.32 3132.76
   87.56 3132.96  106.38 3133.98  137.02 3133.33  146.31  3132.3  178.06 3132.87
  196.97  3133.8  224.51  3134.3  233.79 3133.57  239.91 3133.48  251.15 3132.67
  276.56 3133.42  289.05 3135.59  301.95  3136.2   347.2 3135.95  398.16  3137.3
  434.35 3139.25   460.1 3141.08  485.28 3143.99  497.83 3145.14  526.34 3146.43
#Mann= 3 , 0 , 0
       0     .08       0   70.29     .05       0  106.38    .075       0
#Block Obstruct= 1 ,-1
  488.31  526.343156.428
Bank Sta=70.29,106.38
Exp/Cntr=0.3,0.1

Type RM Length L Ch R = 1 ,154978  ,164.43,167,254.69
BEGIN DESCRIPTION:
154899.9
END DESCRIPTION:
XS GIS Cut Line= 6
  956259.7582349  804504.9701231  956172.2577915  804536.5669649
  956129.7237784  804582.7470432  956139.4452533   804675.108224
  956111.4944766  805005.6639752  956065.3133741  805061.5665526
#Sta/Elev= 30
       0 3160.49    3.12 3158.73   41.78  3146.8    54.6 3146.13   95.96 3135.59
  117.52 3132.41  126.95 3132.49  136.52 3131.52  162.24 3131.08  174.58 3130.29
  182.29 3129.07  196.19 3127.02  198.72 3127.57  218.43 3128.59   225.3 3128.14
  246.57 3129.98  266.23 3131.02  384.52 3131.66  406.71 3134.45  419.31 3134.89
  448.99 3134.87  475.41 3135.58  526.02  3137.9  557.44 3141.03  584.44 3144.28
  607.57 3145.72  619.16 3145.79  629.98 3148.96  640.81 3151.17  656.89 3155.57
#Mann= 3 , 0 , 0
       0    .075       0  182.29     .05       0  218.43     .06       0
#Block Obstruct= 1 ,-1
  596.96  618.853155.788
Bank Sta=182.29,218.43
Exp/Cntr=0.3,0.1

Type RM Length L Ch R = 1 ,154811  ,40.86,41.24,39.38
BEGIN DESCRIPTION:
154732.9
END DESCRIPTION:
XS GIS Cut Line= 6
  956095.6955437  804393.1639441  956013.0568619  804501.3240579
  955983.8903889  804560.8727005  955970.5218246  804611.9145405
   955926.772115  804734.6568666  955841.7030645    804886.56669
#Sta/Elev= 30
       0 3150.56    4.53 3148.67   10.17 3145.81   20.89 3139.14    26.8 3137.69
   42.15 3135.49  128.48 3132.39   147.8  3131.5  208.87 3129.95  219.25 3128.77
  229.68 3126.97  235.68 3125.33  240.13 3125.02  260.98 3126.52   273.7 3127.59
     297 3128.06  332.38 3127.69  367.55 3127.73  402.72 3128.16  413.99 3128.07
   432.8  3128.9  436.25 3129.52  446.92 3132.99  470.99 3133.57  482.86 3134.85
  494.66 3136.83  507.01 3140.16  518.08 3142.12   541.7 3148.05  559.62 3153.13
#Mann= 3 , 0 , 0
       0    .055       0  229.68     .05       0  260.98     .05       0
Bank Sta=229.68,260.98
Exp/Cntr=0.3,0.1

Type RM Length L Ch R = 1 ,154770  ,212.72,264.13,244.76
BEGIN DESCRIPTION:
154691.7
END DESCRIPTION:
XS GIS Cut Line= 6
  956051.9458341  804367.6435362  956021.5636646  804408.9628771
  955935.2789176   804575.455937  955917.0496159  804664.1710527
  955848.9941707  804794.2055092  955806.4591334  804864.6923473
#Sta/Elev= 30
       0 3146.84    6.56 3143.13    9.91 3141.56   17.62 3139.09   28.16 3137.77
   51.29    3137   82.45 3135.23  117.55 3132.91   169.8 3130.45  220.85 3128.49
  230.31 3127.73  238.81  3126.4  257.03 3123.81  267.65 3125.56  271.98  3125.9
  280.31 3126.61  304.68 3127.46  366.84 3127.22   420.7 3127.68  441.62 3128.17
  449.04 3130.85  455.81 3132.47  479.86 3133.35  486.56 3133.89  492.07 3135.01
  506.54  3140.3  527.19 3145.28  541.88 3148.03  553.03 3151.76  558.55 3153.38
#Mann= 3 , 0 , 0
       0    .055       0  238.81     .05       0  271.98    .055       0
Bank Sta=238.81,271.98
Exp/Cntr=0.3,0.1

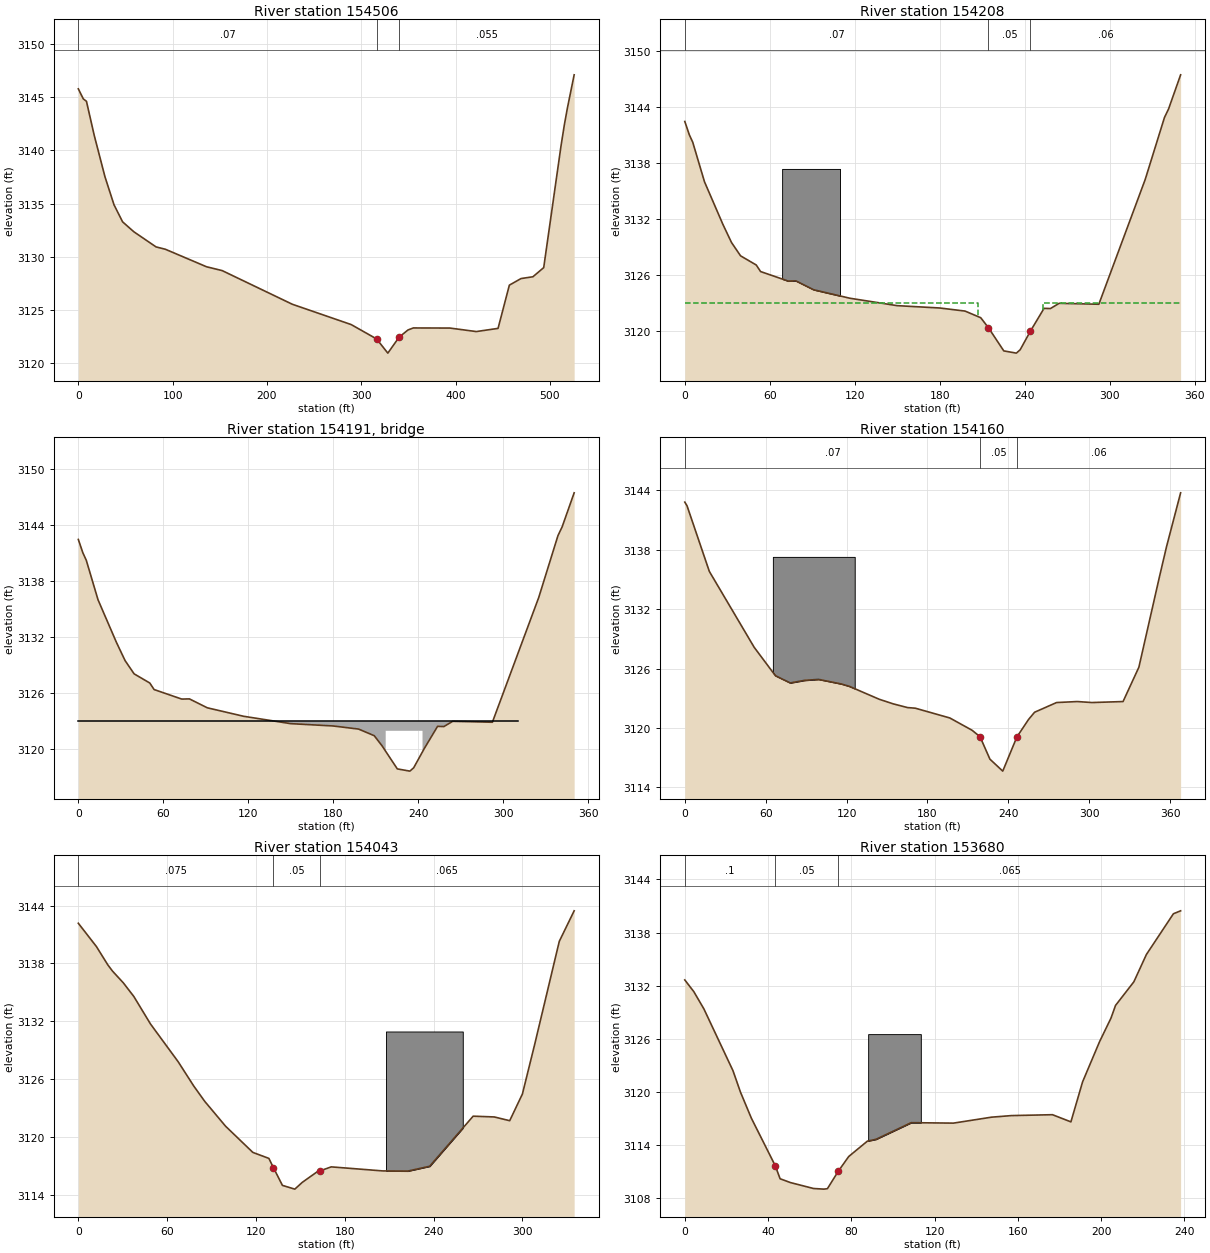
Type RM Length L Ch R = 1 ,154506  ,382.8,297.37,264.21
BEGIN DESCRIPTION:
154427.6
END DESCRIPTION:
XS GIS Cut Line= 6
  955857.5009734  804291.0802642  955848.9941707  804332.4006293
  955755.4183176  804406.5325084  955683.7168072  804502.5387302
  955637.5357047  804665.3867491  955607.1535352  804732.2264979
#Sta/Elev= 30
       0  3145.8    5.32 3144.85    8.61 3144.63   16.86 3141.42   28.29 3137.51
   37.82 3134.89   46.93 3133.28   58.94 3132.34   82.41 3130.92   92.26  3130.7
  135.96 3129.05  152.52 3128.69  226.94 3125.52  289.31 3123.61  316.26 3122.26
   328.2 3120.92  340.24 3122.43  349.59  3123.1   355.2 3123.29  394.08 3123.28
  422.04 3122.95  445.09 3123.25  457.07 3127.32  469.46 3127.94  482.07 3128.11
  493.51 3128.97  511.83 3140.41  515.31 3142.37   518.6 3143.98  525.79 3147.12
#Mann= 3 , 0 , 0
       0     .07       0  316.26     .05       0  340.24    .055       0
Bank Sta=316.26,340.24
Exp/Cntr=0.5,0.3

Type RM Length L Ch R = 1 ,154208  ,40.42,48.01,42.2
BEGIN DESCRIPTION:
154130.2
END DESCRIPTION:
XS GIS Cut Line= 6
  955438.2301066  804308.0948937  955409.0636335  804408.9628771
  955393.2647005  804517.1219667  955376.2510953  804548.7198327
  955376.2510953  804583.9627397  955373.8207266  804648.3721197
#Sta/Elev= 30
       0 3142.47    3.23 3141.03     5.6 3140.25   13.89 3136.02   26.91 3131.45
   32.99 3129.51   39.37 3128.09   50.42 3127.11   53.48 3126.41   72.97 3125.39
   78.39 3125.41   90.94 3124.46  116.61 3123.55  149.86 3122.76  179.89 3122.51
  197.75 3122.18  208.82 3121.47  214.31 3120.39   225.1 3117.92  233.97 3117.68
  236.66 3118.04  243.92 3120.04  253.51 3122.47  258.01 3122.45  264.17 3123.01
  292.18 3122.91  324.89 3136.26  338.48 3142.89  341.39 3143.81  349.89 3147.46
#Mann= 3 , 0 , 0
       0     .07       0  214.31     .05       0  243.92     .06       0
#XS Ineff= 2 , 0
       0  206.88    3123  252.88       0    3123
Permanent Ineff=
       F       F
#Block Obstruct= 1 ,-1
   68.68  109.553137.391
Bank Sta=214.31,243.92
Exp/Cntr=0.5,0.3

Type RM Length L Ch R = 3 ,154191  ,,,
BEGIN DESCRIPTION:
154108  FBSTR_1238
END DESCRIPTION:
Bridge Culvert--1,0,-1,-1, 0
Deck Dist Width WeirC Skew NumUp NumDn MinLoCord MaxHiCord MaxSubmerge Is_Ogee
11,26,2.6,0, 7, 7, , , 0.95, 0, 1,1,,
       0  216.88  216.88  229.88  242.88  242.88     310
    3123    3123    3123    3123    3123    3123    3123
                    3122    3122    3122
       0  222.83  222.83  235.83  248.83  248.83     350
    3123    3123    3123    3123    3123    3123    3123
                    3122    3122    3122
BR Coef=-1 , 0 , 0 ,, 0 ,,,0.8,0,,0,
WSPro=,,,, 1 ,,,, 0 ,,,, 0 ,,,,-1 ,-1 ,-1 , 0 , 0 , 0 , 0 , 0
BC Design=,, 0 ,, 0 ,,,,,,

Type RM Length L Ch R = 1 ,154160  ,180.12,117.1,60.7
BEGIN DESCRIPTION:
154082.2
END DESCRIPTION:
XS GIS Cut Line= 6
    955410.27933   804289.865592  955387.1882666  804349.4142345
  955344.6542535  804496.4622963  955336.1474509  804528.0601623
  955328.8553205  804580.3166745  955339.7924919  804644.7260545
#Sta/Elev= 30
       0 3142.82    1.66 3142.45    18.2 3135.82   51.47 3128.15   67.23 3125.28
   78.23 3124.55   88.76 3124.81   99.21 3124.91  116.34 3124.44  122.16  3124.2
  144.24  3122.9  154.75 3122.43  165.26 3122.06  170.95    3122   196.6 3121.01
  213.07 3119.77  218.97 3119.12  226.31 3116.85  235.83 3115.64   246.3 3119.09
  254.96 3120.86  259.44 3121.59  275.76 3122.57  291.18 3122.67  301.96 3122.57
  325.06 3122.67   336.8 3126.14  351.93  3135.2  357.31 3138.32  367.76 3143.76
#Mann= 3 , 0 , 0
       0     .07       0  218.97     .05       0   246.3     .06       0
#XS Ineff= 2 , 0
       0  207.83    3120  263.83       0    3120
Permanent Ineff=
       F       F
#Block Obstruct= 1 ,-1
   65.33  126.033137.288
Bank Sta=218.97,246.3
Exp/Cntr=0.5,0.3

Type RM Length L Ch R = 1 ,154043  ,399,363.33,230.16
BEGIN DESCRIPTION:
153965.1
END DESCRIPTION:
XS GIS Cut Line= 4
  955170.8690632  804346.9838658  955209.7580354  804430.8372198
   955234.063771  804498.8936892  955287.5359796  804660.5249875
#Sta/Elev= 30
       0 3142.17   12.19 3139.76   19.93 3137.85   23.11  3137.2   30.32    3136
    37.5 3134.57   48.74 3131.72   67.44  3127.8   78.06 3125.26   85.44 3123.68
   99.47 3121.11   117.9 3118.39  128.72 3117.77  131.743116.824  137.87 3114.97
  146.24 3114.58  151.27 3115.28  161.45 3116.39  163.55 3116.49  170.86 3116.89
  205.62 3116.47  222.53 3116.45  237.33 3116.95  266.72 3122.15     281 3122.07
  291.41 3121.68  299.99 3124.45  308.24 3129.57   324.9 3140.29  334.95 3143.46
#Mann= 3 , 0 , 0
       0    .075       0  131.74     .05       0  163.55    .065       0
#Block Obstruct= 1 ,-1
  207.81   259.73130.939
Bank Sta=131.74,163.55
Exp/Cntr=0.3,0.1

Type RM Length L Ch R = 1 ,153680  ,182.84,175.3,178.74
BEGIN DESCRIPTION:
153601.8
END DESCRIPTION:
XS GIS Cut Line= 3
  954887.7090869  804670.2474866  954955.7655562    804706.70609
  955111.3204206  804748.0254309
#Sta/Elev= 30
       0 3132.65    4.33 3131.33    9.18 3129.38   23.14 3122.41   26.74 3119.99
   31.95 3117.06   43.43 3111.69   45.78 3110.21   50.74 3109.78   61.85 3109.11
   66.81 3109.04    68.5 3109.09   73.79 3111.08   78.73 3112.72   87.72 3114.46
   91.83 3114.66  108.76 3116.54  129.07 3116.49  147.31 3117.16  156.93 3117.34
   176.6 3117.44  185.46 3116.63  191.06 3121.14  199.24 3125.69  204.69 3128.33
  206.89 3129.77   215.7 3132.44  221.72 3135.52   234.7 3140.12  238.16 3140.45
#Mann= 3 , 0 , 0
       0      .1       0   43.43     .05       0   73.79    .065       0
#Block Obstruct= 1 ,-1
   88.07  113.373126.534
Bank Sta=43.43,73.79
Exp/Cntr=0.3,0.1

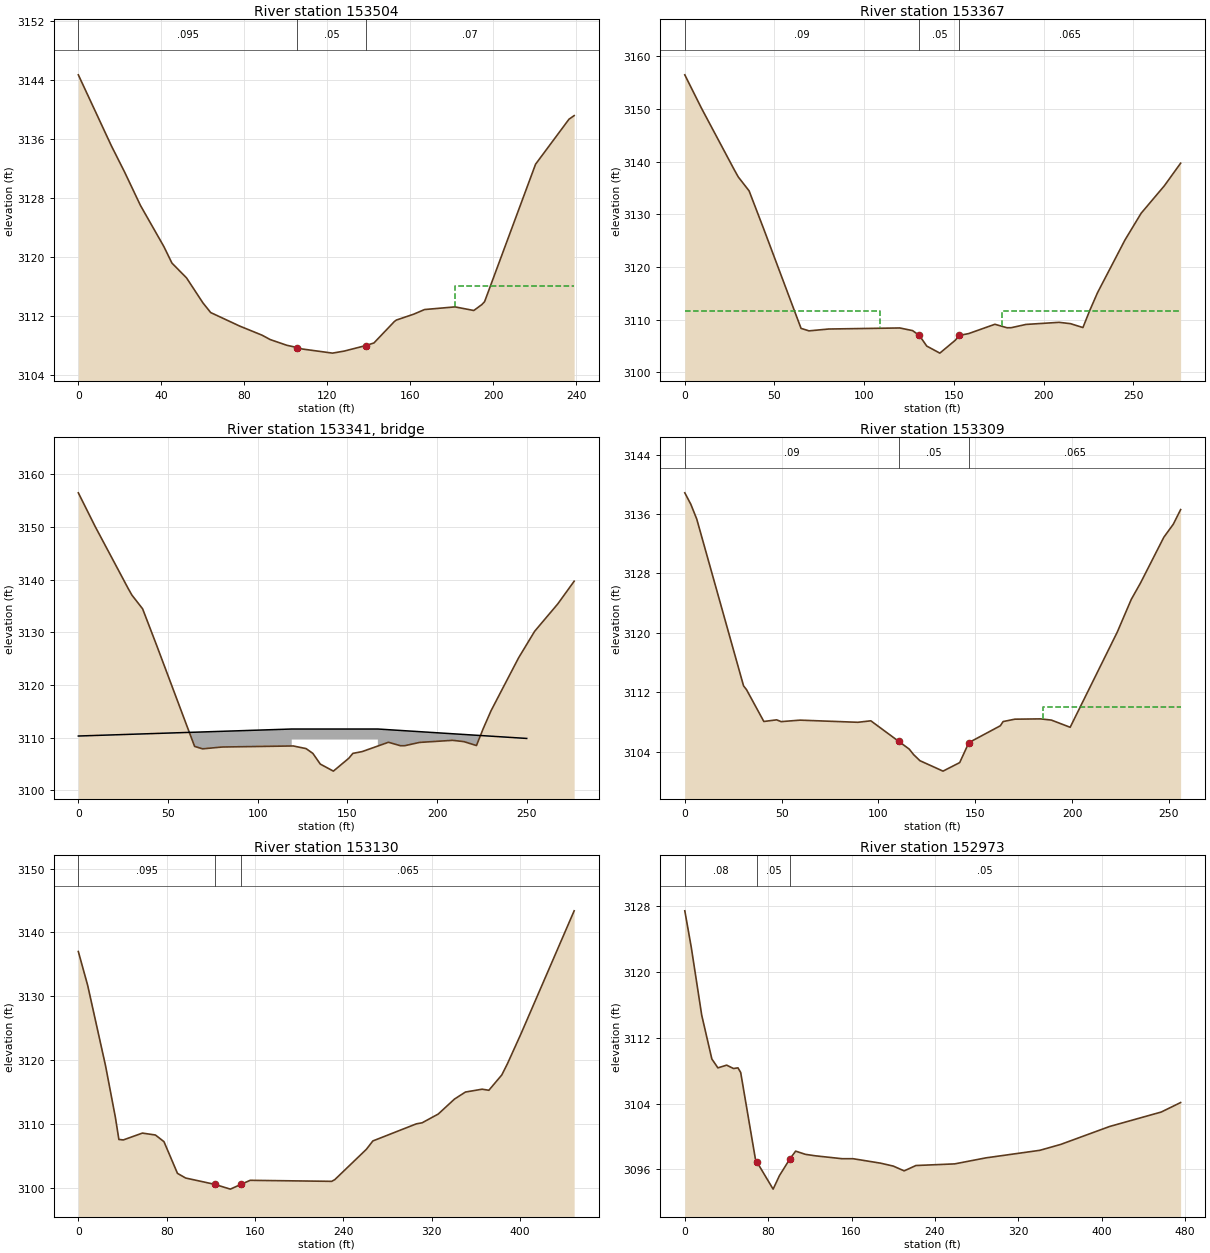
Type RM Length L Ch R = 1 ,153504  ,183,137.82,119.57
BEGIN DESCRIPTION:
153426.5
END DESCRIPTION:
XS GIS Cut Line= 4
  954807.5007738  804836.7405465  954881.6326529   804867.122716
  954941.1812955  804876.8441909  955033.5424763  804910.8724256
#Sta/Elev= 30
       0 3144.74    15.9 3135.11   22.37 3131.49   29.91 3127.01   41.22 3121.41
    45.1 3119.17   52.13 3117.16   60.07 3113.75   63.77 3112.45   77.69 3110.62
    88.5 3109.38   92.45 3108.78  100.52    3108  105.44  3107.7   107.9  3107.5
  122.46 3106.94  128.14 3107.22  138.53 3107.97  142.41 3108.32  152.22 3111.22
   153.2 3111.43  161.58 3112.23  166.81 3112.86  181.48 3113.22  190.53 3112.73
  194.43 3113.54  195.73 3113.93  220.29  3132.6  236.39 3138.71  238.88  3139.2
#Mann= 3 , 0 , 0
       0    .095       0  105.44     .05       0  138.53     .07       0
#XS Ineff= 2 , 0
       0                  181.49       0    3116
Permanent Ineff=
       F       F
Bank Sta=105.44,138.53
Exp/Cntr=0.5,0.3

Type RM Length L Ch R = 1 ,153367  ,35.55,57.47,46.19
BEGIN DESCRIPTION:
153288.6
END DESCRIPTION:
XS GIS Cut Line= 6
  954732.1542225  804989.8650422  954780.7646695  805022.6775804
  954825.7300755  805025.1089733  954897.4315859  805000.8032377
  954936.3205581  804999.5875413  954988.5780945  805025.1089733
#Sta/Elev= 30
       0 3156.49    9.39 3150.09   27.84 3138.29   29.86 3137.07   35.85 3134.45
   43.95 3127.26   64.82 3108.32   69.27 3107.85    80.2  3108.2  119.88  3108.4
  126.97  3107.9  130.76 3106.99   134.9 3104.96   142.2 3103.62  150.85 3106.08
  153.06 3106.99  158.24 3107.33   172.9  3109.1  179.66 3108.44  181.99 3108.45
   190.2 3109.07  208.67 3109.47  215.03 3109.22  221.98 3108.48  225.68 3111.64
  230.13 3115.11  245.43 3125.12  254.43 3130.19  267.37 3135.41  276.45  3139.7
#Mann= 3 , 0 , 0
       0     .09       0  130.76     .05       0  153.06    .065       0
#XS Ineff= 2 , 0
       0     109 3111.62     177       0 3111.62
Permanent Ineff=
       F       F
Bank Sta=130.76,153.06
Exp/Cntr=0.5,0.3

Type RM Length L Ch R = 3 ,153341  ,,,
BEGIN DESCRIPTION:
153261  FBSTR_1239
END DESCRIPTION:
Bridge Culvert--1,0,-1,-1, 0
Deck Dist Width WeirC Skew NumUp NumDn MinLoCord MaxHiCord MaxSubmerge Is_Ogee
11.5,33,2.6,0, 6, 6, , , 0.95, 0, 1,1,,
       0     119     119     167     167     250
 3110.29 3111.62 3111.62 3111.62 3111.62 3109.83
                 3109.62 3109.62
       0     110     110     158     158     250
 3110.29 3111.62 3111.62 3111.62 3111.62 3109.83
                 3109.62 3109.62
BR Coef=-1 , 0 , 0 ,, 0 ,,,0.8,0,,0,
WSPro=,,,, 1 ,,,, 0 ,,,, 0 ,,,,-1 ,-1 ,-1 , 0 , 0 , 0 , 0 , 0
BC Design=,, 0 ,, 0 ,,,,,,

Type RM Length L Ch R = 1 ,153309  ,56.51,179.02,261.02
BEGIN DESCRIPTION:
153231.2
END DESCRIPTION:
XS GIS Cut Line= 5
  954738.2306564  805028.7540143  954774.6882356  805063.9969213
  954813.5772077  805071.2890516  954899.8619547  805045.7686438
  954975.2095302  805054.2754464
#Sta/Elev= 30
       0 3138.86    3.09 3137.33    6.17 3135.33   30.35 3112.85   31.89 3112.33
   40.82 3108.05   47.45 3108.27   49.74 3108.03   59.53 3108.23   89.39 3107.94
   96.08 3108.14  110.44 3105.38   115.9 3104.33  118.16 3103.59  121.42 3102.77
  133.36 3101.36  141.98 3102.51   146.7  3105.2  162.96 3107.47  164.41 3108.04
  170.46 3108.36  183.74  3108.4  189.29 3108.24  199.03 3107.27  223.37  3120.1
  230.57 3124.49  235.38 3126.72  247.42 3132.88  252.32 3134.64  256.08  3136.6
#Mann= 3 , 0 , 0
       0     .09       0  110.44     .05       0   146.7    .065       0
#XS Ineff= 3 ,-1
       0      95 3107.75     173  185.19 3107.75  185.19  256.08    3110
Permanent Ineff=
       F       F       F
Bank Sta=110.44,146.7
Exp/Cntr=0.5,0.3

Type RM Length L Ch R = 1 ,153130  ,117.5,157.05,420.84
BEGIN DESCRIPTION:
153052.2
END DESCRIPTION:
XS GIS Cut Line= 6
  954704.2024217  805037.2608169  954732.1542225  805181.8795342
  954757.6746303  805234.1360464  954840.3133121  805287.6082551
  954896.2169137  805305.8375568  954981.2859641  805292.4700167
#Sta/Elev= 30
       0    3137    8.49 3131.68   24.64  3119.1   33.48 3111.08   36.72 3107.55
   40.75 3107.48   57.98 3108.55   69.79 3108.25   77.52 3107.21   89.75 3102.24
   97.14 3101.51  123.43 3100.52  137.61 3099.77  147.67 3100.55  155.57 3101.15
  229.34 3100.99  232.18 3101.26  260.75 3106.01  266.62 3107.32  306.01    3110
  311.17 3110.16  325.77 3111.53   340.5 3113.88  350.37 3114.98  365.54 3115.43
  371.62 3115.26  383.32 3117.66  388.39  3119.4  400.78 3124.14  448.84 3143.38
#Mann= 3 , 0 , 0
       0    .095       0  123.43     .05       0  147.67    .065       0
Bank Sta=123.43,147.67
Exp/Cntr=0.3,0.1

Type RM Length L Ch R = 1 ,152973  ,256.26,289.83,445.29
BEGIN DESCRIPTION:
152895.1
END DESCRIPTION:
XS GIS Cut Line= 5
  954602.1187418  805051.8450777  954575.3826374  805149.0669959
  954531.6329278  805302.1914916  954517.0496913  805393.3380001
  954553.5082947  805511.2195888
#Sta/Elev= 30
       0 3127.44    6.22    3123   16.25 3114.74   25.96 3109.42   31.77 3108.34
   40.17 3108.67   46.73 3108.26   51.02 3108.34   53.63 3107.78   67.73 3097.27
   69.29 3096.87   84.76 3093.59   90.85 3095.24  100.91 3097.28  106.36 3098.21
  115.77 3097.82  125.45 3097.64  150.91 3097.29  161.43 3097.29  187.76 3096.75
  200.13 3096.39  210.49 3095.81  221.74 3096.46     259 3096.66  288.82 3097.39
  340.68 3098.31  360.77 3099.03  407.65 3101.21  457.23 3102.97  475.78 3104.12
#Mann= 3 , 0 , 0
       0     .08       0   69.29     .05       0  100.91     .05       0
Bank Sta=69.29,100.91
Exp/Cntr=0.3,0.1

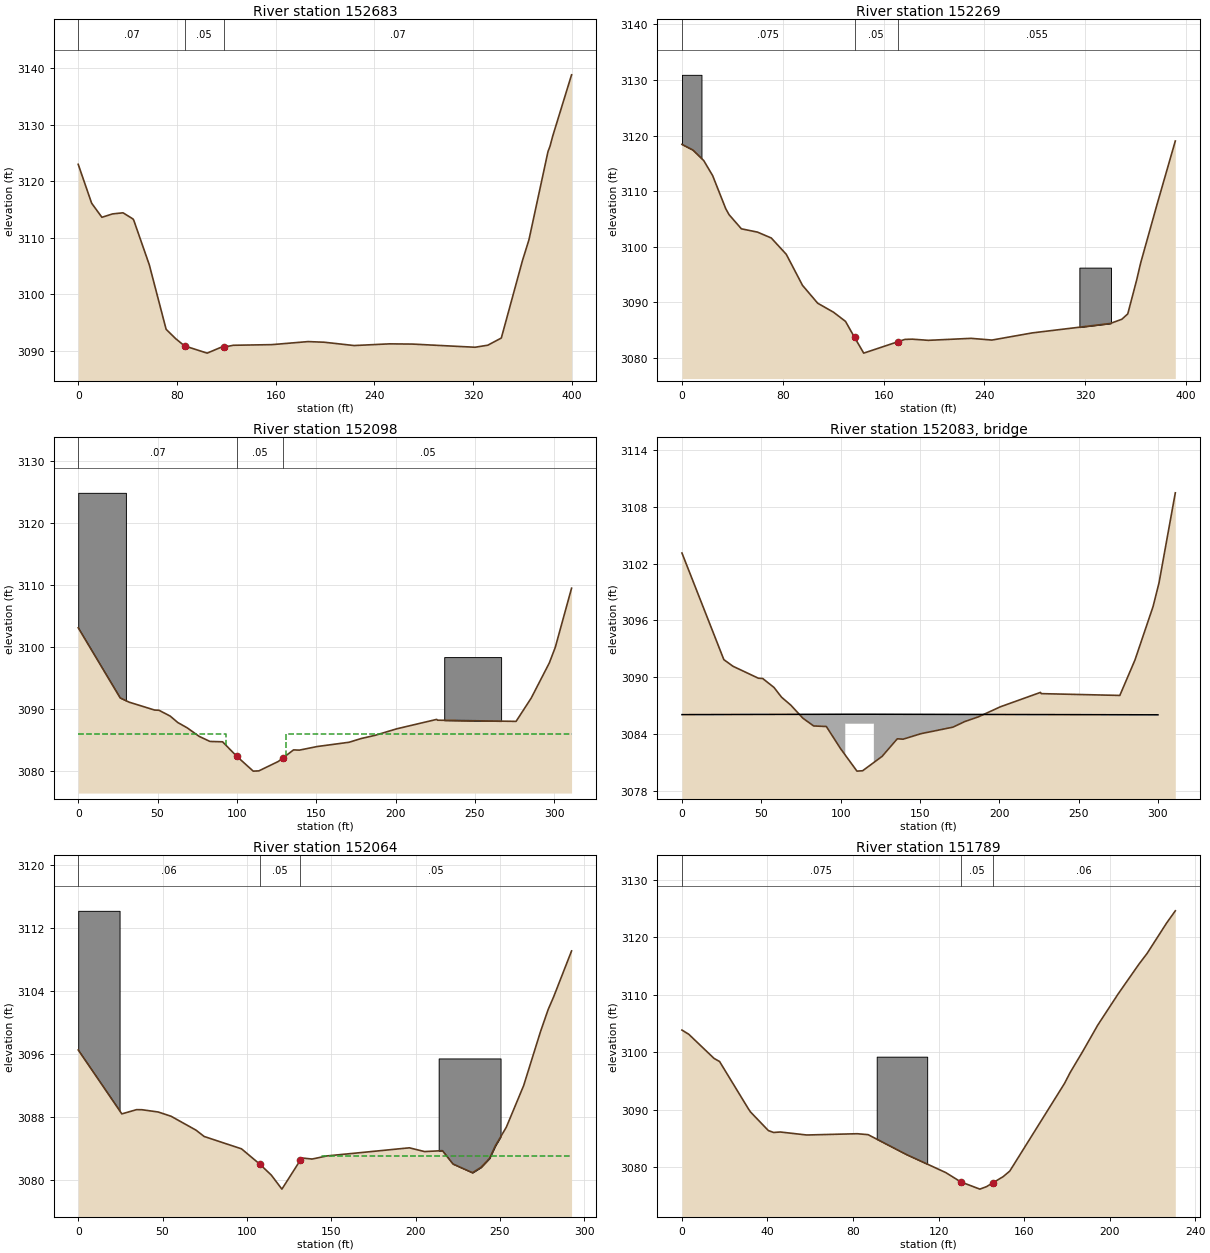
Type RM Length L Ch R = 1 ,152683  ,439.57,414.37,318.52
BEGIN DESCRIPTION:
152605.3
END DESCRIPTION:
XS GIS Cut Line= 4
  954384.5848661  804969.2053717  954298.3001192  805049.4136848
  954196.2164393  805147.8512995  954061.3202211  805185.5255993
#Sta/Elev= 30
       0 3122.97   10.88 3116.09    19.2  3113.6   27.91  3114.2   36.31 3114.39
   44.35 3113.31   44.99 3113.09    57.6 3105.19   71.23 3093.78   79.06 3092.11
   86.15 3090.85  104.47 3089.57  115.25 3090.56  117.81 3090.63  125.72 3090.96
  156.77 3091.07  186.26 3091.61  199.18  3091.5  223.55 3090.91  252.12 3091.21
   270.7 3091.17  321.46 3090.61   331.8 3090.97  342.77 3092.24   359.9 3105.94
  365.16 3109.62  380.59 3125.23  382.16 3126.12  384.53 3128.05  399.68  3138.8
#Mann= 3 , 0 , 0
       0     .07       0   86.15     .05       0  117.81     .07       0
Bank Sta=86.15,117.81
Exp/Cntr=0.3,0.1

Type RM Length L Ch R = 1 ,152269  ,207.09,170.74,100.03
BEGIN DESCRIPTION:
152190.9
END DESCRIPTION:
XS GIS Cut Line= 5
  954051.5987462    804655.66425  953990.8344072  804778.4076004
  953976.2511707  804805.1437047  953930.0710923  804882.9206248
  953880.2439247  805006.8796716
#Sta/Elev= 30
       0 3118.42    8.58 3117.42   17.29 3115.51   24.37 3112.79   34.75 3106.85
   37.33 3105.79   47.17 3103.23   59.91 3102.64   70.88 3101.58    82.8 3098.64
   95.63 3093.07   107.7 3089.85  120.26 3088.23  129.78 3086.58  136.96  3083.7
  144.23 3080.87  171.24 3082.91   176.9 3083.34  182.81 3083.38  195.51 3083.17
   229.4 3083.53  245.95 3083.22  278.01 3084.51  339.81  3086.2  349.02 3086.96
  353.74 3087.93  360.77 3093.99  363.95 3097.07  376.91 3107.57  391.47 3119.03
#Mann= 3 , 0 , 0
       0    .075       0  136.96     .05       0  171.24    .055       0
#Block Obstruct= 2 ,-1
  315.35  340.423096.251       0   15.483130.932
Bank Sta=136.96,171.24
Exp/Cntr=0.5,0.3

Type RM Length L Ch R = 1 ,152098  ,45.51,34.17,49.25
BEGIN DESCRIPTION:
152020.2
END DESCRIPTION:
XS GIS Cut Line= 4
  953813.4041759  804648.3721197  953817.0502411  804779.6222727
  953821.9109785  804878.0598874  953795.1748742  804954.6221352
#Sta/Elev= 30
       0 3103.13    26.4 3091.85   32.13 3091.15   48.18 3089.88   50.89 3089.85
   57.99 3088.91   62.73 3087.88   68.63 3087.03   76.22 3085.65   83.01 3084.83
      91 3084.77   99.88 3082.45   110.3 3080.05  113.86 3080.09  126.15 3081.61
  129.29 3082.22  135.73 3083.47  139.41 3083.43  150.59 3084.01  170.76  3084.7
  178.35  3085.3  186.94  3085.8  200.72 3086.86  225.95 3088.38  226.47 3088.25
  275.98 3088.06  285.52 3091.81  296.95 3097.48   300.7 3099.99  310.95  3109.5
#Mann= 3 , 0 , 0
       0     .07       0   99.88     .05       0  129.29     .05       0
#XS Ineff= 2 , 0
       0   92.93 3086.07  130.93       0 3086.07
Permanent Ineff=
       F       F
#Block Obstruct= 2 ,-1
       0   30.063124.854  230.69  266.543098.407
Bank Sta=99.88,129.29
Exp/Cntr=0.5,0.3

Type RM Length L Ch R = 3 ,152083  ,,,
Node Photo=H:\PROJ\06-0741\CE\GIS\DATA\FRENCH_BROAD_RIVER\SHAPEFILES\survey_data\photos\FBSTR_1788.JPG
BEGIN DESCRIPTION:
152005  FBSTR_1788
END DESCRIPTION:
Bridge Culvert--1,0,-1,-1, 0
Deck Dist Width WeirC Skew NumUp NumDn MinLoCord MaxHiCord MaxSubmerge Is_Ogee
7,12,2.6,0, 7, 7, , , 0.95, 0, 1,1,,
       0  102.93  102.93  111.93  120.93  120.93     300
 3086.03 3086.07 3086.07 3086.07 3086.07 3086.07 3086.01
                 3085.07 3085.07 3085.07
       0   111.5   111.5   120.5   129.5   129.5     300
 3086.03 3086.07 3086.07 3086.07 3086.07 3086.07 3086.01
                 3085.07 3085.07 3085.07
BR Coef=-1 , 0 , 0 ,, 0 ,,,0.8,0,,0,
WSPro=,,,, 1 ,,,, 0 ,,,, 0 ,,,,-1 ,-1 ,-1 , 0 , 0 , 0 , 0 , 0
BC Design=,, 0 ,, 0 ,,,,,,

Type RM Length L Ch R = 1 ,152064  ,343.54,275.19,177.97
BEGIN DESCRIPTION:
151986.0
END DESCRIPTION:
XS GIS Cut Line= 5
  953755.0702056  804653.2338813   953772.084835  804709.1364587
  953785.4523751  804784.4830101  953773.2995073  804861.0462821
  953750.2094682    804937.60853
#Sta/Elev= 30
       0  3096.5   25.86 3088.36   34.59  3088.9   37.81 3088.89   47.44  3088.6
   55.03 3088.06   69.76  3086.3   74.69 3085.48   96.81 3083.91  107.65 3081.96
  114.45 3080.57  120.75 3078.78  131.75 3082.49  132.52 3082.75  138.61 3082.61
  147.56 3083.01  196.34 3084.04  205.32 3083.56  215.89 3083.68  222.15 3081.98
  233.71 3080.87  238.79 3081.56  243.77 3082.68  247.31 3084.31  253.78 3086.67
  264.06 3091.97  273.98  3098.8  278.56 3101.64   281.8 3103.25  292.45 3109.11
#Mann= 3 , 0 , 0
       0     .06       0  107.65     .05       0  131.75     .05       0
#XS Ineff= 2 , 0
       0    96.5    3083   144.5       0    3083
Permanent Ineff=
       F       F
#Block Obstruct= 2 ,-1
       0   24.523114.216  213.68  250.36 3095.42
Bank Sta=107.65,131.75
Exp/Cntr=0.5,0.3

Type RM Length L Ch R = 1 ,151789  ,214.81,218.04,207.8
BEGIN DESCRIPTION:
151710.8
END DESCRIPTION:
XS GIS Cut Line= 3
  953465.8348195  804845.2473491  953581.2860395  804946.1153326
  953633.5425517  805003.2336064
#Sta/Elev= 29
       0 3103.83    3.19  3103.1   15.02  3098.9   17.58 3098.37   30.99 3090.19
   32.07 3089.59   40.41 3086.36   42.86 3086.03   46.03 3086.11   58.31 3085.59
   81.95 3085.81   87.05 3085.65  105.02 3082.19  123.36 3079.06  130.38 3077.44
  139.32 3076.18  142.43 3076.61  145.47 3077.29  150.21 3078.35  153.31 3079.32
   178.9 3094.55  181.54 3096.45  187.65 3100.26  194.41 3104.67  203.96  3110.1
  213.77 3115.32   217.5 3117.14  226.67 3122.45  230.72 3124.56
#Mann= 3 , 0 , 0
       0    .075       0  130.38     .05       0  145.47     .06       0
#Block Obstruct= 1 ,-1
   91.07  114.683099.206
Bank Sta=130.38,145.47
Exp/Cntr=0.3,0.1

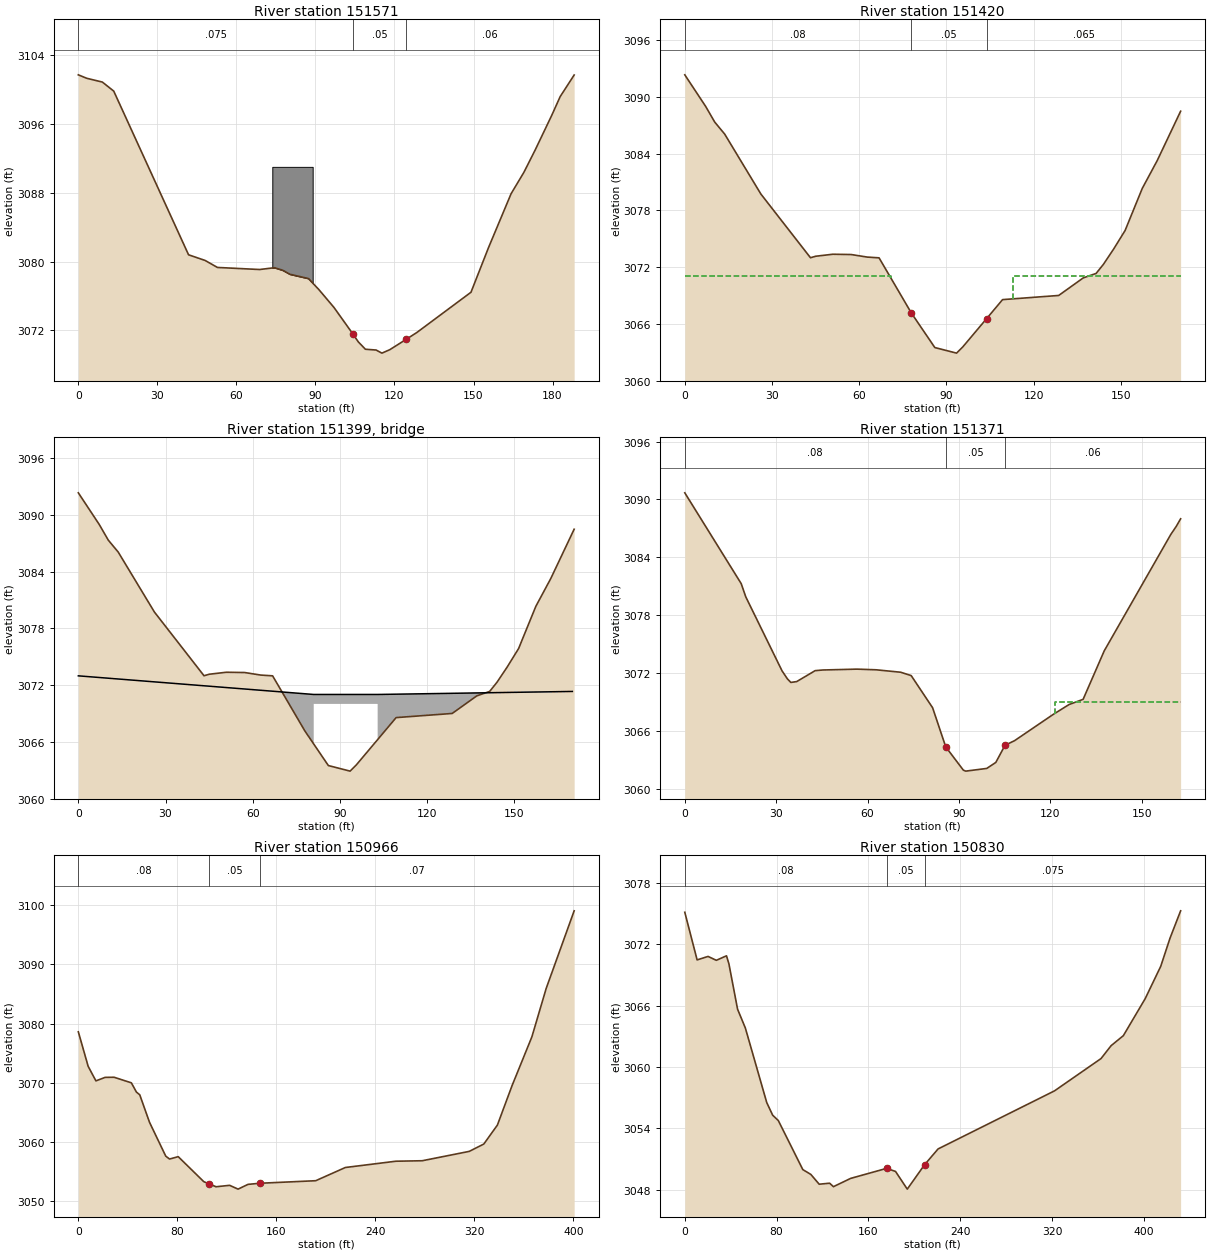
Type RM Length L Ch R = 1 ,151571  ,149.12,150.55,152.61
BEGIN DESCRIPTION:
151492.7
END DESCRIPTION:
XS GIS Cut Line= 3
  953332.1542978  805006.8796716  953409.9322421  805084.6576159
  953475.5562944   805127.191629
#Sta/Elev= 30
       0 3101.69    3.17 3101.29    9.11 3100.85   13.44  3099.8   41.84 3080.79
   48.14 3080.13    52.8 3079.32   68.84 3079.08   74.43 3079.29   77.59 3078.99
   80.28 3078.53   87.34 3078.03   91.33 3076.74   97.02 3074.68  104.16 3071.62
  106.26 3070.68  108.97 3069.82  113.02 3069.73  115.23 3069.37  118.23 3069.77
  124.38 3070.96  128.47 3071.76  149.04 3076.44  155.69 3081.62  164.26 3087.88
  169.13 3090.37  173.42 3092.97  179.78 3097.04  182.89 3099.16   188.2 3101.67
#Mann= 3 , 0 , 0
       0    .075       0  104.16     .05       0  124.38     .06       0
#Block Obstruct= 1 ,-1
   73.62   88.953091.004
Bank Sta=104.16,124.38
Exp/Cntr=0.5,0.3

Type RM Length L Ch R = 1 ,151420  ,48.72,49.12,48.99
BEGIN DESCRIPTION:
151342.2
END DESCRIPTION:
XS GIS Cut Line= 3
  953225.2098805  805107.7476551  953267.7438936  805153.9277334
  953350.3835995   805223.198875
#Sta/Elev= 26
       0 3092.35     7.2    3089    10.3 3087.35   13.73 3086.08   26.18 3079.74
   43.25    3073   45.06 3073.16   50.94 3073.37   57.25 3073.34   62.78 3073.07
   66.85 3072.99   77.93 3067.17   86.04  3063.5   93.52 3062.91   95.64 3063.56
  103.89 3066.57  109.35 3068.57  128.66 3069.01  137.12 3070.87  141.54 3071.34
  144.07 3072.31  147.55 3073.91  151.51 3075.88  157.43 3080.34  162.57 3083.28
  170.62  3088.5
#Mann= 3 , 0 , 0
       0     .08       0   77.93     .05       0  103.89    .065       0
#XS Ineff= 2 , 0
       0      71 3071.02     113       0 3071.02
Permanent Ineff=
       F       F
Bank Sta=77.93,103.89
Exp/Cntr=0.5,0.3

Type RM Length L Ch R = 3 ,151399  ,,,
Node Photo=H:\PROJ\06-0741\CE\GIS\DATA\FRENCH_BROAD_RIVER\SHAPEFILES\survey_data\photos\FBSTR_1787.JPG
BEGIN DESCRIPTION:
151321.2  FBSTR_1787
END DESCRIPTION:
Bridge Culvert--1,0,-1,-1, 0
Deck Dist Width WeirC Skew NumUp NumDn MinLoCord MaxHiCord MaxSubmerge Is_Ogee
14,13,2.6,0, 7, 7, , , 0.95, 0, 1,1,,
       0      81      81      92     103     103     170
 3072.99 3071.02 3071.02 3071.02 3071.02 3071.02 3071.34
                 3070.02 3070.02 3070.02
       0   84.42   84.42   95.42  106.42  106.42     170
  3072.1 3071.02 3071.02 3071.02 3071.02 3071.02 3071.34
                 3070.02 3070.02 3070.02
BR Coef=-1 , 0 , 0 ,, 0 ,,,0.8,0,,0,
WSPro=,,,, 1 ,,,, 0 ,,,, 0 ,,,,-1 ,-1 ,-1 , 0 , 0 , 0 , 0 , 0
BC Design=,, 0 ,, 0 ,,,,,,

Type RM Length L Ch R = 1 ,151371  ,425.94,405.16,255.39
BEGIN DESCRIPTION:
151293.1
END DESCRIPTION:
XS GIS Cut Line= 3
  953192.3973422  805145.4209307  953250.7302884  805203.7538769
  953312.7092997  805254.7957168
#Sta/Elev= 28
       0 3090.69   18.52 3081.28   20.02 3079.91   31.93 3072.24   33.69 3071.41
   34.82 3071.04   36.75 3071.13   42.79 3072.26   45.29 3072.33   56.51 3072.42
   62.82 3072.35   70.85  3072.1   74.33 3071.75   81.36 3068.42   85.68 3064.36
   91.46 3061.95   92.24 3061.85   99.14 3062.13  102.11 3062.75  105.14 3064.53
  108.29 3065.01  120.88 3067.71  126.16 3068.75  130.78 3069.29  137.72 3074.32
  159.57 3086.38  161.39 3087.23  162.79    3088
#Mann= 3 , 0 , 0
       0     .08       0   85.68     .05       0  105.14     .06       0
#XS Ineff= 2 , 0
       0   69.42    3069  121.42       0    3069
Permanent Ineff=
       F       F
Bank Sta=85.68,105.14
Exp/Cntr=0.5,0.3

Type RM Length L Ch R = 1 ,150966  ,96.8,135.51,235.12
BEGIN DESCRIPTION:
150887.9
END DESCRIPTION:
XS GIS Cut Line= 6
  952894.6541294  805456.5316837  952952.9870755  805502.7127862
  952996.7378093  805513.6499576  953113.4037015  805513.6499576
  953227.6402492  805478.4070506  953270.1752865  805463.8238141
#Sta/Elev= 30
       0 3078.63    7.94 3072.81   14.21 3070.35   21.64 3070.94   28.93 3070.96
   42.86 3070.02   46.94 3068.46   49.64    3068   57.51 3063.37   70.64 3057.65
   73.72 3057.16   80.73 3057.56  101.38 3053.34  105.98 3052.94  111.29 3052.48
  122.28 3052.72   129.1 3052.08  137.08 3052.88  146.64 3053.07  191.85  3053.5
  215.78 3055.73  256.66 3056.79   277.9 3056.87   315.9 3058.45  327.67 3059.69
  338.65 3062.89  350.47 3069.53  366.52 3077.78  378.06 3085.94  400.68 3099.05
#Mann= 3 , 0 , 0
       0     .08       0  105.98     .05       0  146.64     .07       0
Bank Sta=105.98,146.64
Exp/Cntr=0.3,0.1

Type RM Length L Ch R = 1 ,150830  ,48.11,126.43,341.69
BEGIN DESCRIPTION:
150752.4
END DESCRIPTION:
XS GIS Cut Line= 6
  952829.0290529  805523.3724566  952905.5913007  805592.6435983
  952946.9106416  805629.1011775  952990.6613754  805654.6226096
  953125.5565693  805678.9283452  953199.6884484  805722.6780548
#Sta/Elev= 30
       0 3075.12   10.74 3070.46   20.27  3070.8   27.48 3070.42   36.35 3070.86
   38.48 3070.06   45.99 3065.64   52.78  3063.8   71.42 3056.51   76.59 3055.27
    81.5 3054.75  102.86 3049.95  109.85 3049.48  117.13 3048.52  126.22 3048.62
  129.56 3048.28  144.56 3049.09  175.88 3050.07  183.67 3049.77  193.91 3048.04
     209 3050.43  220.75 3051.97  322.22 3057.65  362.78 3060.81  371.56 3062.07
  382.23 3063.05  401.27 3066.67  414.81 3069.83  422.86 3072.57  432.15 3075.26
#Mann= 3 , 0 , 0
       0     .08       0  175.88     .05       0     209    .075       0
Bank Sta=175.88,209
Exp/Cntr=0.3,0.1