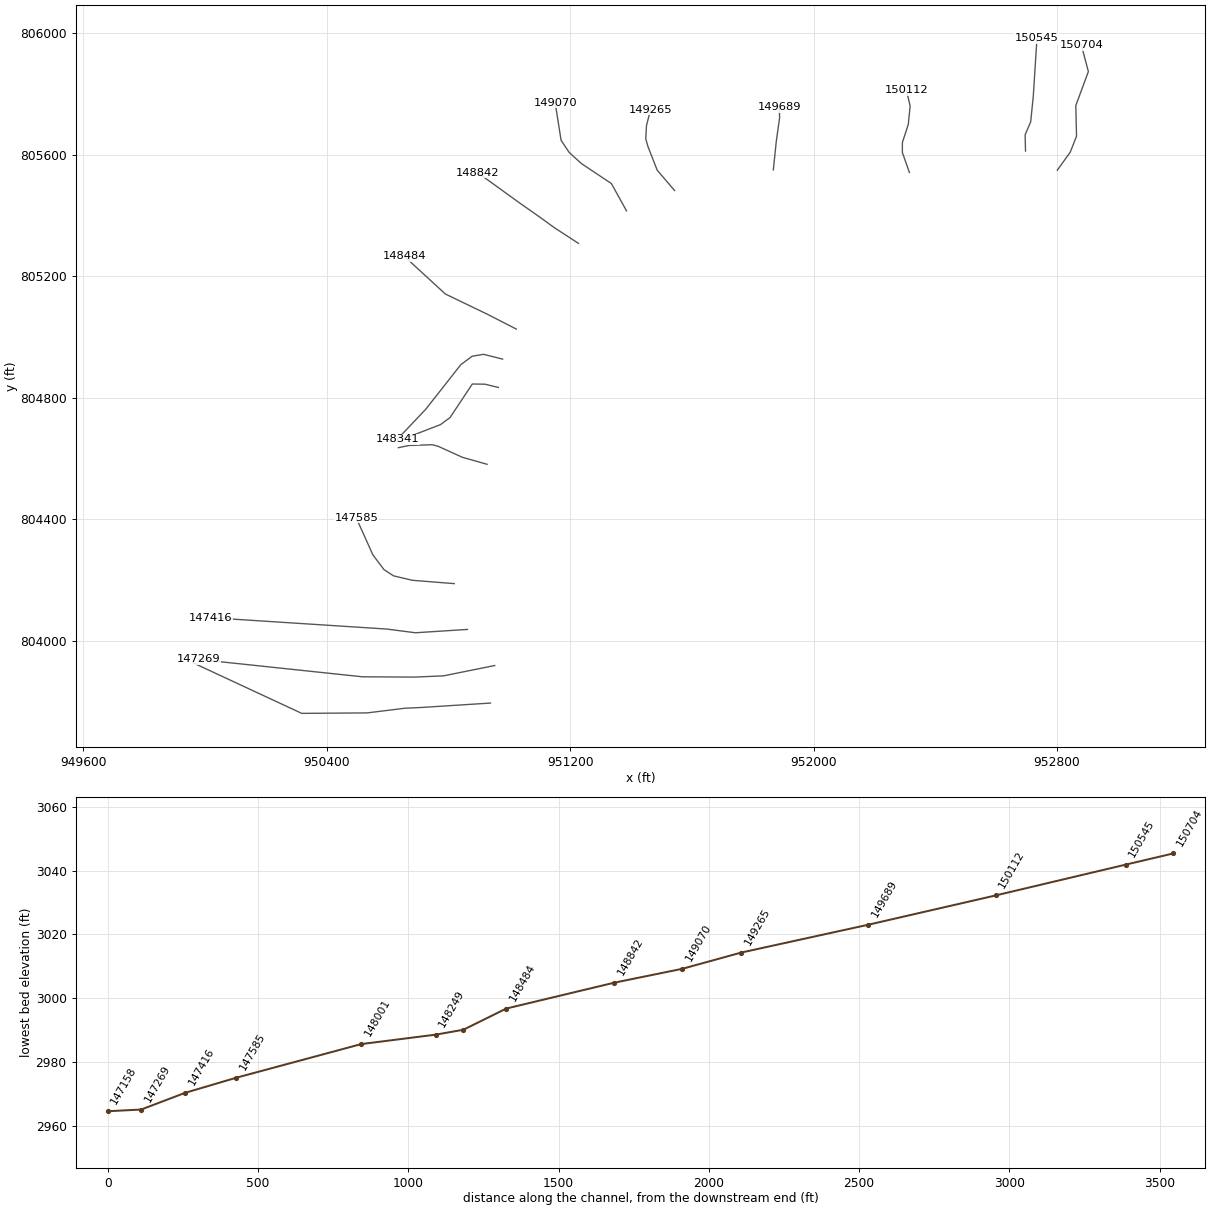
HEC-RAS study lds_big_laurel_crk.prj: lds_big_laurel_crk

--- lds_big_laurel_crk.g20 (geometry) --- (continued)

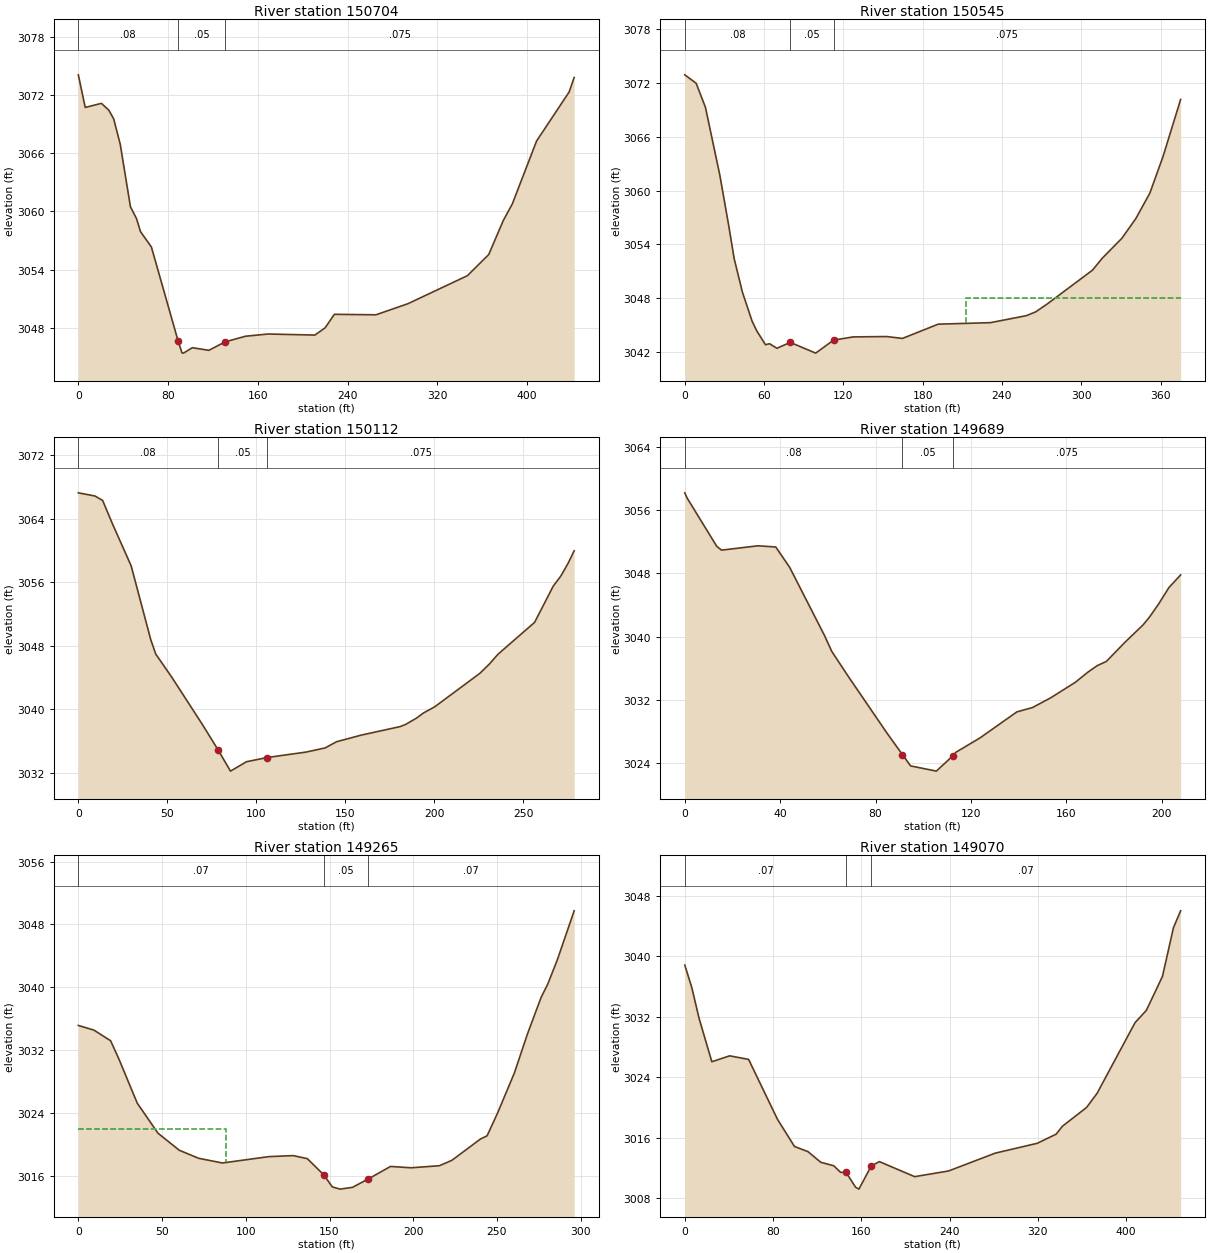
Type RM Length L Ch R = 1 ,150704  ,148.83,158.65,165.32
BEGIN DESCRIPTION:
150626.0
END DESCRIPTION:
XS GIS Cut Line= 6
  952801.0772521  805548.8928645  952843.6122894  805608.4415071
  952864.2719598  805660.6990435  952861.8415911   805761.567027
   952903.160932  805873.3721818  952880.0708928  805960.8726251
#Sta/Elev= 30
       0 3074.07    6.15 3070.71   20.56 3071.13   27.24 3070.42   31.55 3069.52
   37.38  3066.9   46.46 3060.47   51.87 3059.25   55.42 3057.91   65.13 3056.33
   88.853046.679    92.4 3045.42   93.74 3045.39  101.62 3045.95  116.35 3045.68
  130.91 3046.55  148.96 3047.13   169.2 3047.36  210.83 3047.25  220.01    3048
  228.22 3049.39  265.29 3049.34  293.74 3050.48  346.79 3053.37  365.83 3055.55
  378.74 3059.04  386.86 3060.77  408.48 3067.25  437.49  3072.3  441.97 3073.79
#Mann= 3 , 0 , 0
       0     .08       0   88.85     .05       0  130.91    .075       0
Bank Sta=88.85,130.91
Exp/Cntr=0.3,0.1

Type RM Length L Ch R = 1 ,150545  ,401.48,432.95,449.08
BEGIN DESCRIPTION:
150467.3
END DESCRIPTION:
XS GIS Cut Line= 5
  952696.5632035  805612.0875723  952695.3485312   805665.559781
  952713.5778329  805708.0948183  952722.0846355  805791.9491965
  952734.2375033  805982.7469678
#Sta/Elev= 30
       0 3072.93    8.59 3071.99   15.62 3069.31   26.47 3061.77   33.32 3056.04
   37.37 3052.42   43.57  3048.7   50.94 3045.44   54.41 3044.38   61.04 3042.82
   64.13 3042.93    69.7 3042.42   79.82 3043.08   99.05 3041.88  112.57 3043.33
  127.51 3043.69  152.82 3043.73  164.71 3043.52  191.75 3045.11  231.39 3045.28
  258.45 3046.06  265.52 3046.48  274.06 3047.34  308.57 3051.14   315.8 3052.45
  330.81  3054.7  341.32 3056.89  351.93 3059.73  361.93 3063.82  375.23 3070.18
#Mann= 3 , 0 , 0
       0     .08       0   79.82     .05       0  112.57    .075       0
#XS Ineff= 2 , 0
       0                  213.13       0    3048
Permanent Ineff=
       F       F
Bank Sta=79.82,112.57
Exp/Cntr=0.3,0.1

Type RM Length L Ch R = 1 ,150112  ,435.71,423.73,434.16
BEGIN DESCRIPTION:
150034.4
END DESCRIPTION:
XS GIS Cut Line= 6
  952314.9666366  805541.6017584  952291.8765974  805607.2268348
  952291.8765974  805640.0393731  952311.3205714  805699.5880157
  952317.3970053  805760.3513305  952305.2441375  805811.3931705
#Sta/Elev= 30
       0 3067.25    9.36 3066.85   13.66 3066.29   19.22 3063.32   29.68 3058.06
   40.68 3048.77   43.52 3046.94    52.4 3044.07   69.57 3038.13    78.5 3034.89
   85.48 3032.21   94.46 3033.39  105.98 3033.92  128.02 3034.61  138.65 3035.13
  145.08 3035.91  158.86 3036.74  180.84 3037.82  183.94  3038.1  189.97 3038.88
  193.89 3039.53  200.17  3040.3  225.51 3044.51  230.96  3045.7  235.78 3046.93
  256.34 3050.94  266.78 3055.49  271.09 3056.78   275.2  3058.4  278.56 3059.95
#Mann= 3 ,-1 , 0
       0     .08       0    78.5     .05       0  105.98    .075       0
Bank Sta=78.5,105.98
Exp/Cntr=0.3,0.1

Type RM Length L Ch R = 1 ,149689  ,378.89,423.14,433.45
BEGIN DESCRIPTION:
149610.6
END DESCRIPTION:
XS GIS Cut Line= 4
   951867.743969   805550.108561  951877.4664681  805643.6844141
  951888.4036394  805721.4623584  951887.1889672  805756.7052653
#Sta/Elev= 30
       0 3058.18     .86 3057.58   13.41 3051.42   15.41 3050.94   30.63 3051.49
   38.14 3051.34   43.97 3048.77   58.64 3040.12   61.61 3038.16   68.71 3034.92
   84.72 3027.86   91.22 3025.13   94.68 3023.69  105.48 3023.03  112.33 3024.95
  113.72 3025.42   123.8 3027.23  139.22 3030.51  145.78 3031.06  153.31 3032.27
  163.69 3034.24  169.06 3035.54  172.96 3036.36  176.78 3036.89  184.43 3039.27
  192.15  3041.5   194.9 3042.51  198.53 3044.08     203 3046.22  207.89 3047.81
#Mann= 3 , 0 , 0
       0     .08       0   91.22     .05       0  112.33    .075       0
Bank Sta=91.22,112.33
Exp/Cntr=0.3,0.1

Type RM Length L Ch R = 1 ,149265  ,167.43,195.67,294.49
BEGIN DESCRIPTION:
149187.5
END DESCRIPTION:
XS GIS Cut Line= 6
  951543.2646518  805482.0531158  951486.1474021  805548.8928645
  951455.7652326  805626.6708088  951448.4731022  805652.1922409
   951450.903471  805695.9419505  951464.2720352  805748.1984627
#Sta/Elev= 30
       0 3035.14    9.28 3034.55   19.28 3033.19   24.14 3030.91   35.19 3025.24
   47.54 3021.42   60.31 3019.24   71.83 3018.22   86.07 3017.62  113.76 3018.43
  128.38 3018.56  136.76 3018.17  146.63  3016.1  151.68 3014.57  156.38 3014.29
  163.72 3014.52  173.22 3015.59  186.43 3017.18  198.72 3017.01  215.63 3017.27
  223.08 3017.96   240.2 3020.68   244.1 3021.08  250.53 3024.06  260.48 3029.13
   268.2 3034.05  276.38 3038.72  280.34 3040.41  286.09 3043.52   296.1 3049.74
#Mann= 3 , 0 , 0
       0     .07       0  146.63     .05       0  173.22     .07       0
#XS Ineff= 2 , 0
       0    88.3    3022               0
Permanent Ineff=
       F       F
Bank Sta=146.63,173.22
Exp/Cntr=0.3,0.1

Type RM Length L Ch R = 1 ,149070  ,219.06,227.47,287.34
BEGIN DESCRIPTION:
148991.8
END DESCRIPTION:
XS GIS Cut Line= 6
  951385.2794187  805415.2123428   951335.452251  805505.1431549
  951237.0146363  805570.7682314  951196.9109918  805607.2268348
  951170.1748875  805647.3304793  951150.7298894   805771.289526
#Sta/Elev= 30
       0 3038.84    6.27 3035.91   12.97 3031.79    24.5 3026.06   40.66 3026.84
   57.83 3026.37      84 3018.45   99.45 3014.85  111.64 3014.17  123.27 3012.76
  135.02  3012.3  141.22 3011.43  146.22 3011.41  154.82 3009.46  157.83 3009.21
  168.96 3012.26  176.35 3012.85  208.36 3010.86  239.03 3011.61   281.4 3013.97
  319.43 3015.27  336.57 3016.48  342.29 3017.53  364.15 3020.01  373.68 3021.88
   408.1 3031.23  418.33 3032.85  432.94 3037.34  442.89 3043.78  449.41 3046.02
#Mann= 3 , 0 , 0
       0     .07       0  146.22     .05       0  168.96     .07       0
Bank Sta=146.22,168.96
Exp/Cntr=0.3,0.1

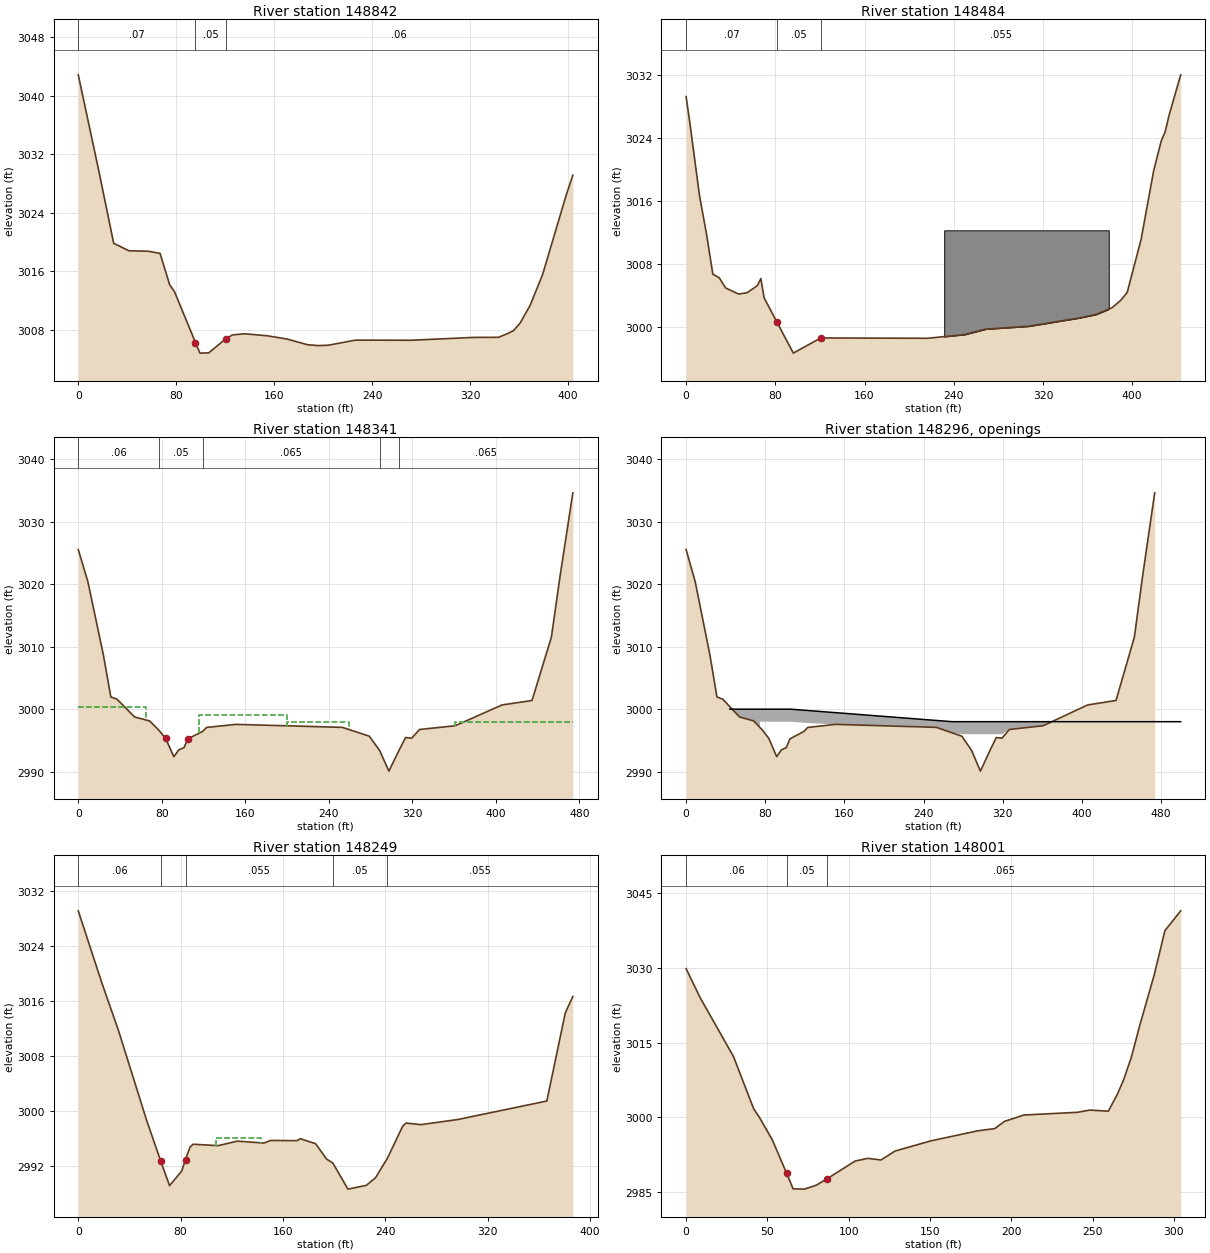
Type RM Length L Ch R = 1 ,148842  ,351.91,358.37,372.73
BEGIN DESCRIPTION:
148764.4
END DESCRIPTION:
XS GIS Cut Line= 5
  951227.2931614  805308.2679255  951147.0848483  805360.5254619
  951102.1194423  805393.3380001  951032.8483006  805441.9484472
  950896.7374102  805540.3860619
#Sta/Elev= 30
       0 3042.87   16.97 3029.59   28.93 3019.85    41.4 3018.82   57.08 3018.76
   66.84 3018.46   74.59 3014.21   78.67 3013.21   95.73 3006.28   99.41 3004.83
  106.55 3004.86  120.31 3006.76  125.96 3007.32  136.14 3007.47  154.46  3007.2
  170.74 3006.75  187.22 3005.98  195.95 3005.86  204.21 3005.91  226.53 3006.61
  271.56 3006.59  323.36 3006.98  343.22 3006.99  351.01 3007.52  355.37 3007.88
  360.86 3008.92  369.06 3011.34  379.26 3015.55  398.58 3026.44     404 3029.15
#Mann= 3 , 0 , 0
       0     .07       0   95.73     .05       0  120.31     .06       0
Bank Sta=95.73,120.31
Exp/Cntr=0.3,0.1

Type RM Length L Ch R = 1 ,148484  ,109.92,142.83,535.88
BEGIN DESCRIPTION:
148406.0
END DESCRIPTION:
XS GIS Cut Line= 4
  951023.1258016  805026.3236456   950928.334252  805074.9351168
  950789.7929929  805141.7748656  950654.8967747  805265.7339124
#Sta/Elev= 30
       0 3029.21    3.53 3025.71   11.93 3016.74   18.34 3011.77   23.98 3006.73
   29.71 3006.28   35.41 3004.99    47.2 3004.21   54.84 3004.39   64.01  3005.3
   67.05 3006.18   69.95 3003.74   81.39 3000.68   96.16 2996.74  120.73 2998.66
  216.62 2998.62  249.79 2999.09  268.84 2999.78  307.28 3000.14  353.07  3001.2
  367.86 3001.64  381.93 3002.48  389.93 3003.44   395.6 3004.43  408.02 3011.11
  419.31 3019.82  426.07 3023.57  429.66 3024.76  432.92 3026.72  443.55 3031.96
#Mann= 3 , 0 , 0
       0     .07       0   81.39     .05       0  120.73    .055       0
#Block Obstruct= 1 ,-1
  231.47  379.043012.283
Bank Sta=81.39,120.73
Exp/Cntr=0.5,0.3

Type RM Length L Ch R = 1 ,148341  ,100.39,91.69,35.63
BEGIN DESCRIPTION:
148263.2
END DESCRIPTION:
XS GIS Cut Line= 6
  950977.9658022   804927.554198  950915.5986283  804943.3039705
  950877.8004032  804937.0042663  950840.6320461  804909.2859776
  950725.3477667  804762.5031773  950632.1129641  804664.2273823
#Sta/Elev= 30
       0 3025.53    9.19  3020.4   24.11 3008.63   31.19 3001.95   37.08  3001.6
   53.92 2998.76   68.36 2998.12   77.21 2996.64   83.68 2995.31   91.55  2992.4
   96.34 2993.49  101.26 2993.85  105.02 2995.26  119.12 2996.44  122.95 2997.08
  150.96 2997.57  252.97 2997.09  278.77 2995.68  288.72 2993.38  297.51 2990.09
  307.64 2993.54  313.53 2995.46  319.35 2995.36  326.85 2996.75  361.03 2997.35
  405.97 3000.68  434.62 3001.39  453.17 3011.52  461.79 3021.61  473.73 3034.61
#Mann= 5 ,-1 , 0
       0     .06       0   77.21     .05       0  119.12    .065       0
  288.72     .05       0  307.64    .065       0
#XS Ineff= 4 ,-1
       0   64.55  3000.4  115.55     200    2999     200     259    2998
     361  473.73    2998
Permanent Ineff=
       F       F       F       F
Bank Sta=83.68,105.02
Exp/Cntr=0.5,0.3

Type RM Length L Ch R = 4 ,148296  ,,,
BEGIN DESCRIPTION:
148219.2  FBSTR_1237
END DESCRIPTION:
Bridge Culvert--1,0,-1,-1, 0
Deck Dist Width WeirC Skew NumUp NumDn MinLoCord MaxHiCord MaxSubmerge Is_Ogee
22,31,2.6,0, 11, 11, , , 0.95, 0, 1,1,,
   44.19   74.55   74.55   89.55  105.55  105.55     269     269     351     351
     500
    3000    3000    3000    3000    3000    3000    2998    2998    2998    2998
    2998
                    2998    2998    2998                    2996    2996
        
   50.49   60.49   60.49   75.49   92.49   92.49     174     174     256     256
     400
    3000    3000    3000    3000    3000    3000    2998    2998    2998    2998
    2998
                    2998    2998    2998                    2996    2996
        
BR Coef=-1 , 0 , 0 ,, 0 ,,,0.8,0,,0,
WSPro=,,,, 1 ,,,, 0 ,,,, 0 ,,,,-1 ,-1 ,-1 , 0 , 0 , 0 , 0 , 0
BC Mult= 1 ,0,64.55,0,45.49
BC Mult= 3 ,64.55,210,45.49,153
BC Mult= 3 ,200,473.73,143,386.59
BC Design=,, 0 ,, 0 ,,,,,,

Type RM Length L Ch R = 1 ,148249  ,255.24,248.06,35.32
BEGIN DESCRIPTION:
148171.5
END DESCRIPTION:
XS GIS Cut Line= 6
  950964.1066578  804834.3193954  950920.0087285  804845.0291997
  950878.4302712  804845.6590677  950805.3543171  804735.4137324
  950773.8557962  804712.1055438  950654.7912847  804666.1169863
#Sta/Elev= 30
       0 3029.09   18.37 3018.63   31.46 3011.64   53.65 2998.46   64.44 2992.65
   71.37 2989.06   80.89 2991.21   83.83 2992.87   87.31 2994.67   89.77  2995.1
  109.27 2994.89  124.34 2995.55  145.09 2995.27  150.39 2995.65  170.99 2995.62
  173.57  2995.9  185.53 2995.18  194.12 2992.94  199.04 2992.35  210.77 2988.56
  225.15 2989.11  232.34 2990.21  241.61 2993.05  253.61 2997.73  256.27 2998.18
  267.76 2997.95   296.4 2998.69  366.26 3001.39  380.68 3014.22  386.59 3016.62
#Mann= 5 ,-1 , 0
       0     .06       0   64.44     .05       0   83.83    .055       0
  199.04     .05       0  241.61    .055       0
#XS Ineff= 4 ,-1
       0   45.49    2997  107.49     143    2996     143     159    2995
     271  386.59    2995
Permanent Ineff=
       F       F       F       F
Bank Sta=64.44,83.83
Exp/Cntr=0.5,0.3

Type RM Length L Ch R = 1 ,148001  ,409.74,416.48,355.27
BEGIN DESCRIPTION:
147923.4
END DESCRIPTION:
XS GIS Cut Line= 6
  950927.1195797  804581.5323709  950845.6955703  804604.6224101
  950765.4872573  804641.0810135  950746.0432833   804645.941751
  950670.6957077  804643.5113822  950635.4528008  804636.2192519
#Sta/Elev= 30
       0 3029.86    8.59 3024.06   29.14 3012.22   41.55 3001.73   45.16 2999.98
   53.03 2995.49   61.79 2988.81   65.83 2985.66   72.77  2985.6   80.13  2986.4
   86.38 2987.61  104.05 2991.25   111.8 2991.78  119.89 2991.45   128.5 2993.24
  150.67  2995.3   179.5 2997.31  189.86 2997.75  195.91 2999.21  207.85 3000.48
  240.68 3001.02  248.35 3001.47  259.76 3001.25  265.47 3004.77  269.13 3007.54
  273.91 3012.08  279.12 3018.51  287.94 3028.58  294.54 3037.48  304.25 3041.47
#Mann= 3 , 0 , 0
       0     .06       0   61.79     .05       0   86.38    .065       0
Bank Sta=61.79,86.38
Exp/Cntr=0.3,0.1

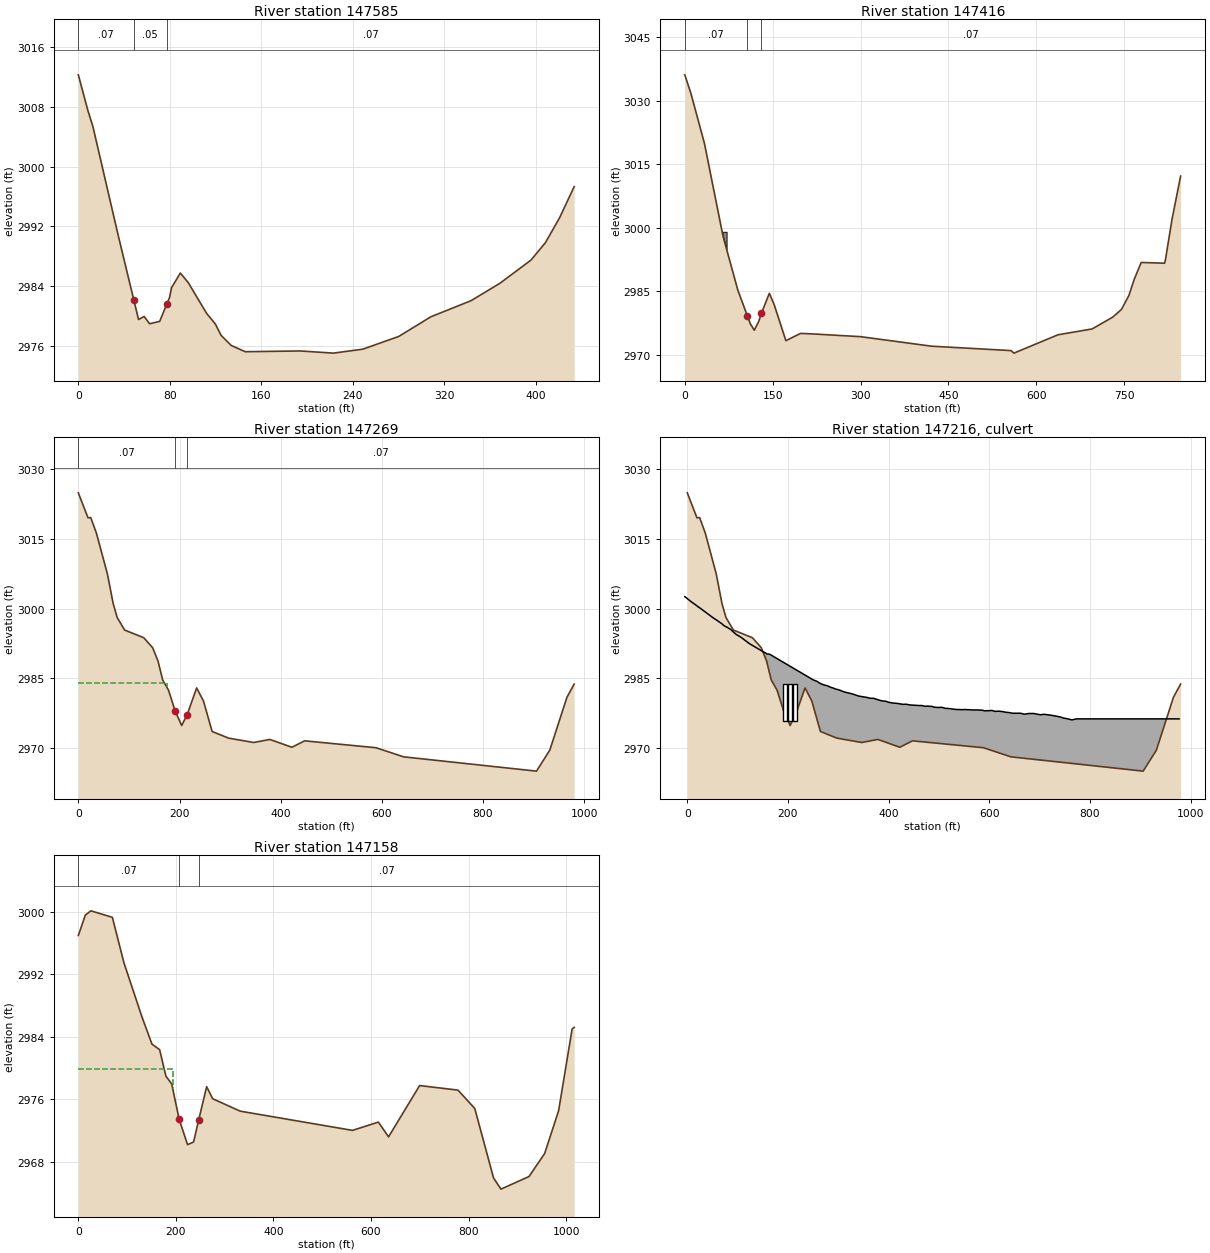
Type RM Length L Ch R = 1 ,147585  ,157.56,169.09,319.81
BEGIN DESCRIPTION:
147506.9
END DESCRIPTION:
XS GIS Cut Line= 6
  950818.9594659  804188.9976085  950681.6328791  804199.9347799
  950619.6538678  804214.5180164   950588.057026  804235.1776868
  950551.5984226   804283.789158  950496.9105174  804405.3168119
#Sta/Elev= 30
       0 3012.28    8.28 3007.55   12.79 3005.33   34.64 2990.93   48.472982.175
   52.65 2979.53   57.53 2979.94   62.28 2978.96   71.13 2979.28   77.25 2981.55
   79.78 2982.49   81.46 2983.78   89.18 2985.75   96.09 2984.47  112.16 2980.35
  119.81 2978.93  124.81 2977.41  133.63 2976.06   145.9 2975.22  194.02 2975.32
  222.94 2975.03  248.76 2975.56  280.13 2977.26  308.17 2979.89  343.39 2982.05
  368.73 2984.39  395.73 2987.48  408.33  2989.8  420.72 2993.13  433.52 2997.31
#Mann= 3 , 0 , 0
       0     .07       0   48.47     .05       0   77.25     .07       0
Bank Sta=48.47,77.25
Exp/Cntr=0.3,0.1

Type RM Length L Ch R = 1 ,147416  ,144.2,146.94,162.76
XS GIS Cut Line= 4
  950862.5207272  804038.3772222  950691.3553782   804027.365286
  950597.7785009  804039.5181538  950018.5518871  804076.9507483
#Sta/Elev= 30
       0 3036.08   10.42 3031.71   33.65 3019.81   65.23 2997.98    90.5 2985.22
  106.81 2979.14  111.75 2977.28  118.58 2975.74  126.32 2977.87  130.84 2979.76
  144.32 2984.46  152.43 2981.85  172.57 2973.27  197.54 2974.99  219.04 2974.86
  299.96 2974.22  421.08 2971.97  556.78 2970.93  561.81 2970.33  636.94 2974.66
  695.43 2976.05  730.38 2978.83  745.22 2980.63  758.01 2983.94  767.19 2987.78
  778.99 2991.75   818.9 2991.57  820.24 2992.23  831.48 3001.84  846.32 3012.15
#Mann= 3 , 0 , 0
       0     .07       0  106.81     .05       0  130.84     .07       0
#Block Obstruct= 1 ,-1
   63.57   71.312999.002
Bank Sta=106.81,130.84
Exp/Cntr=0.5,0.3

Type RM Length L Ch R = 1 ,147269  ,102,111.01,132.57
XS GIS Cut Line= 5
  950952.0090955  803919.5738755  950783.8322908  803885.6306473
   950687.709313  803881.5318965  950516.9095946  803882.5448062
  949978.4369768  803939.6323548
#Sta/Elev= 30
       0 3024.88   19.13 3019.51   24.49 3019.56   35.75 3016.22    57.4 3007.48
   68.82 3001.11   76.73  2998.1   91.52 2995.39  129.33 2993.74  146.93 2991.59
  157.49 2988.74  166.69 2984.68  178.27 2982.47  191.21 2978.05  204.25 2974.87
  215.22 2977.23  233.88 2982.95  247.39 2980.13  264.44 2973.59  297.19 2972.16
  346.56 2971.22  378.59 2971.88  422.16  2970.2  447.39 2971.58  588.31  2970.1
  642.88 2968.14  905.66 2965.07   931.9 2969.57  965.88 2980.96  980.07 2983.78
#Mann= 3 , 0 , 0
       0     .07       0  191.21     .05       0  215.22     .07       0
#XS Ineff= 2 , 0
       0     175    2984     233       0    2979
Permanent Ineff=
       F       F
Bank Sta=191.21,215.22
Exp/Cntr=0.5,0.3

Type RM Length L Ch R = 2 ,147216  ,,,
Bridge Culvert--1,0,-1,-1, 0
Deck Dist Width WeirC Skew NumUp NumDn MinLoCord MaxHiCord MaxSubmerge Is_Ogee
40,28,2.6,0, 182, 183, , , 0.95, 0, 1,1,,
      -5   -4.79    -.05    2.98    7.98   14.21   14.44   15.02    22.5   24.13
   28.94   35.16   37.12   39.39      51   51.71   51.89   58.24   59.11   66.16
   68.54   72.58   77.23   80.36   84.83   86.66   90.16   95.06   97.35  101.17
  103.74   109.2  111.84  115.27  120.37  123.11  128.82   129.2  131.01  137.49
   137.9  143.73  147.57  152.06  156.02   158.2  162.67  163.33  249.91  257.35
  258.36  264.29  271.08  272.26  277.43  279.06  285.16  287.16  290.98  294.23
  299.41  302.63  304.23  309.76  313.91  317.95     322  324.71  329.57  333.01
  336.47  339.83   347.2     348  351.31  355.34  356.98   363.5  367.62  370.29
  374.88  378.92  382.18  385.58  394.03  394.19  394.41  401.18  401.26  408.08
  409.92  417.23  417.26  417.32  425.73  428.46  432.94  435.51  441.51  443.72
  448.82  453.78  457.59  462.93  464.63  469.89  473.36   478.2  480.71  484.91
  489.09  490.65  496.45  496.52  497.29  504.86  505.54  508.59  512.57  513.32
  515.48  520.32  522.02  526.31  529.17  532.62  538.36  539.95  545.65  551.21
  554.39   559.8  562.04   567.2  570.76  577.38  578.68  579.91  587.66  590.46
  595.29  597.42  604.41  605.21  611.84  615.58  620.79  626.42  628.49  629.86
  637.54  637.57  640.43  645.66  653.02  654.94  661.26  662.49  668.11  671.25
  675.82  678.74  687.67  687.78  694.17  694.66  696.21  701.65  707.99  709.28
  710.42  721.25  722.14   731.6  736.34  740.81  748.15  749.99  761.56  764.11
  773.67     977
 3002.57 3002.56 3002.14 3001.88 3001.45 3000.99 3000.97 3000.92  3000.3  3000.2
 2999.82 2999.32 2999.17 2998.97 2998.04 2997.98 2997.97 2997.52 2997.46 2996.93
 2996.75 2996.35 2996.09  2995.9 2995.59 2995.48  2995.1 2994.63 2994.43 2994.19
 2994.03 2993.65 2993.41 2993.13 2992.69 2992.49 2992.13 2992.11 2991.99 2991.57
 2991.54 2991.21 2990.95 2990.64 2990.45 2990.23 2990.22 2990.21  2984.7 2984.38
 2984.31  2983.9 2983.63 2983.57 2983.45 2983.37 2983.08 2983.02 2982.88 2982.72
 2982.59 2982.47 2982.41 2982.16 2982.03 2981.94 2981.83 2981.75 2981.61 2981.48
 2981.36 2981.22 2981.07 2981.06 2981.01 2980.94 2980.91 2980.73 2980.73 2980.72
 2980.54 2980.41  2980.3 2980.19 2980.09 2980.08 2980.08 2979.84 2979.83 2979.71
 2979.69 2979.62 2979.62 2979.62 2979.48 2979.42 2979.45 2979.44  2979.3 2979.29
 2979.25 2979.21 2979.16 2979.15 2979.19 2979.09    2979 2979.07    2979    2979
 2978.88 2978.81 2978.74 2978.74 2978.75 2978.77 2978.78  2978.7 2978.57 2978.54
 2978.57  2978.5 2978.51  2978.4  2978.4 2978.33 2978.31 2978.31 2978.28 2978.32
 2978.28 2978.27 2978.26 2978.21 2978.21 2978.23 2978.17 2978.21 2978.13 2978.02
 2978.07 2978.05  2978.1 2978.11 2977.91 2977.95 2977.94 2977.85 2977.85 2977.77
 2977.68 2977.68 2977.64 2977.51 2977.52 2977.51 2977.51 2977.51 2977.33 2977.32
 2977.42 2977.45 2977.46 2977.46 2977.33 2977.32 2977.29 2977.18 2977.28 2977.26
 2977.26 2977.11  2977.1  2976.9 2976.79 2976.72 2976.45 2976.44 2976.17 2976.09
  2976.3  2976.3
                                                                                
                                                                                
                                                                                
                                                                                
                                                                                
                                                                                
                                                                                
                                                                                
                                                                                
                                                                                
                                                                                
                                                                                
                                                                                
                                                                                
                                                                                
                                                                                
                                                                                
                                                                                
                
       0     .21    4.95    7.98   12.98   19.21   19.44   20.02    27.5   29.13
   33.94   40.16   42.12   44.39      56   56.71   56.89   63.24   64.11   71.16
   73.54   77.58   82.23   85.36   89.83   91.66   95.16  100.06  102.35  106.17
  108.74   114.2  116.84  120.27  125.37  128.11  133.82   134.2  136.01  142.49
   142.9  148.73  152.57  157.06  161.02   163.2  167.67  168.33  253.76  254.91
  262.35  263.36  269.29  276.08  277.26  282.43  284.06  290.16  292.16  295.98
  299.23  304.41  307.63  309.23  314.76  318.91  322.95     327  329.71  334.57
  338.01  341.47  344.83   352.2     353  356.31  360.34  361.98   368.5  372.62
  375.29  379.88  383.92  387.18  390.58  399.03  399.19  399.41  406.18  406.26
  413.08  414.92  422.23  422.26  422.32  430.73  433.46  437.94  440.51  446.51
  448.72  453.82  458.78  462.59  467.93  469.63  474.89  478.36   483.2  485.71
  489.91  494.09  495.65  501.45  501.52  502.29  509.86  510.54  513.59  517.57
  518.32  520.48  525.32  527.02  531.31  534.17  537.62  543.36  544.95  550.65
  556.21  559.39   564.8  567.04   572.2  575.76  582.38  583.68  584.91  592.66
  595.46  600.29  602.42  609.41  610.21  616.84  620.58  625.79  631.42  633.49
  634.86  642.54  642.57  645.43  650.66  658.02  659.94  666.26  667.49  673.11
  676.25  680.82  683.74  692.67  692.78  699.17  699.66  701.21  706.65  712.99
  714.28  715.42  726.25  727.14   736.6  741.34  745.81  753.15  754.99  766.56
  769.11  778.67    1016
 3002.57 3002.56 3002.14 3001.88 3001.45 3000.99 3000.97 3000.92  3000.3  3000.2
 2999.82 2999.32 2999.17 2998.97 2998.04 2997.98 2997.97 2997.52 2997.46 2996.93
 2996.75 2996.35 2996.09  2995.9 2995.59 2995.48  2995.1 2994.63 2994.43 2994.19
 2994.03 2993.65 2993.41 2993.13 2992.69 2992.49 2992.13 2992.11 2991.99 2991.57
 2991.54 2991.21 2990.95 2990.64 2990.45 2990.23 2990.22 2990.21 2984.78  2984.7
 2984.38 2984.31  2983.9 2983.63 2983.57 2983.45 2983.37 2983.08 2983.02 2982.88
 2982.72 2982.59 2982.47 2982.41 2982.16 2982.03 2981.94 2981.83 2981.75 2981.61
 2981.48 2981.36 2981.22 2981.07 2981.06 2981.01 2980.94 2980.91 2980.73 2980.73
 2980.72 2980.54 2980.41  2980.3 2980.19 2980.09 2980.08 2980.08 2979.84 2979.83
 2979.71 2979.69 2979.62 2979.62 2979.62 2979.48 2979.42 2979.45 2979.44  2979.3
 2979.29 2979.25 2979.21 2979.16 2979.15 2979.19 2979.09    2979 2979.07    2979
    2979 2978.88 2978.81 2978.74 2978.74 2978.75 2978.77 2978.78  2978.7 2978.57
 2978.54 2978.57  2978.5 2978.51  2978.4  2978.4 2978.33 2978.31 2978.31 2978.28
 2978.32 2978.28 2978.27 2978.26 2978.21 2978.21 2978.23 2978.17 2978.21 2978.13
 2978.02 2978.07 2978.05  2978.1 2978.11 2977.91 2977.95 2977.94 2977.85 2977.85
 2977.77 2977.68 2977.68 2977.64 2977.51 2977.52 2977.51 2977.51 2977.51 2977.33
 2977.32 2977.42 2977.45 2977.46 2977.46 2977.33 2977.32 2977.29 2977.18 2977.28
 2977.26 2977.26 2977.11  2977.1  2976.9 2976.79 2976.72 2976.45 2976.44 2976.17
 2976.09  2976.3  2976.3
                                                                                
                                                                                
                                                                                
                                                                                
                                                                                
                                                                                
                                                                                
                                                                                
                                                                                
                                                                                
                                                                                
                                                                                
                                                                                
                                                                                
                                                                                
                                                                                
                                                                                
                                                                                
                        
BR Coef=-1 , 0 , 0 ,, 0 ,,,0.8,-1,,0,
WSPro=,,,, 1 ,,,, 0 ,,,, 0 ,,,,-1 ,-1 ,-1 , 0 , 0 , 0 , 0 , 0
Multiple Barrel Culv=2,8,9,32,0.011,0.4,1,8,1,2975.75,2970.29, 3,Culvert #1  , 0 ,36
   194.5   218.5     204     228   213.5   237.5
Culvert Bottom n=0.011
BC Design=,, 0 ,, 0 ,,,,,,

Type RM Length L Ch R = 1 ,147158  ,240.06,163.8,33.91
XS GIS Cut Line= 6
  950938.1222983  803796.1422791  950712.3417606  803781.6891129
  950657.3138292  803779.1696409  950532.3388002  803763.7404353
   950317.875403  803762.1980268  949959.9219301  803928.8313988
#Sta/Elev= 30
       0 2996.97   14.32 2999.57   25.73 3000.12    69.8 2999.29   93.34 2993.51
  130.24  2986.6  150.95 2983.08  166.69 2982.37  179.55 2978.99  191.49 2977.98
  206.52 2973.52  223.84 2970.23  236.29 2970.56  246.77 2973.39   263.1 2977.64
  275.45  2976.1  331.75 2974.51  562.13 2972.05  615.18 2973.11  636.06 2971.22
  699.69 2977.78  778.33  2977.2  812.83 2974.85  851.29 2965.97   866.5 2964.54
  924.04 2966.15  956.13  2969.1  984.76 2974.57 1012.43 2985.02 1016.57 2985.22
#Mann= 3 , 0 , 0
       0     .07       0  206.52     .05       0  246.77     .07       0
#XS Ineff= 2 , 0
       0     194  2979.9     262       0    2974
Permanent Ineff=
       F       F
#Block Obstruct= 2 , 0
       0                  704.95       0 2977.72
Bank Sta=206.52,246.77
Exp/Cntr=0.5,0.3