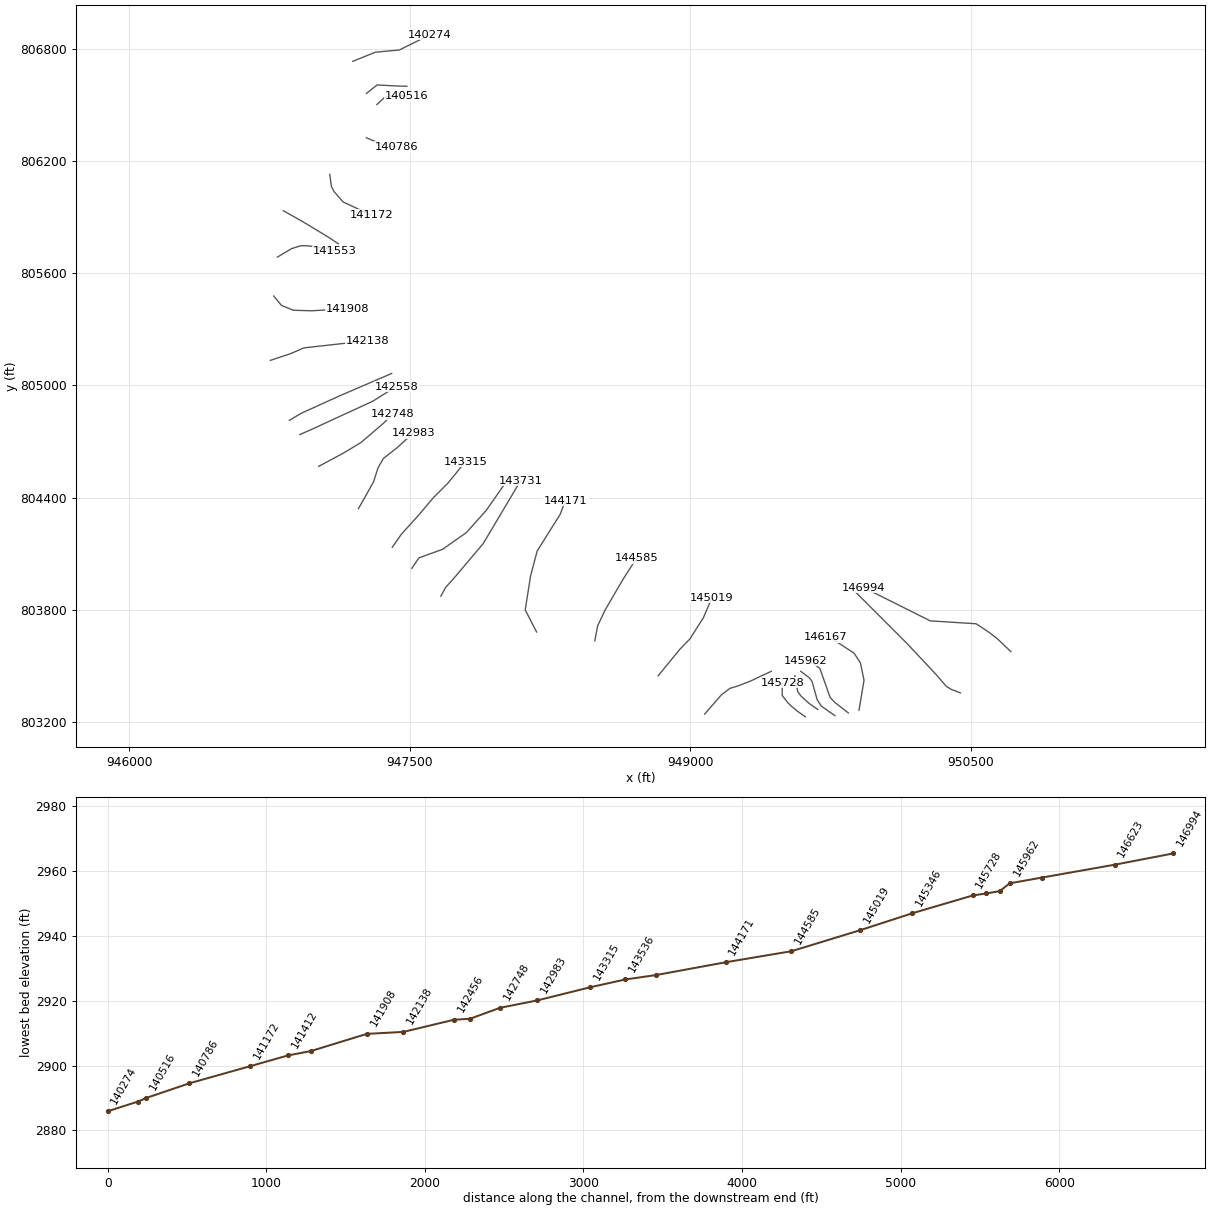
HEC-RAS study lds_big_laurel_crk.prj: lds_big_laurel_crk

--- lds_big_laurel_crk.g20 (geometry) --- (continued)

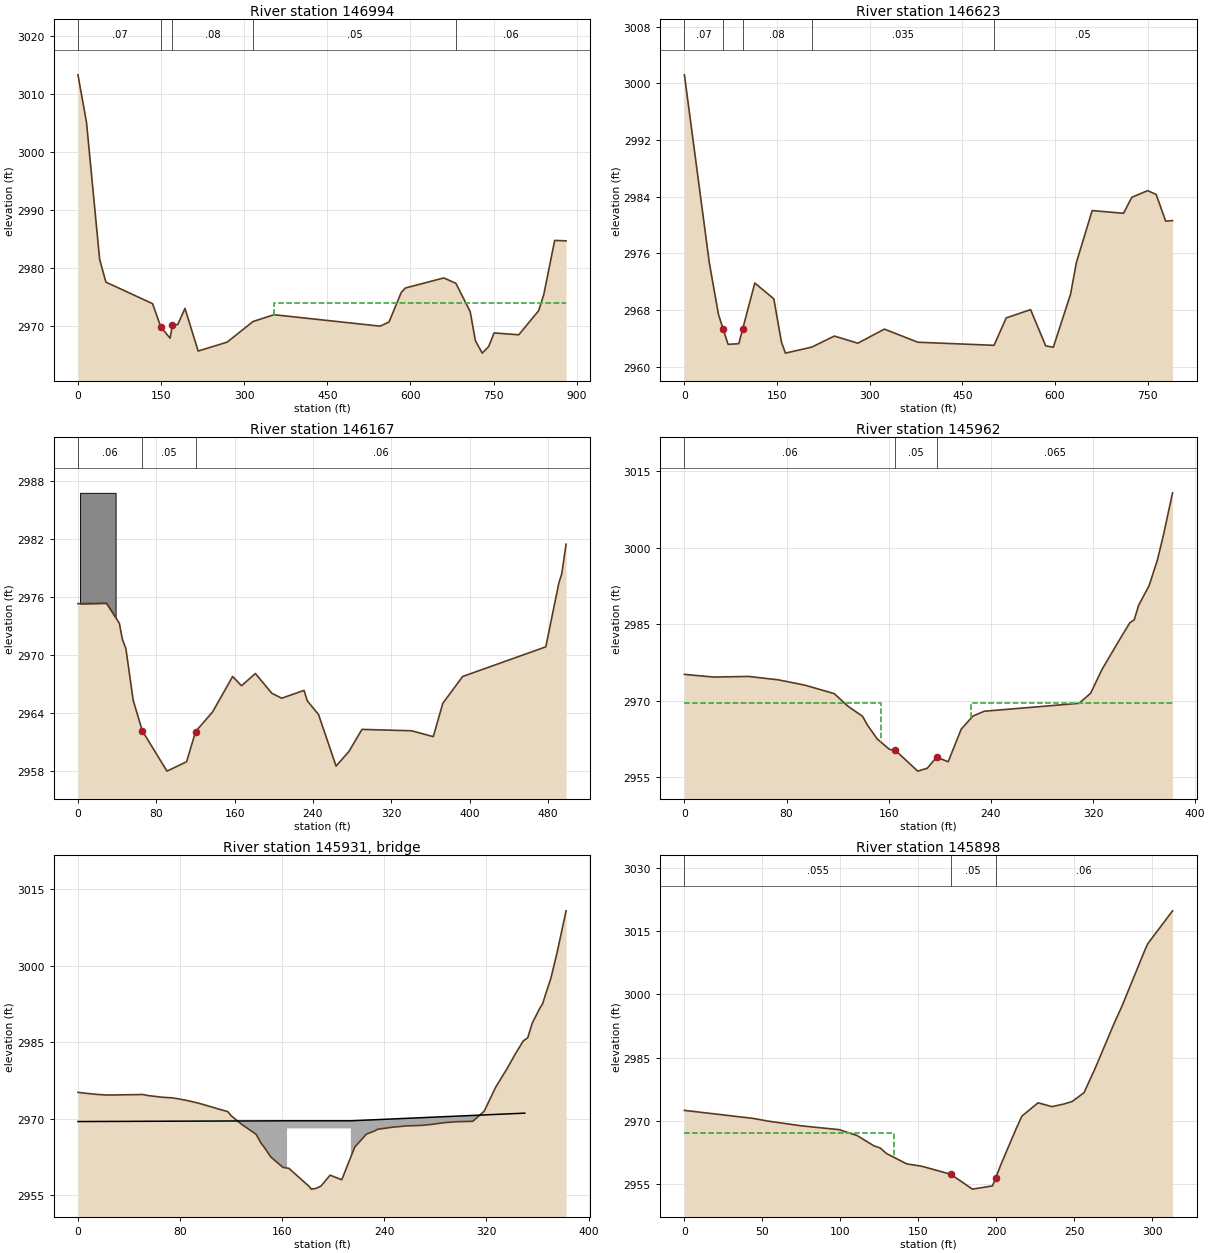
Type RM Length L Ch R = 1 ,146994  ,367.2,371.3,170.17
XS GIS Cut Line= 6
   950713.230745  803576.4975775  950642.7439069  803643.3373262
  950597.7785009  803678.5802332  950527.7105506  803725.1679334
  950282.3887422   803740.597139  949927.5211104   803918.031467
#Sta/Elev= 30
       0 3013.36   15.47 3005.16   39.12 2981.58   50.45 2977.63  134.74 2973.91
  149.59 2969.88  166.31 2967.97   170.4 2970.17  180.12 2970.32  193.19  2973.1
  216.95 2965.75  269.17 2967.28  316.04 2970.84  353.84 2972.01  545.22 2970.04
  561.42 2970.75  583.62 2975.87  591.06 2976.62  660.37 2978.35  682.25 2977.41
  707.94 2972.53  717.42 2967.51  729.71 2965.39  741.13 2966.51  751.05 2968.87
   795.6 2968.55  831.48 2972.71  840.66 2975.46  860.41 2984.82  880.97 2984.74
#Mann= 5 ,-1 , 0
       0     .07       0  149.59     .05       0   170.4     .08       0
  316.04     .05       0  682.25     .06       0
#XS Ineff= 2 , 0
       0                  353.84       0    2974
Permanent Ineff=
       F       F
#Block Obstruct= 2 , 0
       0                  694.15       0 2975.66
Bank Sta=149.59,170.4
Exp/Cntr=0.3,0.1

Type RM Length L Ch R = 1 ,146623  ,595.61,455.69,288.88
XS GIS Cut Line= 6
  950443.4383088  803355.3166124  950393.6121653  803374.7616106
  950368.0917574  803390.5595194  950317.0499174   803450.108162
  950157.4137132  803620.2503596  949878.1476526  803899.5164203
#Sta/Elev= 30
       0 3001.18   40.31 2974.66   55.19 2967.34   63.01 2965.24   70.66 2963.14
   88.02 2963.23   94.12 2965.25  113.98 2971.79  144.76 2969.56  157.17 2963.43
  163.56  2961.9  206.26 2962.75  242.72 2964.31  280.75  2963.3  323.77 2965.29
  377.84 2963.44  501.31    2963  520.98 2966.87  560.48 2968.04  584.98 2962.92
  597.25 2962.73  625.18 2970.22  634.62 2974.69  660.15 2982.02  710.92 2981.64
  724.31 2983.89  749.88 2984.83  763.72  2984.3  779.24 2980.52  790.28 2980.61
#Mann= 5 ,-1 , 0
       0     .07       0   63.01     .05       0   94.12     .08       0
  206.26    .035       0  501.31     .05       0
Bank Sta=63.01,94.12
Exp/Cntr=0.3,0.1

Type RM Length L Ch R = 1 ,146167  ,124.78,204.81,214.08
BEGIN DESCRIPTION:
146089.1
END DESCRIPTION:
XS GIS Cut Line= 6
  949901.4251158  803262.9554316  949928.1612202  803423.3720576
   949908.716222  803516.9489349  949874.6890115  803567.9907748
  949761.6681603   803642.122654  949721.5634917  803651.8441289
#Sta/Elev= 30
       0  2975.3   29.07 2975.35   42.25 2973.28   45.44  2971.6   48.98 2970.64
   56.42  2965.3    65.7 2962.14   90.93 2957.96  110.95 2958.93  120.19 2962.06
  137.52 2964.09  157.99 2967.76  167.09  2966.8  181.22 2968.07  198.04 2966.02
  208.12 2965.51  230.91 2966.32  234.27 2965.24  245.78 2963.81  263.66 2958.48
  276.86 2960.01  290.08 2962.28  340.73 2962.14  362.91 2961.53  372.65 2964.98
  392.91 2967.76  477.84 2970.83  491.21 2977.45  494.16  2978.4  498.55 2981.46
#Mann= 3 , 0 , 0
       0     .06       0    65.7     .05       0  120.19     .06       0
#Block Obstruct= 1 ,-1
    2.17   38.452986.778
Bank Sta=65.7,120.19
Exp/Cntr=0.5,0.3

Type RM Length L Ch R = 1 ,145962  ,89.41,64.29,70.77
BEGIN DESCRIPTION:
145884.3
END DESCRIPTION:
XS GIS Cut Line= 6
   949844.306842  803248.3721951  949772.6053316  803304.2747725
  949747.0849237  803331.0108768  949692.3970186  803485.3510689
  949658.3687839  803513.3028697  949614.6190743   803526.671434
#Sta/Elev= 30
       0 2975.17   22.63 2974.64   50.31 2974.76   73.36  2974.1   94.26 2973.06
  117.34 2971.39  127.88 2968.96  139.56 2966.93  143.32 2965.23  151.02  2962.5
  160.56 2960.45  165.25 2960.26  182.73 2956.18  190.23 2956.75  197.54 2958.92
  206.62 2958.02  216.78 2964.41  226.02 2966.99  234.85 2967.93  309.22 2969.49
  318.22 2971.48  327.05 2976.12  342.49 2982.67  348.85 2985.28  352.29 2985.87
  355.82 2988.74  363.94 2992.56  370.43 2997.56  375.32 3002.63  382.33 3010.79
#Mann= 3 , 0 , 0
       0     .06       0  165.25     .05       0  197.54    .065       0
#XS Ineff= 2 , 0
       0  153.77 2969.59  224.77       0 2969.59
Permanent Ineff=
       F       F
Bank Sta=165.25,197.54
Exp/Cntr=0.5,0.3

Type RM Length L Ch R = 3 ,145931  ,,,
BEGIN DESCRIPTION:
145854.8  FBSTR_1223
END DESCRIPTION:
Bridge Culvert--1,0,-1,-1, 0
Deck Dist Width WeirC Skew NumUp NumDn MinLoCord MaxHiCord MaxSubmerge Is_Ogee
16,26,2.6,0, 7, 7, , , 0.95, 0, 1,1,,
       0  163.77  163.77  188.77  213.77  213.77     350
 2969.44 2969.59 2969.59 2969.59 2969.59 2969.59 2971.09
                 2968.09 2968.09 2968.09
       0  149.69  149.69  174.69  199.69  199.69     300
 2969.44 2969.59 2969.59 2969.59 2969.59 2969.59 2971.09
                 2968.09 2968.09 2968.09
BR Coef=-1 , 0 , 0 ,, 0 ,,,0.8,0,,0,
WSPro=,,,, 1 ,,,, 0 ,,,, 0 ,,,,-1 ,-1 ,-1 , 0 , 0 , 0 , 0 , 0
BR U #Sta/Elev= 75
       0 2975.17     6.1 2974.99    6.37 2974.98   15.29 2974.76   22.63 2974.64
   24.31 2974.66   26.49 2974.65   47.74 2974.73   50.31 2974.76   51.12 2974.73
   55.43 2974.52   55.52 2974.52   66.38  2974.2   73.36  2974.1    76.4 2973.99
   78.37 2973.91   86.44 2973.52   90.92 2973.25   94.26 2973.06  106.48 2972.18
  108.96 2971.98  117.34 2971.39  120.08 2970.57  127.88 2968.96  139.56 2966.93
  143.32 2965.23  146.59 2964.15  151.02  2962.5  157.77 2961.04  160.56 2960.45
  163.62 2960.32  165.25 2960.26  168.662959.497  179.77 2957.01  180.91 2956.76
  182.73 2956.18  186.19  2956.3  190.23 2956.75  197.54 2958.92  206.62 2958.02
  208.722959.341  216.78 2964.41  226.02 2966.99  231.76 2967.52  234.85 2967.93
  235.89 2967.96  241.73 2968.16  246.61 2968.34  251.35 2968.44  257.69 2968.59
   263.6 2968.63  264.71 2968.64  268.46 2968.68  269.78  2968.7  278.29 2968.92
  283.16 2969.09  288.13 2969.24  296.34  2969.4  308.42 2969.48  309.22 2969.49
  309.71 2969.58  318.22 2971.48  327.05 2976.12   335.9 2979.74  342.49 2982.67
  348.85 2985.28  352.29 2985.87  355.82 2988.74  361.64 2991.62  363.94 2992.56
  365.27 2993.59  365.75 2993.99  370.43 2997.56  375.32 3002.63  382.33 3010.79
BR U #Mann= 3
       0     .06  165.25    .045  197.54    .065
BR D #Sta/Elev= 58
       0 2972.45    2.73 2972.32    7.96 2972.08   10.92 2971.95   17.15 2971.63
    25.1 2971.36   27.36 2971.27   34.24 2970.98   43.84 2970.56   48.49 2970.23
    53.9 2969.89   64.34 2969.37   68.01 2969.18   75.29 2968.77   81.29 2968.57
   86.55 2968.35   89.05 2968.25   96.67 2967.98   99.18 2967.88  109.15 2966.64
  110.69 2966.49  121.45 2964.05  123.18 2963.83  125.63 2963.51  129.49 2962.23
  142.52 2959.76  143.03 2959.74  143.86 2959.71  152.32 2959.18  159.69 2958.51
  170.71  2957.3  183.91 2953.98  184.69 2953.76  197.37 2954.52  197.44 2954.52
  197.57 2954.53   199.62956.438  202.92 2959.57  206.47 2962.68  212.54 2967.96
   216.4 2971.09  226.03 2974.06  226.64 2974.23  226.75 2974.25   226.9 2974.24
  232.29 2973.62  235.66 2973.34  243.39 2973.97  248.73 2974.58   254.9 2976.27
   256.2 2976.64   263.1  2982.2  275.95 2993.45  278.99 2995.96  280.48 2997.12
   295.5 3010.72  297.18 3012.05  312.99 3019.82
BR D #Mann= 3
       0    .055  170.71    .045   199.6     .06
BC Design=,, 0 ,, 0 ,,,,,,

Type RM Length L Ch R = 1 ,145898  ,44.85,83.71,81.58
BEGIN DESCRIPTION:
145820.0
END DESCRIPTION:
XS GIS Cut Line= 6
  949772.6053316  803233.7889585   949699.689149  803284.8307985
  949677.8137821   803318.858009  949649.8619813  803417.2956237
  949636.4944412  803435.5249254  949590.3133387  803470.7678324
#Sta/Elev= 30
       0 2972.45   43.84 2970.56    53.9 2969.89   75.29 2968.77   99.18 2967.88
  110.69 2966.49  121.45 2964.05  125.63 2963.51  129.49 2962.23  142.52 2959.76
  152.32 2959.18  170.71  2957.3  184.69 2953.76  197.57 2954.53   199.62956.438
  202.92 2959.57  206.47 2962.68  212.54 2967.96   216.4 2971.09  226.75 2974.25
  235.66 2973.34  243.39 2973.97  248.73 2974.58   256.2 2976.64   263.1  2982.2
  275.95 2993.45  280.48 2997.12   295.5 3010.72  297.18 3012.05  312.99 3019.82
#Mann= 3 , 0 , 0
       0    .055       0  170.71     .05       0   199.6     .06       0
#XS Ineff= 2 , 0
       0  134.69    2967  214.69       0    2967
Permanent Ineff=
       F       F
Bank Sta=170.71,199.6
Exp/Cntr=0.5,0.3

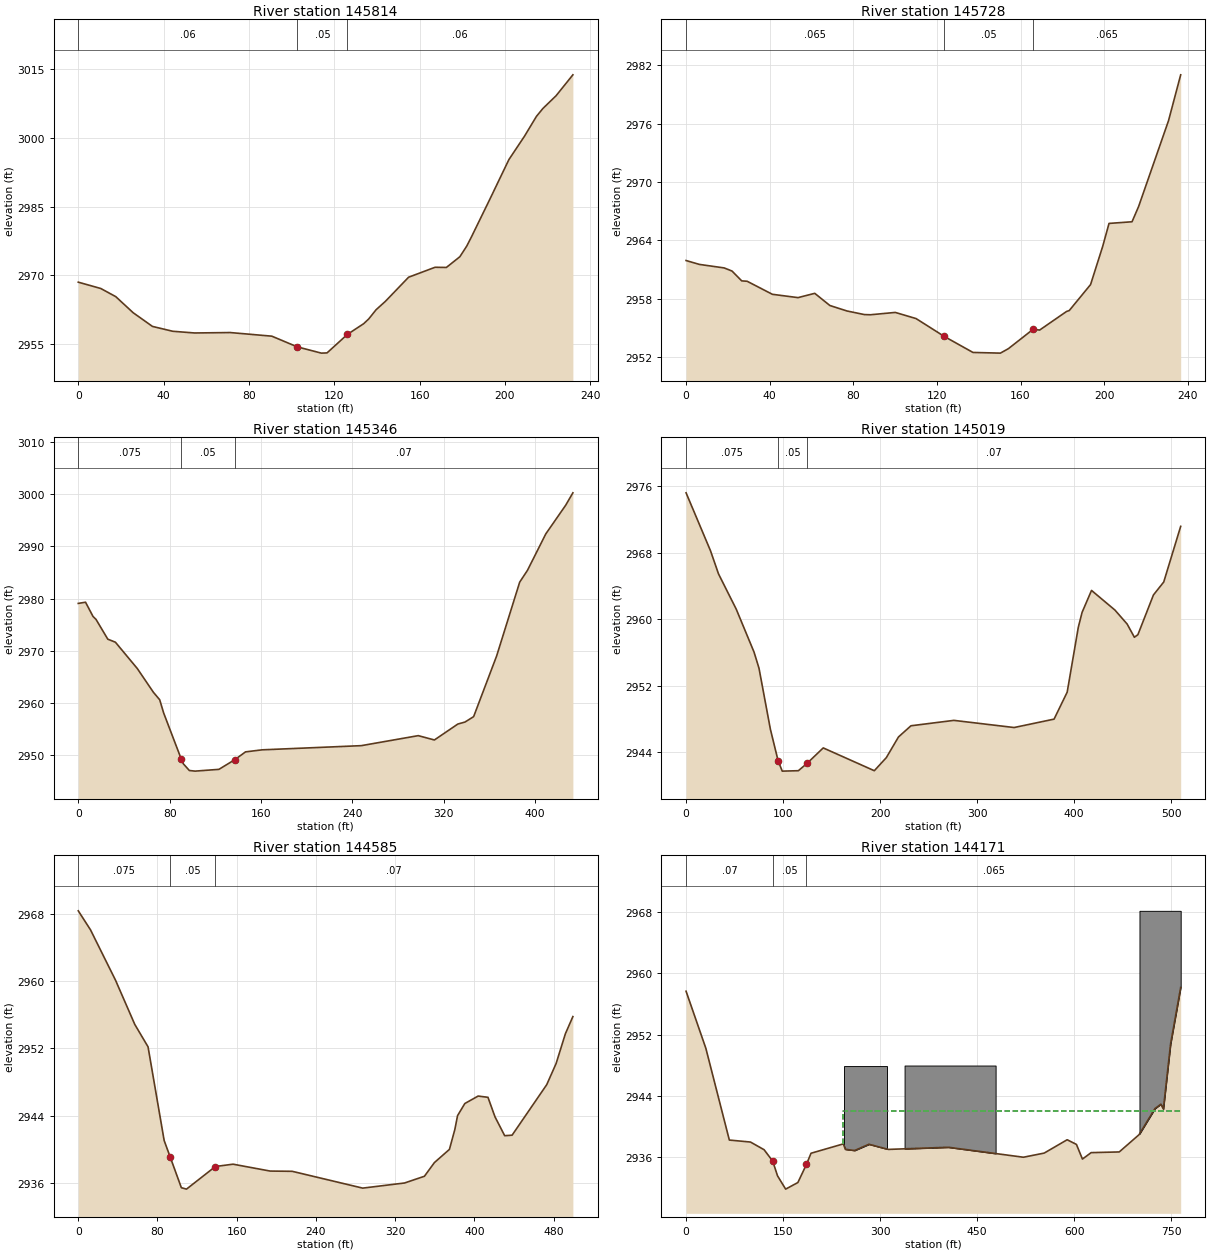
Type RM Length L Ch R = 1 ,145814  ,92.73,85.81,76.68
BEGIN DESCRIPTION:
145736.3
END DESCRIPTION:
XS GIS Cut Line= 6
  949681.4598472  803266.6014968  949634.0640725   803299.414035
  949590.3133387  803339.5187036  949574.5154299  803361.3930463
  949564.7929308  803400.2820185  949558.7164969  803447.6777932
#Sta/Elev= 30
       0 2968.54   10.54 2967.16   17.58 2965.38   25.73 2961.87   34.78 2958.88
    44.3 2957.82   54.52 2957.45   71.26 2957.54   90.74 2956.75  102.71 2954.41
  113.95 2953.05  116.62  2953.1  126.13 2957.13   133.8 2959.48  136.17 2960.52
   139.6 2962.52  143.98 2964.36  154.84 2969.62  167.25 2971.79  172.54 2971.75
  178.87 2974.09  182.09 2976.41  184.41 2978.52  193.05 2986.76  201.84 2995.28
  209.14 3000.38  214.77 3004.73  217.81 3006.46  223.96 3009.23  231.85  3013.8
#Mann= 3 , 0 , 0
       0     .06       0  102.71     .05       0  126.13     .06       0
Bank Sta=102.71,126.13
Exp/Cntr=0.3,0.1

Type RM Length L Ch R = 1 ,145728  ,464.04,382.66,158.79
BEGIN DESCRIPTION:
145650.5
END DESCRIPTION:
XS GIS Cut Line= 6
  949614.6190743  803227.7125246  949573.2997334  803256.8789977
  949540.4871952   803283.615102  949518.6118283  803305.4904689
  949490.6610517  803341.9490723  949490.6610517  803408.7888211
#Sta/Elev= 30
       0 2961.93    6.39 2961.53   18.23 2961.17   21.98 2960.85   26.62 2959.84
   29.22  2959.8    41.3 2958.46   53.56 2958.12   61.57 2958.56    68.8 2957.31
   76.95 2956.75   85.27 2956.38   88.21 2956.36  100.08  2956.6  110.02 2955.97
  123.56 2954.13  137.25 2952.49  150.38 2952.42  154.22 2952.88  165.99 2954.86
  169.16 2954.79  182.04  2956.7  183.31 2956.79  193.52 2959.46   199.3 2963.37
  202.35 2965.74  213.35 2965.91  216.51 2967.48  230.81 2976.29  236.63    2981
#Mann= 3 , 0 , 0
       0    .065       0  123.56     .05       0  165.99    .065       0
Bank Sta=123.56,165.99
Exp/Cntr=0.3,0.1

Type RM Length L Ch R = 1 ,145346  ,323.66,326.51,413.55
BEGIN DESCRIPTION:
145267.8
END DESCRIPTION:
XS GIS Cut Line= 6
  949076.2509224  803242.2957612  949166.1817345  803345.5941133
  949211.1471405   803379.622348  949254.8968501  803392.9909123
  949318.0915579  803417.2956237  949432.3270814  803470.7678324
#Sta/Elev= 30
       0 2979.06    6.36 2979.29   12.89 2976.57   15.53    2976   25.86  2972.2
   32.49 2971.63   51.71 2966.57   65.77 2962.03   71.28  2960.6   74.75 2958.06
   90.23 2949.19   92.07  2948.3   97.23 2947.04  102.27 2946.92  123.12 2947.26
  137.01 2949.11  146.43 2950.61  160.95    2951  247.75  2951.8  297.62 2953.72
  311.75 2952.89  332.26 2955.94  338.58 2956.33  346.09 2957.36   366.2 2968.97
  386.41 2983.13  393.28 2985.42  409.27 2992.38  426.64 2997.86  432.98 3000.25
#Mann= 3 , 0 , 0
       0    .075       0   90.23     .05       0  137.01     .07       0
Bank Sta=90.23,137.01
Exp/Cntr=0.3,0.1

Type RM Length L Ch R = 1 ,145019  ,410.06,434.05,472.81
BEGIN DESCRIPTION:
144941.3
END DESCRIPTION:
XS GIS Cut Line= 6
  948827.6957916  803447.1124483  948882.3836967  803513.9521971
  948944.6668882  803589.9071088  948997.8349167  803644.5950139
  949069.2322469  803757.0075048  949114.8049891   803863.344586
#Sta/Elev= 30
       0 2975.18   25.17 2968.22   33.45 2965.43   51.65 2961.21   70.07 2956.03
   75.15  2954.1   86.91 2946.76   94.86 2942.97   99.12 2941.73  115.72 2941.78
  124.66 2942.66  141.36 2944.52     194 2941.78  206.35 2943.35  218.92 2945.84
  231.75 2947.18  275.98 2947.83  338.06 2946.97  379.24 2947.98  392.75 2951.22
  404.22 2959.02  408.13 2960.82  417.84 2963.45  441.95 2961.09  454.54 2959.41
  462.01 2957.82  465.63 2958.13  481.67 2962.91  492.25 2964.46  509.72 2971.15
#Mann= 3 , 0 , 0
       0    .075       0   94.86     .05       0  124.66     .07       0
Bank Sta=94.86,124.66
Exp/Cntr=0.3,0.1

Type RM Length L Ch R = 1 ,144585  ,368.62,414.38,470.14
BEGIN DESCRIPTION:
144507.3
END DESCRIPTION:
XS GIS Cut Line= 5
   948488.937418  803633.9609985  948504.1279907  803714.4734917
  948543.6242989  803798.0236897   948639.328389  803962.0863809
  948712.2445716  804076.0187485
#Sta/Elev= 30
       0 2968.37   12.29 2966.12   37.67  2960.1   57.07 2954.85   70.47 2952.18
   86.76 2941.02   92.892939.048  104.11 2935.41   109.3 2935.24  138.48 2937.93
  156.31 2938.21   193.8 2937.39  216.11 2937.36  287.29 2935.36  329.52 2935.97
  349.59 2936.77   359.7  2938.4  374.86 2939.97  380.35 2942.35  383.08 2943.99
  390.41 2945.43  403.85 2946.32  413.79 2946.17  420.87 2943.85  430.67  2941.6
  438.15 2941.66  473.11 2947.67  482.63  2950.2  491.99 2953.74  499.55 2955.78
#Mann= 3 , 0 , 0
       0    .075       0   92.89     .05       0  138.48     .07       0
#XS Ineff= 2 , 0
       0                  413.79       0 2946.17
Permanent Ineff=
       F       F
Bank Sta=92.89,138.48
Exp/Cntr=0.3,0.1

Type RM Length L Ch R = 1 ,144171  ,492.88,439.63,271.78
BEGIN DESCRIPTION:
144092.9
END DESCRIPTION:
XS GIS Cut Line= 6
  948177.5224849  803681.0536173  948116.7581458  803799.5425421
  948145.6214629   803981.834535  948180.5601897  804113.9962043
  948303.6077202  804309.9588933  948330.9511607  804382.8761001
#Sta/Elev= 30
       0 2957.65   30.58 2950.21   66.92 2938.24   99.59 2937.98  120.65 2936.98
  133.99 2935.49  141.45 2933.57  153.99 2931.84  172.89  2932.7  186.112935.059
  193.21 2936.52  243.22 2937.74  246.27 2937.03  260.75 2936.88  282.83 2937.69
   312.7 2937.02  405.45  2937.3  521.64    2936  553.77 2936.54  589.28 2938.28
  603.63 2937.67   612.9 2935.76  626.37  2936.6  669.83 2936.69  700.44 2938.94
  725.09 2942.35  734.25 2942.92  738.04 2942.29  749.18 2950.76  764.82 2958.14
#Mann= 3 , 0 , 0
       0     .07       0  133.99     .05       0  186.11    .065       0
#XS Ineff= 2 , 0
       0                  243.22       0    2942
Permanent Ineff=
       F       F
#Block Obstruct= 3 ,-1
  701.09  764.822968.136  337.86  478.64 2947.96  244.22  310.642947.889
Bank Sta=133.99,186.11
Exp/Cntr=0.3,0.1

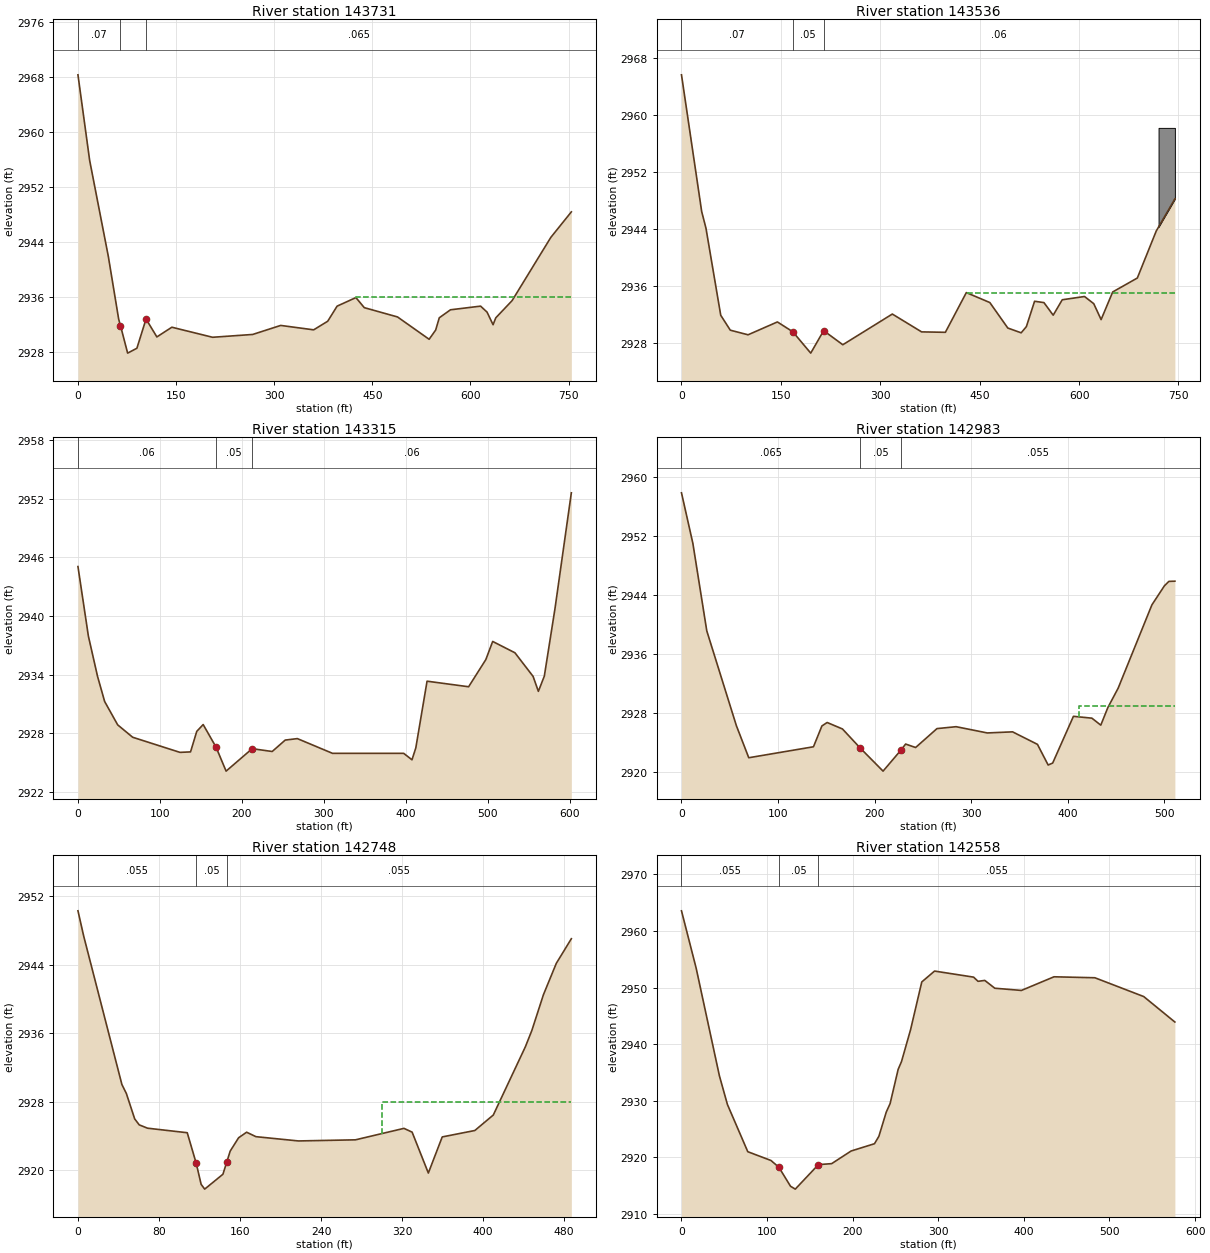
Type RM Length L Ch R = 1 ,143731  ,221.85,194.95,74.64
BEGIN DESCRIPTION:
143653.3
END DESCRIPTION:
XS GIS Cut Line= 5
  947665.5862571   803872.459749  947691.4108452  803919.5513436
  947733.9458825  803966.6429382  947891.9321398  804153.4925126
  948092.4524102  804490.7320338
#Sta/Elev= 30
       0 2968.28   17.86 2955.87   46.44 2941.92   62.27  2932.8   65.01 2931.88
   75.94 2927.89    90.1  2928.6  104.09 2932.84  120.62 2930.24  143.51 2931.65
  205.84 2930.19   267.1  2930.6  309.92 2931.91   360.3 2931.27  381.82 2932.52
  396.15 2934.71  424.91 2935.95  437.68 2934.49  488.49 2933.14  536.81  2929.9
  546.81 2931.24  552.33 2933.02  569.45 2934.18  615.46 2934.71  625.36 2933.84
  634.55 2932.01  638.67 2933.01  663.56  2935.5  722.78 2944.68   754.2 2948.39
#Mann= 3 , 0 , 0
       0     .07       0   65.01     .05       0  104.09    .065       0
#XS Ineff= 2 , 0
       0                  424.91       0    2936
Permanent Ineff=
       F       F
Bank Sta=65.01,104.09
Exp/Cntr=0.3,0.1

Type RM Length L Ch R = 1 ,143536  ,152.45,220.85,255.77
BEGIN DESCRIPTION:
143458.3
END DESCRIPTION:
XS GIS Cut Line= 6
  947510.6387289  804021.3308433  947548.6161847  804077.5376009
  947674.7014201  804123.1103431  947802.3055079   804212.736975
  947907.1227125  804329.7080716  948037.7655293  804516.5566218
#Sta/Elev= 30
       0 2965.69   30.48 2946.44    36.9 2944.12   59.22 2931.85   73.64 2929.75
  100.47  2929.1  144.73 2930.91  168.012929.523  195.03 2926.52  214.542929.682
  243.46  2927.7  318.17 2932.02  362.33 2929.51  398.22 2929.45  429.85 2935.04
  465.29 2933.64  492.46 2930.05   512.6 2929.38  520.45 2930.25  532.84 2933.82
  546.97 2933.63  560.93 2931.86  574.59 2934.03  608.19 2934.49  622.13 2933.48
  633.24 2931.24  650.74 2935.13  687.89 2937.09   716.4  2943.7  744.56 2948.22
#Mann= 3 , 0 , 0
       0     .07       0  168.01     .05       0  214.54     .06       0
#XS Ineff= 2 , 0
       0                  431.44       0    2935
Permanent Ineff=
       F       F
#Block Obstruct= 1 ,-1
  719.91  744.562958.224
Bank Sta=168.01,214.54
Exp/Cntr=0.3,0.1

Type RM Length L Ch R = 1 ,143315  ,276.26,332.39,337.45
BEGIN DESCRIPTION:
143237.5
END DESCRIPTION:
XS GIS Cut Line= 6
  947405.8205001  804133.7443584  947454.4319713  804203.6228362
  947542.5397508  804300.8447545  947626.0899488  804399.5865494
   947703.563713  804477.0603135   947796.229074  804590.9926811
#Sta/Elev= 30
       0 2945.07   12.72 2937.95   23.88 2933.83   32.57 2931.25   48.46 2928.86
   66.74 2927.59  124.49 2926.04  137.39 2926.09  144.97 2928.19  152.81 2928.89
   168.52926.578  180.78 2924.12   212.62926.418  237.03 2926.13  252.93  2927.3
  267.76 2927.45  310.69 2925.94  397.52 2925.94  407.62 2925.28   412.3  2926.5
  426.02 2933.33  476.74 2932.76  497.73 2935.54  506.11  2937.4  533.25 2936.24
  555.43 2933.82  561.86 2932.29  569.13 2933.85  582.13 2940.76   602.1 2952.62
#Mann= 3 , 0 , 0
       0     .06       0   168.5     .05       0   212.6     .06       0
Bank Sta=168.5,212.6
Exp/Cntr=0.3,0.1

Type RM Length L Ch R = 1 ,142983  ,293.17,235.11,157.84
BEGIN DESCRIPTION:
142905.1
END DESCRIPTION:
XS GIS Cut Line= 6
  947225.0483838  804340.3410628   947305.560877  804483.1367474
  947329.8655884  804559.0916591  947358.7289055  804609.2219828
  947428.6073833  804663.9088637  947518.2340152  804744.4213569
#Sta/Elev= 30
       0 2957.91   11.78 2951.04   26.18 2939.15   56.82 2926.26   69.65  2921.9
  136.65 2923.39  145.39 2926.22  150.81 2926.69  166.69 2925.81  185.142923.207
   208.7 2920.08  226.92 2922.89  232.06 2923.76  242.42 2923.29  264.53 2925.86
  284.32 2926.12  316.64 2925.27  342.77 2925.42  368.56 2923.72  379.64 2920.91
  384.34 2921.18  405.81 2927.53  424.93 2927.28  434.14 2926.33  441.45 2928.72
   452.1 2931.35  487.06 2942.68  500.01 2945.27  504.61 2945.87  510.85  2945.9
#Mann= 3 , 0 , 0
       0    .065       0  185.14     .05       0  226.92    .055       0
#XS Ineff= 2 , 0
       0                  411.28       0    2929
Permanent Ineff=
       F       F
Bank Sta=185.14,226.92
Exp/Cntr=0.3,0.1

Type RM Length L Ch R = 1 ,142748  ,194.53,190.01,180.59
BEGIN DESCRIPTION:
142670.0
END DESCRIPTION:
XS GIS Cut Line= 5
  947012.3752455  804566.6869454  947143.0170382  804636.5654232
   947238.720104  804694.2910332  947352.6524716  804791.5129515
  947408.8592291  804844.6820042
#Sta/Elev= 30
       0 2950.32    5.72 2947.34   43.39 2930.02   47.76 2928.98      56 2926.01
   60.46 2925.31   68.72 2924.92  107.89 2924.39  116.75 2920.81   121.6 2918.36
  125.11  2917.8  143.11 2919.54  147.01    2921  150.27 2922.24  158.58  2923.8
  166.49 2924.45  175.69 2923.93  217.61 2923.43  273.93 2923.56  321.83  2924.9
  329.88 2924.46   345.9 2919.68  359.61  2923.9   391.8 2924.65  410.03 2926.46
  441.71 2934.44  448.11 2936.35  459.49 2940.51  472.21 2944.18  487.07 2947.06
#Mann= 3 , 0 , 0
       0    .055       0  116.75     .05       0  147.01    .055       0
#XS Ineff= 2 , 0
       0                  299.69       0    2928
Permanent Ineff=
       F       F
Bank Sta=116.75,147.01
Exp/Cntr=0.5,0.3

Type RM Length L Ch R = 1 ,142558  ,99.62,101.34,104.1
BEGIN DESCRIPTION:
142480
END DESCRIPTION:
XS GIS Cut Line= 5
  946912.1145982  804736.8260706  946988.0695099  804770.2459449
  947056.4281111  804802.1469669  947301.0032955   804914.560482
  947427.0885308  804993.5530986
#Sta/Elev= 30
       0 2963.56   17.11 2953.45   44.31 2934.41   53.68 2929.35   77.44 2921.02
   104.5 2919.47  113.75 2918.28  127.36 2914.92  132.91 2914.41  159.96 2918.74
  175.43 2918.91  198.11 2921.14  225.46 2922.43   230.6 2923.74  239.22 2928.02
  243.69 2929.51  253.13 2935.57  257.01 2936.93  267.62 2942.57  280.71    2951
  295.64 2952.92  341.21 2951.85  346.44 2951.11  354.32 2951.27  366.03 2949.89
  397.07  2949.5   435.2 2951.91  482.93 2951.74  539.99 2948.42  576.38 2943.92
#Mann= 3 , 0 , 0
       0    .055       0  113.75     .05       0  159.96    .055       0
Bank Sta=113.75,159.96
Exp/Cntr=0.5,0.3

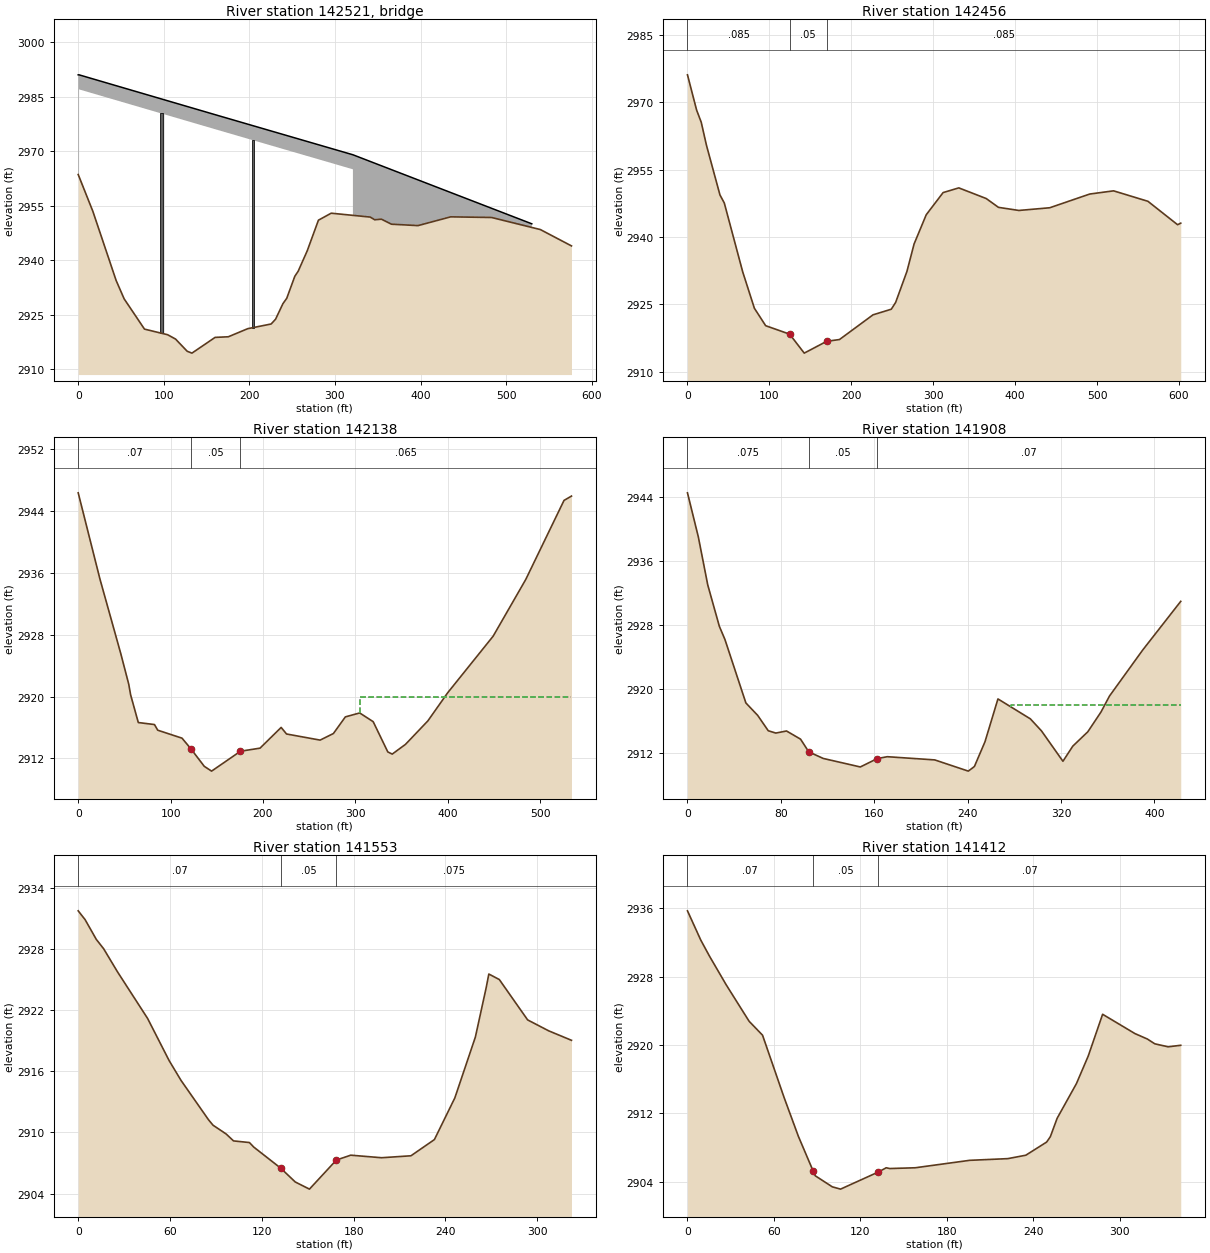
Type RM Length L Ch R = 3 ,142521  ,,,
BEGIN DESCRIPTION:
142442  FBSTR_1232  Deck=contour+3' guiderail
END DESCRIPTION:
Bridge Culvert--1,0,-1,-1, 0
Deck Dist Width WeirC Skew NumUp NumDn MinLoCord MaxHiCord MaxSubmerge Is_Ogee
21,40,2.6,0, 5, 5, 2980.52, , 0.95, 0, 3,3,,
       0       1   160.5     321     530
    2991    2991    2980    2969    2950
            2987    2976    2965
       0       1   160.5     321     530
    2991    2991    2980    2969    2950
            2987    2976    2965
Pier Skew, UpSta & Num, DnSta & Num=  ,97, 2 ,107, 2 , 0 , 0 , 0 ,,
       3       3
    2900 3038.64
       3       3
    2900 3038.64
Pier Skew, UpSta & Num, DnSta & Num=  ,204, 2 ,214, 2 , 0 , 0 , 0 ,,
       3       3
    2900 3038.64
       3       3
    2900 3038.64
BR Coef=-1 , 0 , 0 ,, 0 ,,,0.8,-1,,0,
WSPro=,,,, 1 ,,,, 0 ,,,, 0 ,,,,-1 ,-1 ,-1 , 0 , 0 , 0 , 0 , 0
BC Design=,, 0 ,, 0 ,,,,,,

Type RM Length L Ch R = 1 ,142456  ,322.23,319.08,291.23
BEGIN DESCRIPTION:
142378.6
END DESCRIPTION:
XS GIS Cut Line= 4
  946855.9078407  804812.7809823  946919.7098846  804850.7584381
  947130.8641704  804946.4615039  947402.7827952  805063.4315763
#Sta/Elev= 30
       0 2976.12   11.14 2968.27   16.78 2965.56   23.15 2960.44   39.66 2949.35
   44.93 2947.57   67.42 2932.21   81.67 2924.11   95.45 2920.22  124.68 2918.34
  142.53 2914.11  169.88 2916.74  185.56 2917.14  226.44 2922.64  248.82  2923.9
  254.11 2925.42  267.88 2932.32  276.58 2938.42  291.42 2944.94  312.02 2949.88
  331.17 2950.93  364.59 2948.56  379.61 2946.59   404.5  2945.9  442.17  2946.5
  491.05 2949.56   520.1 2950.27  562.02 2947.94  598.24 2942.72  602.09 2943.07
#Mann= 3 , 0 , 0
       0    .085       0  124.68     .05       0  169.88    .085       0
Bank Sta=124.68,169.88
Exp/Cntr=0.5,0.3

Type RM Length L Ch R = 1 ,142138  ,304.91,229.95,189.16
BEGIN DESCRIPTION:
142059.5
END DESCRIPTION:
XS GIS Cut Line= 4
  946754.1283409  805133.3100541   946863.503127  805169.7686576
  946933.3816048  805200.1508271   947273.659855  805238.1282829
#Sta/Elev= 30
       0 2946.33   23.41 2935.24   46.12 2925.53   54.71 2921.59   56.76 2920.21
   65.05 2916.64   82.55 2916.38   86.08 2915.65  112.37 2914.62  122.132913.225
  136.45 2910.98  144.37 2910.36   175.6 2912.93   196.8 2913.33  219.67 2916.01
  225.47 2915.16  261.85 2914.37  276.21 2915.22  289.15 2917.37  304.66 2917.88
  319.28 2916.75   335.1 2912.84  339.88 2912.56  354.24 2913.82   378.5 2916.86
  399.78 2920.47  449.09  2927.8  484.35 2935.12  525.81 2945.35  533.88 2945.91
#Mann= 3 , 0 , 0
       0     .07       0  122.13     .05       0   175.6    .065       0
#XS Ineff= 2 , 0
       0                  304.66       0    2920
Permanent Ineff=
       F       F
Bank Sta=122.13,175.6
Exp/Cntr=0.3,0.1

Type RM Length L Ch R = 1 ,141908  ,292.18,354.1,331.19
BEGIN DESCRIPTION:
141829.6
END DESCRIPTION:
XS GIS Cut Line= 6
  946772.3576426  805477.3859475  946813.3728034  805427.2556239
  946877.1748472  805401.4310358  946974.3977897  805398.3923068
  947051.8715538  805402.9498883  947165.8039214  805409.0263222
#Sta/Elev= 30
       0 2944.49    9.31 2938.98   17.38 2932.99   27.33 2927.82   32.07  2926.2
   50.02 2918.27   60.13 2916.72   69.19  2914.8   75.68 2914.51   84.84 2914.77
   96.87 2913.75  103.94 2912.16  116.35 2911.34  148.07 2910.28  162.66 2911.33
  171.18 2911.56  211.84 2911.16   240.6 2909.76  245.82 2910.34  254.87 2913.43
  265.97 2918.77  293.76 2916.28  303.27 2914.78  321.65 2910.99   330.1 2912.88
  342.96 2914.67  354.26 2917.14  361.52 2919.13  389.96 2924.87  422.57 2930.95
#Mann= 3 , 0 , 0
       0    .075       0  103.94     .05       0  162.66     .07       0
#XS Ineff= 2 , 0
       0                   277.5       0    2918
Permanent Ineff=
       F       F
Bank Sta=103.94,162.66
Exp/Cntr=0.3,0.1

Type RM Length L Ch R = 1 ,141553  ,192.91,141.94,59.02
BEGIN DESCRIPTION:
141475.5
END DESCRIPTION:
XS GIS Cut Line= 6
  946792.1057968  805685.5015043  946868.0607085  805731.0752707
  946916.6711555  805746.2658433  946948.5732016  805746.2658433
  947048.8328248  805734.1129755  947095.9254436  805717.4025262
#Sta/Elev= 30
       0 2931.74    4.53 2930.87   11.82 2928.94   16.63 2928.02    25.7 2925.75
   45.37 2921.18   59.46 2917.04   67.18 2915.11   85.14 2911.25   88.12 2910.71
   96.68 2909.85  101.51 2909.17   111.9 2909.01  114.77 2908.56  132.33  2906.5
  141.86 2905.14  151.13 2904.44   168.7 2907.29   178.1 2907.77  198.23 2907.52
  217.46 2907.71  232.79  2909.3  246.15 2913.39  259.57 2919.36  266.64 2924.21
  268.36 2925.54  275.21    2925  293.72 2921.04  307.45 2919.97  322.37 2919.04
#Mann= 3 , 0 , 0
       0     .07       0  132.33     .05       0   168.7    .075       0
Bank Sta=132.33,168.7
Exp/Cntr=0.3,0.1

Type RM Length L Ch R = 1 ,141412  ,293.23,239.64,214.84
BEGIN DESCRIPTION:
141333.5
END DESCRIPTION:
XS GIS Cut Line= 5
  946824.0068187  805933.1143935  946899.9617304  805890.5803804
   946947.053325  805863.2359157  947067.0621265  805790.3197331
  947117.1924501  805756.8998587
#Sta/Elev= 30
       0 2935.71    9.21 2932.29   15.22 2930.42   26.82 2927.06   42.76 2922.78
   52.07 2921.15    67.1 2913.82   76.96  2909.3   87.05  2905.3   88.58  2904.7
  100.45  2903.4  106.19 2903.13  132.312905.126  137.87 2905.63  140.27 2905.54
  157.98 2905.63  195.72  2906.5  222.25  2906.7   234.7  2907.1  249.15 2908.64
  251.72 2909.27  256.45 2911.43  269.84 2915.49  278.02 2918.72  287.98  2923.6
   310.4 2921.34  319.05  2920.7  324.19 2920.14  333.46 2919.79  342.18 2919.97
#Mann= 3 , 0 , 0
       0     .07       0   87.05     .05       0  132.31     .07       0
Bank Sta=87.05,132.31
Exp/Cntr=0.3,0.1

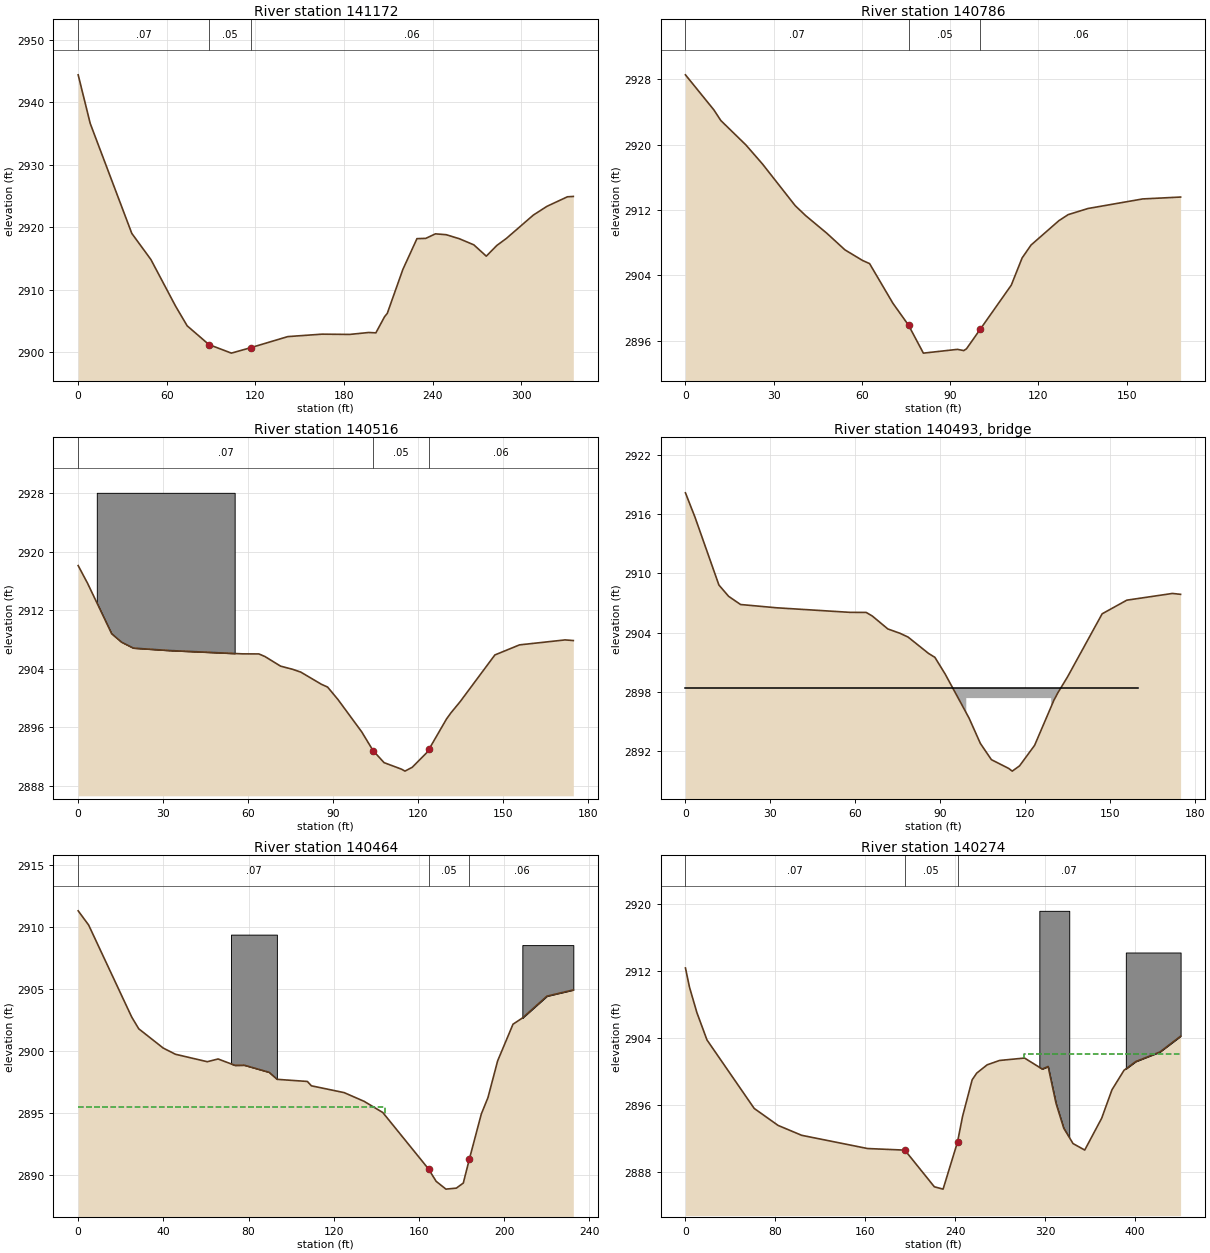
Type RM Length L Ch R = 1 ,141172  ,314.09,385.76,386.21
BEGIN DESCRIPTION:
141093.9
END DESCRIPTION:
XS GIS Cut Line= 5
   947071.619708  806127.5592542  947080.7338467  806062.2383579
   947094.405567  806036.4137699  947143.0170382  805980.2070123
  947293.4080091  805910.3285345
#Sta/Elev= 30
       0 2944.43    8.16 2936.63   36.32    2919   49.25 2914.81   65.95 2907.34
   73.81 2904.18   88.55 2901.17  103.77  2899.8  116.79 2900.67  141.96 2902.45
     165 2902.84  183.97  2902.8  196.76 2903.11  201.59 2903.05  207.52 2905.65
  209.32 2906.17  219.88 2913.22  229.44 2918.16  235.36  2918.2  241.95 2918.93
  249.26 2918.79  258.18 2918.14  267.91 2917.17  276.38 2915.35  283.53 2917.07
  289.97 2918.19  308.19 2921.93  317.44 2923.34  331.32 2924.87  335.32 2924.93
#Mann= 3 , 0 , 0
       0     .07       0   88.55     .05       0  116.79     .06       0
Bank Sta=88.55,116.79
Exp/Cntr=0.3,0.1

Type RM Length L Ch R = 1 ,140786  ,217.42,269.66,277.8
BEGIN DESCRIPTION:
140708.2
END DESCRIPTION:
XS GIS Cut Line= 3
  947267.5834211  806323.5229674  947355.6912006   806287.064364
  947427.5176604   806274.129026
#Sta/Elev= 26
       0 2928.53    9.67 2924.24   12.03 2922.94   20.54 2919.96    26.2 2917.62
   37.33 2912.52   40.87 2911.31   47.98 2909.18   54.23 2907.12   60.23 2905.82
    62.6 2905.44   70.55 2900.58   75.84 2897.91   80.89 2894.49   92.46 2894.95
   94.63  2894.8   95.55 2895.02  100.24 2897.42  110.77  2902.8  114.46 2906.13
  117.49 2907.71  126.96 2910.69  130.12 2911.43  136.86 2912.18  155.47 2913.35
  168.34 2913.58
#Mann= 3 , 0 , 0
       0     .07       0   75.84     .05       0  100.24     .06       0
Bank Sta=75.84,100.24
Exp/Cntr=0.5,0.3

Type RM Length L Ch R = 1 ,140516  ,88.17,52.54,53.45
BEGIN DESCRIPTION:
140438.5
END DESCRIPTION:
XS GIS Cut Line= 5
  947323.7901787  806501.2573788  947366.3241918  806540.7536871
   947411.896934  806548.3489734  947452.9131189  806548.3489734
  947482.3397325  806544.9200335
#Sta/Elev= 30
       0 2918.13    3.37 2915.67   11.82 2908.81   15.28 2907.66   19.48 2906.84
   32.18 2906.51   58.04 2906.05   63.84 2906.04   65.99 2905.68   71.49 2904.37
    75.8 2903.93   78.64 2903.55   85.85  2901.9   88.11  2901.5   91.74 2899.81
  100.16 2895.37  104.17  2892.8  108.06 2891.16  114.19 2890.27  115.43    2890
     118 2890.53  123.33 2892.61  123.87 2892.97  130.12 2897.15  131.55 2897.92
  134.98 2899.54  147.18  2905.9  155.89 2907.28  172.01 2907.96  174.89 2907.87
#Mann= 3 , 0 , 0
       0     .07       0  104.17     .05       0  123.87     .06       0
#XS Ineff= 2 , 0
       0   89.19 2898.38  139.19       0 2898.38
Permanent Ineff=
       F       F
#Block Obstruct= 1 ,-1
    6.58   55.27 2928.09
Bank Sta=104.17,123.87
Exp/Cntr=0.5,0.3

Type RM Length L Ch R = 3 ,140493  ,,,
Node Photo=H:\PROJ\06-0741\CE\GIS\DATA\FRENCH_BROAD_RIVER\SHAPEFILES\survey_data\photos\FBSTR_1779.JPG
BEGIN DESCRIPTION:
140413.6  FBSTR_1779
END DESCRIPTION:
Bridge Culvert--1,0,-1,-1, 0
Deck Dist Width WeirC Skew NumUp NumDn MinLoCord MaxHiCord MaxSubmerge Is_Ogee
15,12,2.6,0, 7, 7, , , 0.95, 0, 1,1,,
       0   99.19   99.19  114.19  129.19  129.19     160
 2898.38 2898.38 2898.38 2898.38 2898.38 2898.38 2898.38
                 2897.38 2897.38 2897.38
       0     159     159     174     189     189     220
  2898.3 2898.38 2898.38 2898.38 2898.38 2898.38 2898.38
                 2897.38 2897.38 2897.38
BR Coef=-1 , 0 , 0 ,, 0 ,,,0.8,0,,0,
WSPro=,,,, 1 ,,,, 0 ,,,, 0 ,,,,-1 ,-1 ,-1 , 0 , 0 , 0 , 0 , 0
BC Design=,, 0 ,, 0 ,,,,,,

Type RM Length L Ch R = 1 ,140464  ,167.58,190.23,216.55
BEGIN DESCRIPTION:
140386
END DESCRIPTION:
XS GIS Cut Line= 4
  947267.5834211  806560.5018412  947325.3090311  806606.0745834
  947436.2026696  806599.9981495  947484.0009454  806598.9125234
#Sta/Elev= 30
       0  2911.3     4.9 2910.16   25.15 2902.74   28.44  2901.8   39.91 2900.25
   45.67 2899.75   60.61 2899.15   65.68 2899.37   73.55 2898.86   77.97 2898.87
    89.6  2898.3   93.41 2897.73  107.59 2897.56  109.47 2897.21  124.87 2896.66
  134.21 2895.96  142.99 2895.06  164.47 2890.51  168.02 2889.52  172.63 2888.89
  177.51 2888.97  180.78 2889.38  183.61  2891.3  189.23 2894.94  192.35 2896.26
   196.9 2899.22  204.11 2902.17  208.61 2902.68  220.05 2904.43  232.42 2904.93
#Mann= 3 , 0 , 0
       0     .07       0  164.47     .05       0  183.61     .06       0
#XS Ineff= 2 , 0
       0     144 2895.48     204       0    2895
Permanent Ineff=
       F       F
#Block Obstruct= 2 ,-1
  208.49  232.422908.539   71.74   93.272909.385
Bank Sta=164.47,183.61
Exp/Cntr=0.5,0.3

Type RM Length L Ch R = 1 ,140274  ,254.3,345.96,366.63
BEGIN DESCRIPTION:
140195.7
END DESCRIPTION:
XS GIS Cut Line= 4
  947194.6662143  806732.1598188  947314.6750157    806780.77129
  947443.7979559  806792.9241578  947606.3417947  806873.4356268
#Sta/Elev= 30
       0 2912.33    3.59 2910.04   10.18    2907   19.17 2903.73   61.18 2895.55
   82.46 2893.52  103.42 2892.34  162.04 2890.76   195.2 2890.57  221.45 2886.19
  229.24 2885.91  242.07 2891.53  246.56  2894.6   255.1 2898.97  259.16 2899.77
  268.44 2900.76  279.42 2901.28  301.73 2901.57  317.41 2900.26  322.69 2900.56
  329.76 2896.14  336.56  2893.2  344.88 2891.35  355.27 2890.58  370.37 2894.39
  379.47 2897.77  390.23 2900.11  400.61 2901.15  421.98 2902.28  440.56 2904.18
#Mann= 3 , 0 , 0
       0     .07       0   195.2     .05       0  242.07     .07       0
#XS Ineff= 2 , 0
       0                  301.42       0    2902
Permanent Ineff=
       F       F
#Block Obstruct= 2 ,-1
  391.83  440.562914.179  314.87  341.482919.158
Bank Sta=195.2,242.07
Exp/Cntr=0.3,0.1