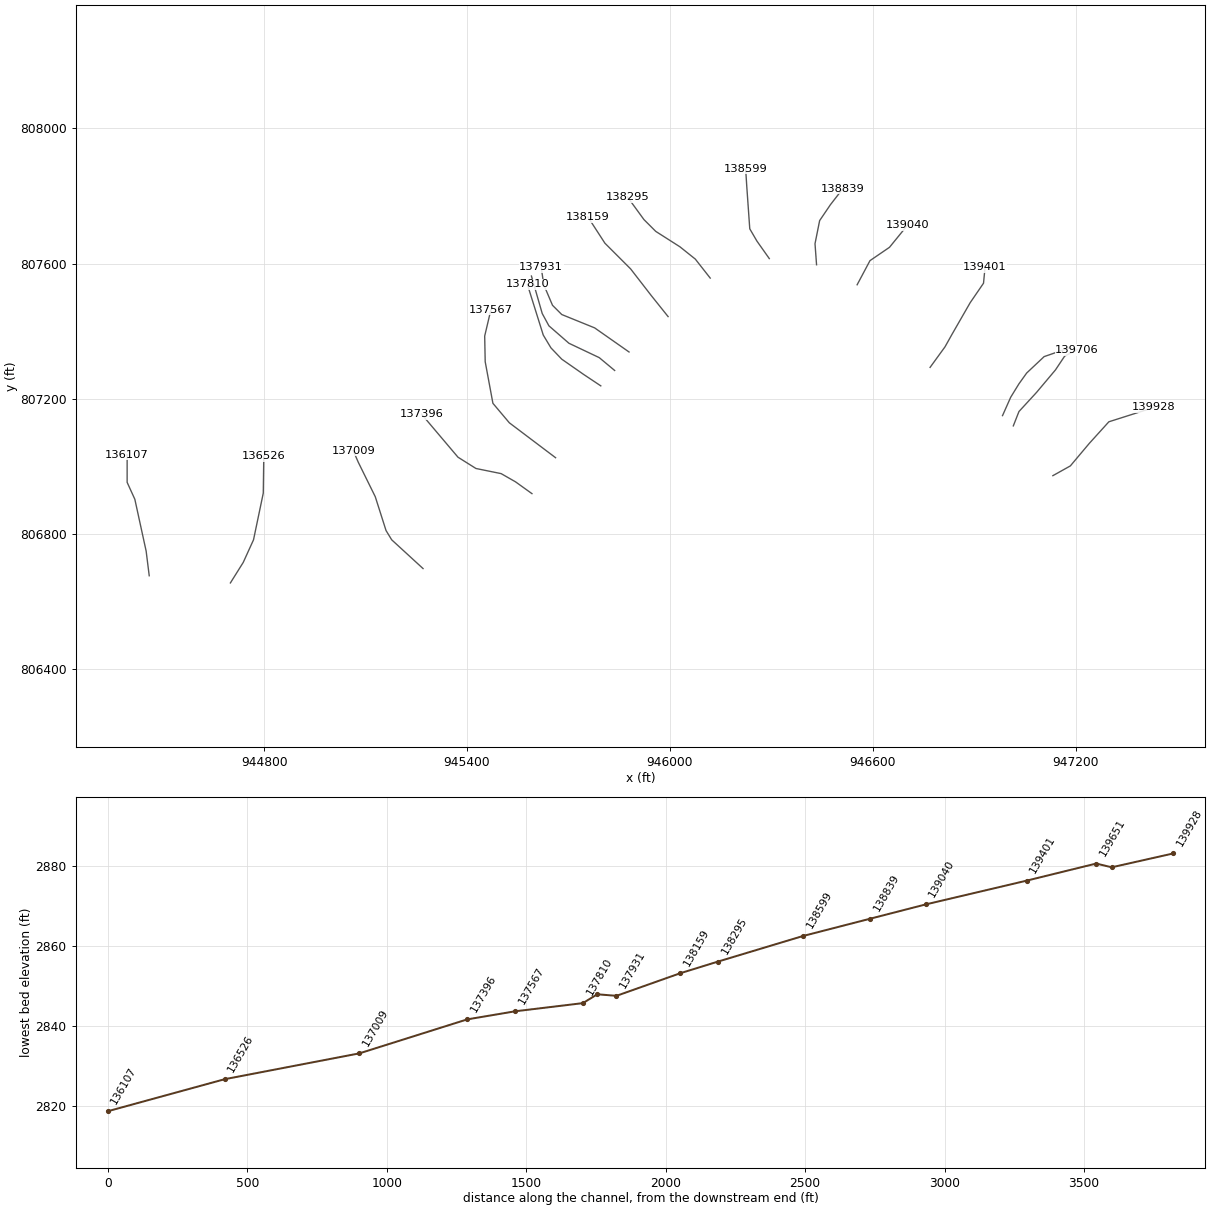
HEC-RAS study lds_big_laurel_crk.prj: lds_big_laurel_crk

--- lds_big_laurel_crk.g20 (geometry) --- (continued)

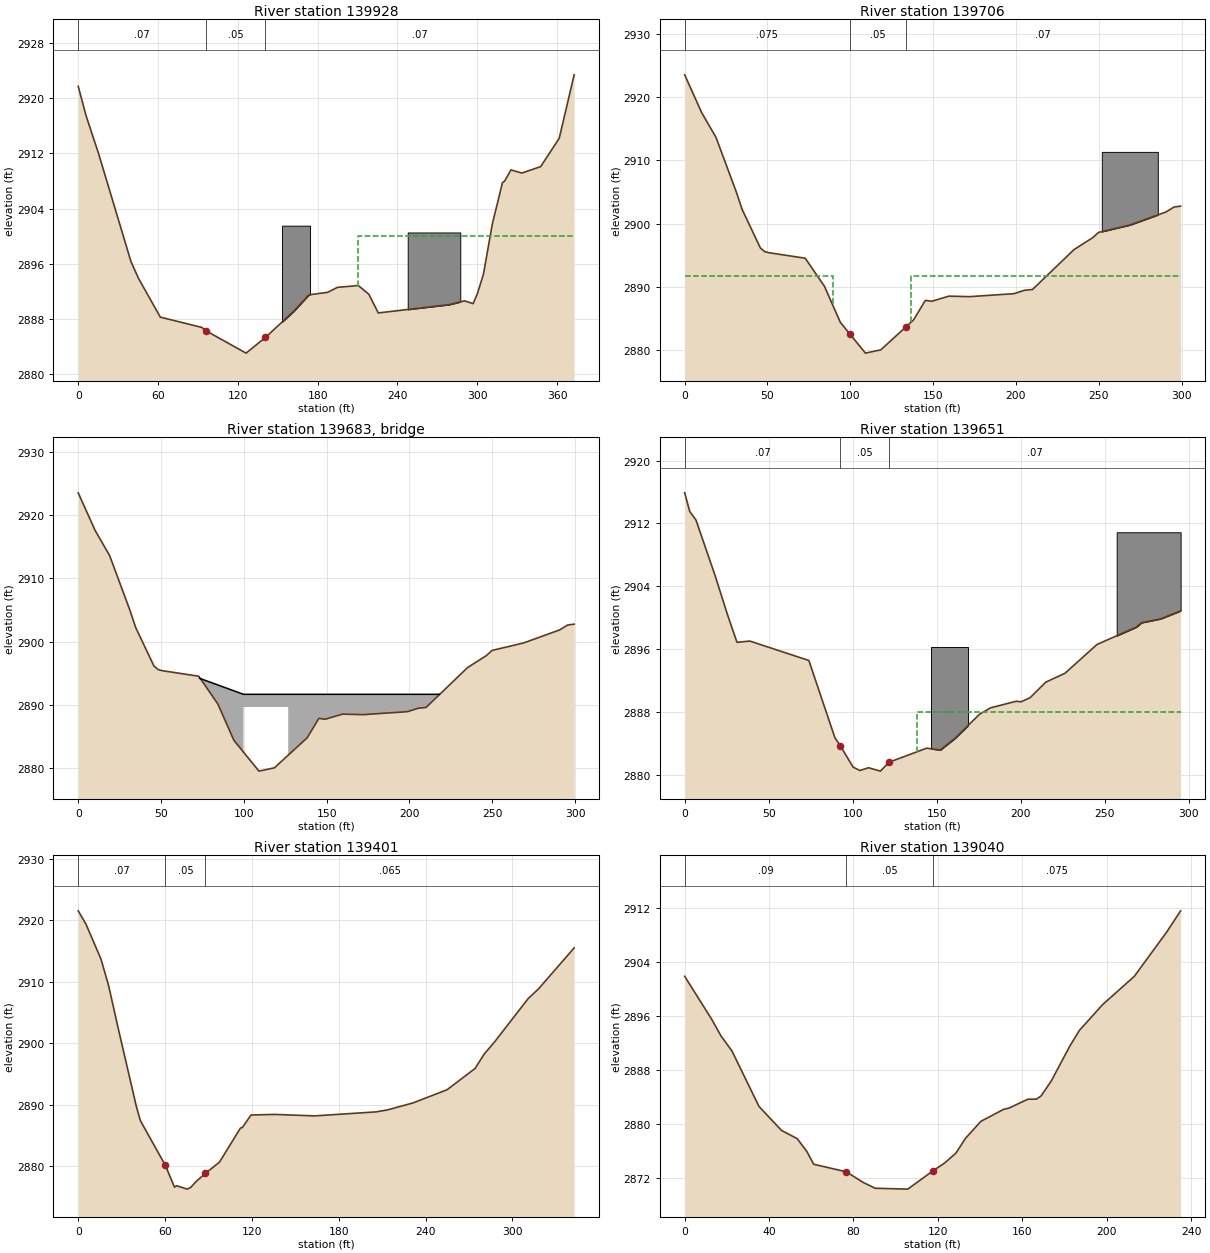
Type RM Length L Ch R = 1 ,139928  ,227.13,221.17,239.65
BEGIN DESCRIPTION:
139849.8
END DESCRIPTION:
XS GIS Cut Line= 5
  947132.3830228  806972.0258437  947184.0332231  807000.8881366
  947240.2389565  807067.7289095  947297.9645664  807131.5309534
  947431.6461123  807174.0649666
#Sta/Elev= 30
       0 2921.74    5.94 2917.44   15.32 2911.96   39.71 2896.28    45.5 2893.81
   61.73 2888.25   92.89 2886.76   96.33 2886.24  126.19 2883.03  140.71  2885.3
  162.08 2889.11   173.4 2891.48  187.53 2891.85  194.91 2892.57  210.62 2892.83
  218.51 2891.56  225.56 2888.86   278.9 2890.06  290.43 2890.61  296.88 2890.21
  300.04 2891.64   304.6 2894.45  311.34 2901.78  318.93 2907.76   320.5 2907.96
  325.31  2909.6  333.55 2909.15  347.67 2910.08  361.61 2914.19  372.82 2923.39
#Mann= 3 , 0 , 0
       0     .07       0   96.33     .05       0  140.71     .07       0
#XS Ineff= 2 , 0
       0                  209.97       0    2900
Permanent Ineff=
       F       F
#Block Obstruct= 2 ,-1
  153.22  174.292901.518  247.69  287.222900.529
Bank Sta=96.33,140.71
Exp/Cntr=0.5,0.3

Type RM Length L Ch R = 1 ,139706  ,48.11,55.83,46.99
BEGIN DESCRIPTION:
139628.6
END DESCRIPTION:
XS GIS Cut Line= 6
  947015.4129504  807119.3780856  947032.1233997  807161.9120988
  947083.7725758  807218.1188563  947139.9793333  807284.9596292
  947167.3227738    807325.97479  947203.7813772  807344.2040917
#Sta/Elev= 30
       0 2923.52   10.25 2917.56   18.95 2913.62   31.16 2905.02   34.73 2902.24
    45.7 2896.18   48.34  2895.6   50.55 2895.44   72.77 2894.56   84.37 2890.14
   93.99 2884.43   99.92 2882.53  109.14 2879.57  118.43 2880.09  133.61 2883.72
   138.2 2884.82   145.3  2887.9  149.11 2887.76  159.56 2888.57  172.12 2888.49
  198.85 2888.96  205.21  2889.5     210 2889.62  235.05 2895.92  246.34  2897.8
  249.85 2898.63  268.76  2899.8  290.57 2901.86  295.44 2902.64  299.42 2902.78
#Mann= 3 , 0 , 0
       0    .075       0   99.92     .05       0  133.61     .07       0
#XS Ineff= 2 , 0
       0   89.77  2891.7  136.77       0  2891.7
Permanent Ineff=
       F       F
#Block Obstruct= 2 ,-1
                          251.84  285.632911.354
Bank Sta=99.92,133.61
Exp/Cntr=0.5,0.3

Type RM Length L Ch R = 3 ,139683  ,,,
Node Photo=H:\PROJ\06-0741\CE\GIS\DATA\FRENCH_BROAD_RIVER\SHAPEFILES\survey_data\photos\FBSTR_1779A.JPG
BEGIN DESCRIPTION:
139605  FBSTR_1779A
END DESCRIPTION:
Bridge Culvert--1,0,-1,-1, 0
Deck Dist Width WeirC Skew NumUp NumDn MinLoCord MaxHiCord MaxSubmerge Is_Ogee
14,12,2.6,0, 7, 7, , , 0.95, 0, 1,1,,
   73.26   99.77   99.77  112.77  126.77  126.77  218.08
 2894.23  2891.7  2891.7  2891.7  2891.7  2891.7  2891.7
                  2889.7  2889.7  2889.7
   73.91   96.43   96.43  109.43  123.43  123.43  213.96
 2894.56  2891.7  2891.7  2891.7  2891.7  2891.7 2891.63
                  2889.7  2889.7  2889.7
BR Coef=-1 , 0 , 0 ,, 0 ,,,0.8,0,,0,
WSPro=,,,, 1 ,,,, 0 ,,,, 0 ,,,,-1 ,-1 ,-1 , 0 , 0 , 0 , 0 , 0
BC Design=,, 0 ,, 0 ,,,,,,

Type RM Length L Ch R = 1 ,139651  ,249.43,249.46,292.6
BEGIN DESCRIPTION:
139572.8
END DESCRIPTION:
XS GIS Cut Line= 6
  946983.5119285   807149.759231  947007.8176641  807204.4471361
  947032.1233997  807243.9434444  947054.9092587  807275.8444663
  947106.5584348  807324.4559375   947180.994494  807350.2805256
#Sta/Elev= 30
       0 2915.89    3.04 2913.51    6.75 2912.42    18.1 2905.37   25.57 2900.34
   31.14 2896.88   38.77 2897.04   73.91 2894.57   89.41 2884.74   92.66 2883.71
  100.23 2881.01  104.24 2880.58  109.43 2880.93  116.48  2880.5  121.58 2881.63
  144.05 2883.42  152.08 2883.18  160.92 2884.68  175.62 2887.76  182.04 2888.55
   197.4 2889.39  200.08 2889.31  205.59 2889.84  214.88 2891.81  226.37 2892.95
  245.34  2896.6  268.86 2898.82  271.88 2899.37   283.1 2899.85  295.14 2900.88
#Mann= 3 , 0 , 0
       0     .07       0   92.66     .05       0  121.58     .07       0
#XS Ineff= 2 , 0
       0   81.43    2888  138.43       0    2888
Permanent Ineff=
       F       F
#Block Obstruct= 2 ,-1
   146.6  168.582896.286   257.1  295.142910.877
Bank Sta=92.66,121.58
Exp/Cntr=0.5,0.3

Type RM Length L Ch R = 1 ,139401  ,341.85,361.77,291.2
BEGIN DESCRIPTION:
139323.3
END DESCRIPTION:
XS GIS Cut Line= 6
  946769.3189136  807292.5549156  946813.3728034  807353.3192546
  946834.6408341  807391.2956863  946887.8088626  807483.9610473
  946927.3051709  807541.6866572  946931.8627524   807588.779276
#Sta/Elev= 30
       0 2921.54    5.34 2919.39   15.69 2913.71   20.98  2909.4   27.73 2902.32
   40.11 2889.76   42.95 2887.39   60.17 2880.13   66.54 2876.55   67.96  2876.8
   75.27 2876.24   77.72 2876.51   81.51  2877.5   87.85 2878.79   97.61 2880.64
  112.14 2886.19  113.48 2886.28  119.41 2888.31  135.84  2888.4  163.37 2888.16
  205.65 2888.81  213.45 2889.12  231.33 2890.27  254.81 2892.41  274.21 2895.88
  280.57 2898.24  287.55 2900.16  311.05  2907.3     318 2908.82  342.67 2915.51
#Mann= 3 , 0 , 0
       0     .07       0   60.17     .05       0   87.85    .065       0
Bank Sta=60.17,87.85
Exp/Cntr=0.3,0.1

Type RM Length L Ch R = 1 ,139040  ,170.36,200.31,216.35
BEGIN DESCRIPTION:
138961.5
END DESCRIPTION:
XS GIS Cut Line= 4
  946553.6070463  807537.1290758  946591.5845022  807608.5274302
  946649.3101122  807648.0237385  946702.4791648  807713.3446348
#Sta/Elev= 30
       0 2901.87   12.69 2895.56   17.17 2893.06   22.41  2890.8   35.22 2882.58
   45.83 2879.04   53.34  2877.8   57.84 2875.93   61.16 2874.01   76.56 2872.89
   84.57 2871.32   90.29 2870.45  105.74 2870.32  117.532873.002  123.08 2874.16
   128.6 2875.68   133.1 2877.86  140.43 2880.38  151.17 2882.15  153.74 2882.34
  162.63 2883.65  166.69 2883.66  168.96 2884.15  173.86 2886.42  182.39 2891.45
  187.06 2893.85  197.98 2897.65  213.08 2901.86  228.39 2908.41  235.04 2911.58
#Mann= 3 , 0 , 0
       0     .09       0   76.56     .05       0  117.53    .075       0
Bank Sta=76.56,117.53
Exp/Cntr=0.3,0.1

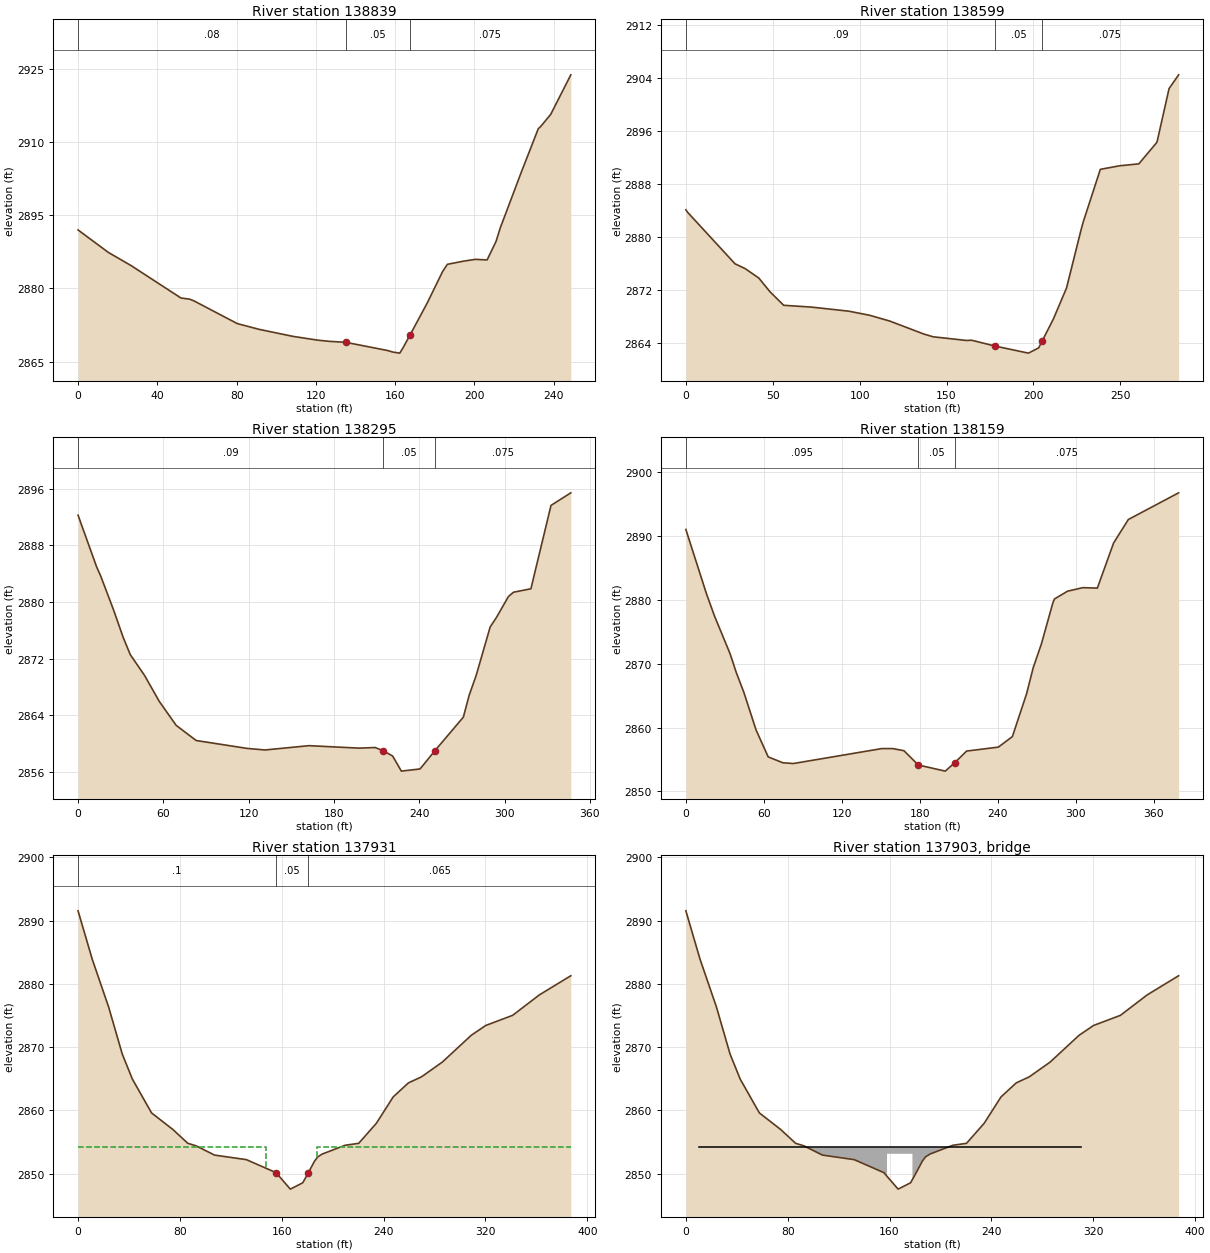
Type RM Length L Ch R = 1 ,138839  ,174.24,239.75,276.26
BEGIN DESCRIPTION:
138761.2
END DESCRIPTION:
XS GIS Cut Line= 5
  946433.5982449  807596.3745624  946429.0416876  807658.6577538
  946442.7134078   807727.016355  946474.6144298  807774.1089738
  946511.0730332  807821.2005684
#Sta/Elev= 30
       0    2892    15.3 2887.39   26.77 2884.69   51.89 2878.05   56.39  2877.8
   58.54 2877.44   80.32  2872.8    91.4 2871.61   108.5 2870.17  120.94  2869.4
  126.67 2869.16  135.01 2868.96  156.12 2867.28  158.89 2866.95   162.3 2866.74
  163.87 2867.78  167.44 2870.42  176.12 2876.99  183.91 2883.47  186.32 2884.95
  194.56 2885.61  200.49 2885.97  206.36 2885.85  210.87 2889.64  212.98 2892.39
  223.35 2903.56  232.19 2912.77  233.28 2913.16  238.45  2915.7   248.6 2923.81
#Mann= 3 , 0 , 0
       0     .08       0  135.01     .05       0  167.44    .075       0
Bank Sta=135.01,167.44
Exp/Cntr=0.3,0.1

Type RM Length L Ch R = 1 ,138599  ,189.36,304.23,338.81
BEGIN DESCRIPTION:
138521.5
END DESCRIPTION:
XS GIS Cut Line= 5
  946293.8412893  807614.6038641    946257.38371  807666.2530402
  946236.1156793  807702.7106194  946227.0015405  807831.8345838
  946223.9628115  807880.4450308
#Sta/Elev= 30
       0 2884.09      .9 2883.74   28.27 2875.94   34.11 2875.21   41.96 2873.79
   48.43 2871.71   56.28 2869.67   72.24  2869.4   93.79 2868.78  105.83 2868.16
  117.35 2867.29  136.87 2865.34  142.22 2864.92  161.52 2864.36   164.4  2864.4
  178.06 2863.51  197.13 2862.45  203.03 2863.24  205.012864.259   211.5  2867.6
  219.06 2872.27  227.35 2880.97  228.62  2882.2  238.52 2890.19  249.57 2890.73
  260.67 2891.02  270.63 2894.13  271.17 2894.34  278.06 2902.37  283.58 2904.46
#Mann= 3 , 0 , 0
       0     .09       0  178.06     .05       0  205.01    .075       0
Bank Sta=178.06,205.01
Exp/Cntr=0.3,0.1

Type RM Length L Ch R = 1 ,138295  ,169.68,136.13,133.91
BEGIN DESCRIPTION:
138217.2
END DESCRIPTION:
XS GIS Cut Line= 6
  946119.1456069  807556.8782541  946075.0917171  807613.0839875
  946029.5189749  807649.5425909  945958.1216447  807695.1153331
  945923.1818937  807730.0550841  945874.5714467  807796.8948328
#Sta/Elev= 30
       0 2892.28   13.06 2884.97   15.83 2883.73   24.93 2878.91   31.68 2875.03
   36.73 2872.56    46.8 2869.61   57.12 2865.95   69.02 2862.56   83.07 2860.42
  118.97  2859.3  131.42 2859.08   162.4 2859.69  197.74 2859.34  208.91 2859.43
  214.48 2858.98  221.22 2858.23  227.37 2856.09  240.53  2856.4  251.052859.001
  270.95 2863.72  275.01 2866.79  279.96 2869.61  289.83 2876.48  294.18  2877.8
  302.68 2880.78  306.29 2881.39  318.46 2881.87   332.6 2893.66  346.54 2895.44
#Mann= 3 , 0 , 0
       0     .09       0  214.48     .05       0  251.05    .075       0
Bank Sta=214.48,251.05
Exp/Cntr=0.3,0.1

Type RM Length L Ch R = 1 ,138159  ,172.33,228.27,229.11
BEGIN DESCRIPTION:
138081.1
END DESCRIPTION:
XS GIS Cut Line= 5
   945994.579224  807442.9458865  945945.9687769  807503.7092014
  945883.6855854  807584.2216946  945807.7306737  807660.1766063
  945757.6003501  807737.6503704
#Sta/Elev= 30
       0 2891.01   16.01 2880.85    22.1 2877.43   34.09 2871.53   38.82  2868.6
   44.59 2865.54   54.03 2859.62   63.39  2855.4   74.66 2854.48   82.77 2854.36
  150.79  2856.7  159.31  2856.7  167.87 2856.37  178.91 2854.13  199.69 2853.17
  206.91 2854.48  216.11 2856.31  240.54 2856.93  251.33 2858.58  262.23 2865.26
  267.33 2869.34  273.68  2873.1  282.44 2879.48  283.74 2880.13  293.83 2881.35
  305.61  2881.9  316.74 2881.83  329.23 2888.89  340.58 2892.57   379.3 2896.75
#Mann= 3 , 0 , 0
       0    .095       0  178.91     .05       0  206.91    .075       0
Bank Sta=178.91,206.91
Exp/Cntr=0.5,0.3

Type RM Length L Ch R = 1 ,137931  ,68.5,68.77,34.9
BEGIN DESCRIPTION:
137852.8
END DESCRIPTION:
XS GIS Cut Line= 6
   945879.128004  807338.1276578  945777.3485042   807409.524988
   945680.126586  807449.0223205  945652.7831455  807476.3657609
  945626.9585574  807537.1290758  945619.3622469   807588.779276
#Sta/Elev= 30
       0 2891.54   11.13  2883.9   24.05 2876.32   34.74 2868.89   42.69 2864.94
   57.73  2859.6   74.52 2856.97   86.16  2854.8   92.88 2854.38  107.22 2852.93
  132.25 2852.21  155.49 2850.16  166.74 2847.55   176.5 2848.55  180.942850.146
  185.66 2851.94  188.21 2852.63  191.64 2853.08  209.72 2854.48  220.48 2854.79
  234.38 2857.97  247.57 2862.13   259.5 2864.34  269.86 2865.31  286.19 2867.64
  308.89 2871.87  320.27 2873.42  341.36 2875.02  362.37 2878.25  387.08 2881.28
#Mann= 3 , 0 , 0
       0      .1       0  155.49     .05       0  180.94    .065       0
#XS Ineff= 2 , 0
       0     148 2854.13     188       0 2854.13
Permanent Ineff=
       F       F
Bank Sta=155.49,180.94
Exp/Cntr=0.5,0.3

Type RM Length L Ch R = 3 ,137903  ,,,
Node Photo=H:\PROJ\06-0741\CE\GIS\DATA\FRENCH_BROAD_RIVER\SHAPEFILES\survey_data\photos\FBSTR_1263.JPG
BEGIN DESCRIPTION:
137820  FBSTR_1263
END DESCRIPTION:
Bridge Culvert--1,0,-1,-1, 0
Deck Dist Width WeirC Skew NumUp NumDn MinLoCord MaxHiCord MaxSubmerge Is_Ogee
28,9,2.6,0, 7, 7, , , 0.95, 0, 1,1,,
      10     158     158     168     178     178     310
 2854.13 2854.13 2854.13 2854.13 2854.13 2854.13 2854.13
                 2853.13 2853.13 2853.13
     -10     141     141     151     161     161     290
 2854.13 2854.13 2854.13 2854.13 2854.13 2854.13 2854.13
                 2853.13 2853.13 2853.13
BR Coef=-1 , 0 , 0 ,, 0 ,,,0.8,0,,0,
WSPro=,,,, 1 ,,,, 0 ,,,, 0 ,,,,-1 ,-1 ,-1 , 0 , 0 , 0 , 0 , 0
BC Design=,, 0 ,, 0 ,,,,,,

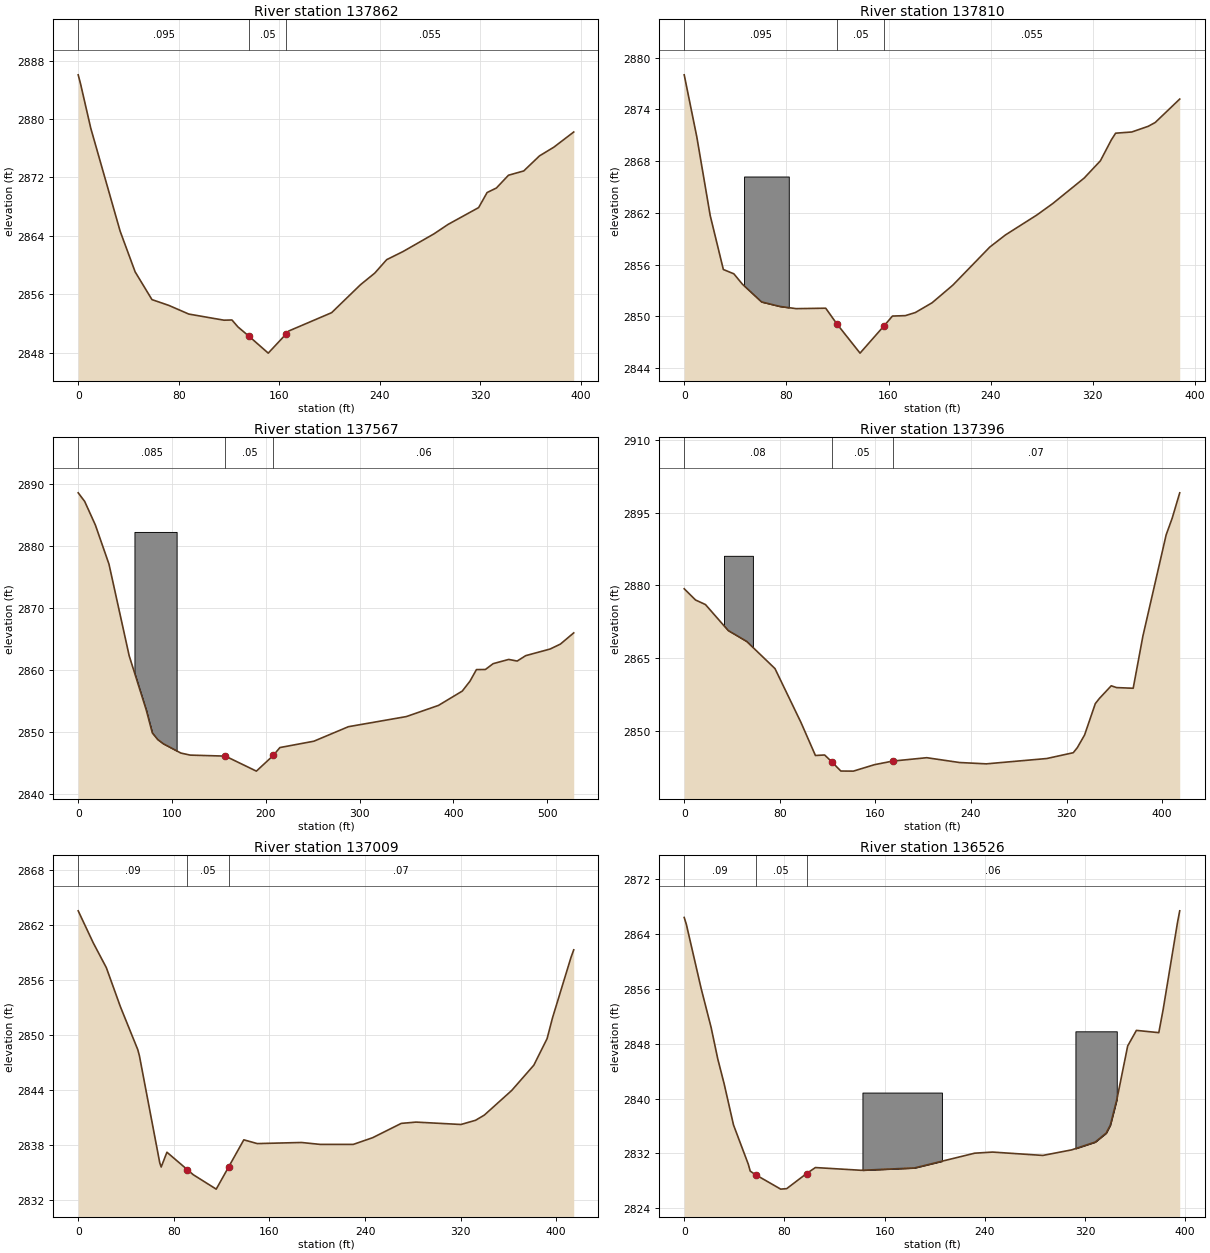
Type RM Length L Ch R = 1 ,137862  ,66.65,51.6,19.38
BEGIN DESCRIPTION:
137784.1
END DESCRIPTION:
XS GIS Cut Line= 6
  945836.5939908  807283.4407768  945791.0202245  807321.4172085
  945701.3935925  807363.9522458  945642.1491301  807415.6014219
   945622.400976  807452.0600253   945590.499954   807562.954688
#Sta/Elev= 30
       0 2886.05    1.88 2884.82      10 2878.75   33.42 2864.63   45.35 2859.07
   58.74 2855.27   72.27 2854.47   88.04 2853.29   116.1 2852.45  122.44 2852.48
  127.21 2851.53   136.1 2850.24  151.34 2847.94  165.41 2850.53  167.68 2850.97
  201.82 2853.48  224.81 2857.31  236.12 2858.89  245.66 2860.74  258.78 2861.86
  283.29 2864.27  294.58 2865.57  318.88 2867.87  325.62 2869.93  333.02 2870.55
  342.64  2872.3  354.82 2872.89  367.34 2874.95  378.76 2876.14   394.6 2878.22
#Mann= 3 , 0 , 0
       0    .095       0   136.1     .05       0  165.41    .055       0
#XS Ineff= 2 , 0
       0     126 2850.24     176       0 2851.21
Permanent Ineff=
       F       F
Bank Sta=136.1,165.41
Exp/Cntr=0.5,0.3

Type RM Length L Ch R = 1 ,137810  ,250.38,243.54,205.72
BEGIN DESCRIPTION:
137732.5
END DESCRIPTION:
XS GIS Cut Line= 6
  945795.5778059  807237.8670105  945745.4474823   807271.287909
   945680.126586  807316.8606512   945648.225564  807350.2805256
  945625.4386808  807388.2579814  945578.3470862  807538.6489524
#Sta/Elev= 30
       0 2878.01    9.86 2870.82   20.36 2861.69   30.65 2855.43   38.87 2854.93
   45.54 2853.73   60.53 2851.67    74.9 2851.15   87.57 2850.89   110.8 2850.94
  119.54 2849.12  137.68 2845.73  156.382848.878  163.06 2850.03  173.18 2850.08
  181.01 2850.44  194.09 2851.57  210.36 2853.62  239.24 2858.03  251.54 2859.44
   276.1 2861.75  288.47 2863.07   313.2 2866.04  325.87 2868.04  334.42 2870.46
  337.78 2871.24  350.45 2871.38  363.31 2872.04  368.78 2872.48  387.98  2875.2
#Mann= 3 , 0 , 0
       0    .095       0  119.54     .05       0  156.38    .055       0
#Block Obstruct= 1 ,-1
   46.87   81.882866.216
Bank Sta=119.54,156.38
Exp/Cntr=0.3,0.1

Type RM Length L Ch R = 1 ,137567  ,128.04,171.29,271.05
BEGIN DESCRIPTION:
137488.9
END DESCRIPTION:
XS GIS Cut Line= 6
  945661.8972843  807025.1938722  945525.1790577  807128.4922244
  945476.5675865  807186.2178344  945453.7807033  807309.2653649
  945452.2618509  807385.2202766  945470.4911526  807462.6940407
#Sta/Elev= 30
       0 2888.54    6.91 2887.16   18.35 2883.34   32.82 2877.05   54.37 2862.28
   72.54 2853.55   79.02 2849.85    84.7 2848.79   90.66 2848.11   109.5  2846.6
   119.5 2846.27  156.91 2846.11  189.98 2843.69  207.96 2846.21  215.05 2847.49
  251.25 2848.51  288.09 2850.85  349.81 2852.48  384.09 2854.28  409.48 2856.59
  417.71 2858.19  424.57 2860.05  434.11 2860.07   442.4 2861.01  458.96 2861.69
  468.02 2861.43  477.12  2862.3  503.17 2863.37  514.07 2864.16  528.29 2865.97
#Mann= 3 , 0 , 0
       0    .085       0  156.91     .05       0  207.96     .06       0
#Block Obstruct= 1 ,-1
   59.98  104.932882.238
Bank Sta=156.91,207.96
Exp/Cntr=0.3,0.1

Type RM Length L Ch R = 1 ,137396  ,388.82,386.39,251.04
BEGIN DESCRIPTION:
137317.6
END DESCRIPTION:
XS GIS Cut Line= 6
  945592.0188065   806918.856791  945543.4073352   806953.796542
  945500.8733221  806978.1012534  945426.4372628  806993.2928503
  945373.2692343  807026.7127246  945265.4133007  807154.3168124
#Sta/Elev= 30
       0 2879.31    9.47    2877   17.81 2876.05   36.76 2870.71   52.38 2868.43
   75.97 2862.84   97.71 2851.73  109.82 2844.91  117.55 2845.01  123.44 2843.62
  131.07  2841.7  141.57 2841.68  159.23 2843.01  174.42 2843.75     203 2844.45
  230.31 2843.46  252.81 2843.18  303.41 2844.28  325.61 2845.48  328.99 2846.52
  335.06 2849.13  344.06 2855.61  347.47 2856.68  357.39 2859.29  361.83 2858.92
  375.76 2858.78  383.87 2869.53  403.34 2890.44  408.34 2893.84  414.71 2899.11
#Mann= 3 , 0 , 0
       0     .08       0  123.44     .05       0  174.42     .07       0
#Block Obstruct= 1 ,-1
   33.29   57.492886.114
Bank Sta=123.44,174.42
Exp/Cntr=0.3,0.1

Type RM Length L Ch R = 1 ,137009  ,543.13,482.99,294.72
BEGIN DESCRIPTION:
136931.3
END DESCRIPTION:
XS GIS Cut Line= 6
   945269.969858  806697.0684898  945177.3055212  806782.1385644
  945160.5950719  806809.4820049  945128.6940499  806909.7426522
  945078.5637263   807011.522152  945063.3731536  807046.4608788
#Sta/Elev= 30
       0 2863.53   12.57 2860.05   23.55 2857.34   35.34 2853.08   49.86 2848.41
   51.25 2847.73   68.28 2836.07   69.45 2835.63   74.25 2837.24   91.282835.346
   96.28 2834.79   115.5 2833.22  125.82 2835.62  138.59 2838.59  149.83 2838.18
  186.87  2838.3  202.54 2838.09  230.15 2838.09  246.36 2838.82  270.33 2840.38
  282.71 2840.52  320.29 2840.26  332.53 2840.72   339.8 2841.28   362.7 2843.96
  381.26 2846.72  392.35 2849.61  396.87 2851.87  412.33 2858.45  414.63 2859.28
#Mann= 3 , 0 , 0
       0     .09       0   91.28     .05       0  125.82     .07       0
Bank Sta=91.28,125.82
Exp/Cntr=0.3,0.1

Type RM Length L Ch R = 1 ,136526  ,281.71,419.25,410.42
BEGIN DESCRIPTION:
136448.3
END DESCRIPTION:
XS GIS Cut Line= 5
  944700.3090444  806654.5344767  944738.2865003  806715.2977915
  944768.6686698  806782.1385644  944797.5309627  806920.3756434
  944799.0498151  807029.7514537
#Sta/Elev= 30
       0 2866.45    1.71 2865.45   13.45 2856.14   21.52 2850.37   26.78 2845.81
   31.92 2842.14   39.37 2836.15   51.21  2830.4   52.72 2829.41   56.94 2828.89
   77.04 2826.78   81.84 2826.85   97.67 2829.05  104.77 2829.93  141.36 2829.53
  183.84 2829.87     232 2832.03  246.28 2832.19  286.33  2831.7  309.33 2832.51
  328.16 2833.65  336.93 2834.96  340.25 2836.13   345.6 2839.97  354.12 2847.69
  361.08 2849.96  378.97 2849.63  382.37 2852.94  393.91 2865.73  395.68 2867.42
#Mann= 3 , 0 , 0
       0     .09       0   56.94     .05       0   97.67     .06       0
#Block Obstruct= 2 ,-1
  142.32  205.79 2840.88  312.39   345.42849.825
Bank Sta=56.94,97.67
Exp/Cntr=0.3,0.1

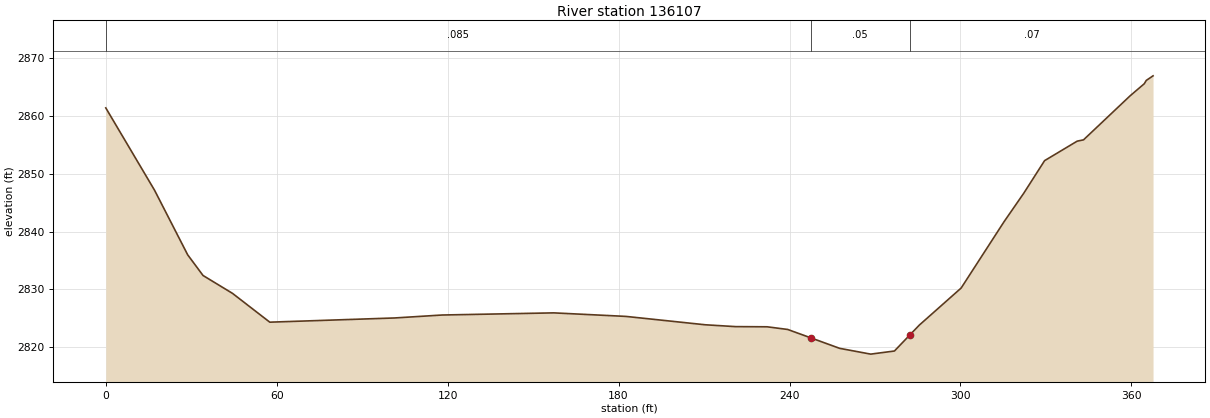
Type RM Length L Ch R = 1 ,136107  ,358.72,418.14,416.49
BEGIN DESCRIPTION:
136029.0
END DESCRIPTION:
XS GIS Cut Line= 5
  944460.2914415  806675.8014832  944451.1773027  806748.7176659
  944417.7564042  806902.1473659  944394.9705452  806952.2766654
  944394.9705452   807034.308011
#Sta/Elev= 30
       0 2861.42   17.13 2847.16   28.75 2835.99   34.14 2832.41   44.47 2829.32
   57.57 2824.33  101.43 2825.06  118.08 2825.57  157.25 2825.94  182.54 2825.33
  210.41 2823.88  221.05 2823.56  232.14 2823.53  239.36 2823.07   247.52821.613
  257.61  2819.8  268.51  2818.8  276.83 2819.34  282.18 2822.09  285.58 2823.83
  300.25 2830.24   315.3 2841.71  322.24 2846.66  329.54 2852.29  340.97 2855.66
  343.21 2855.89  359.56 2863.51  364.55 2865.61  365.22 2866.17  367.61 2866.97
#Mann= 3 , 0 , 0
       0    .085       0   247.5     .05       0  282.18     .07       0
Bank Sta=247.5,282.18
Exp/Cntr=0.3,0.1