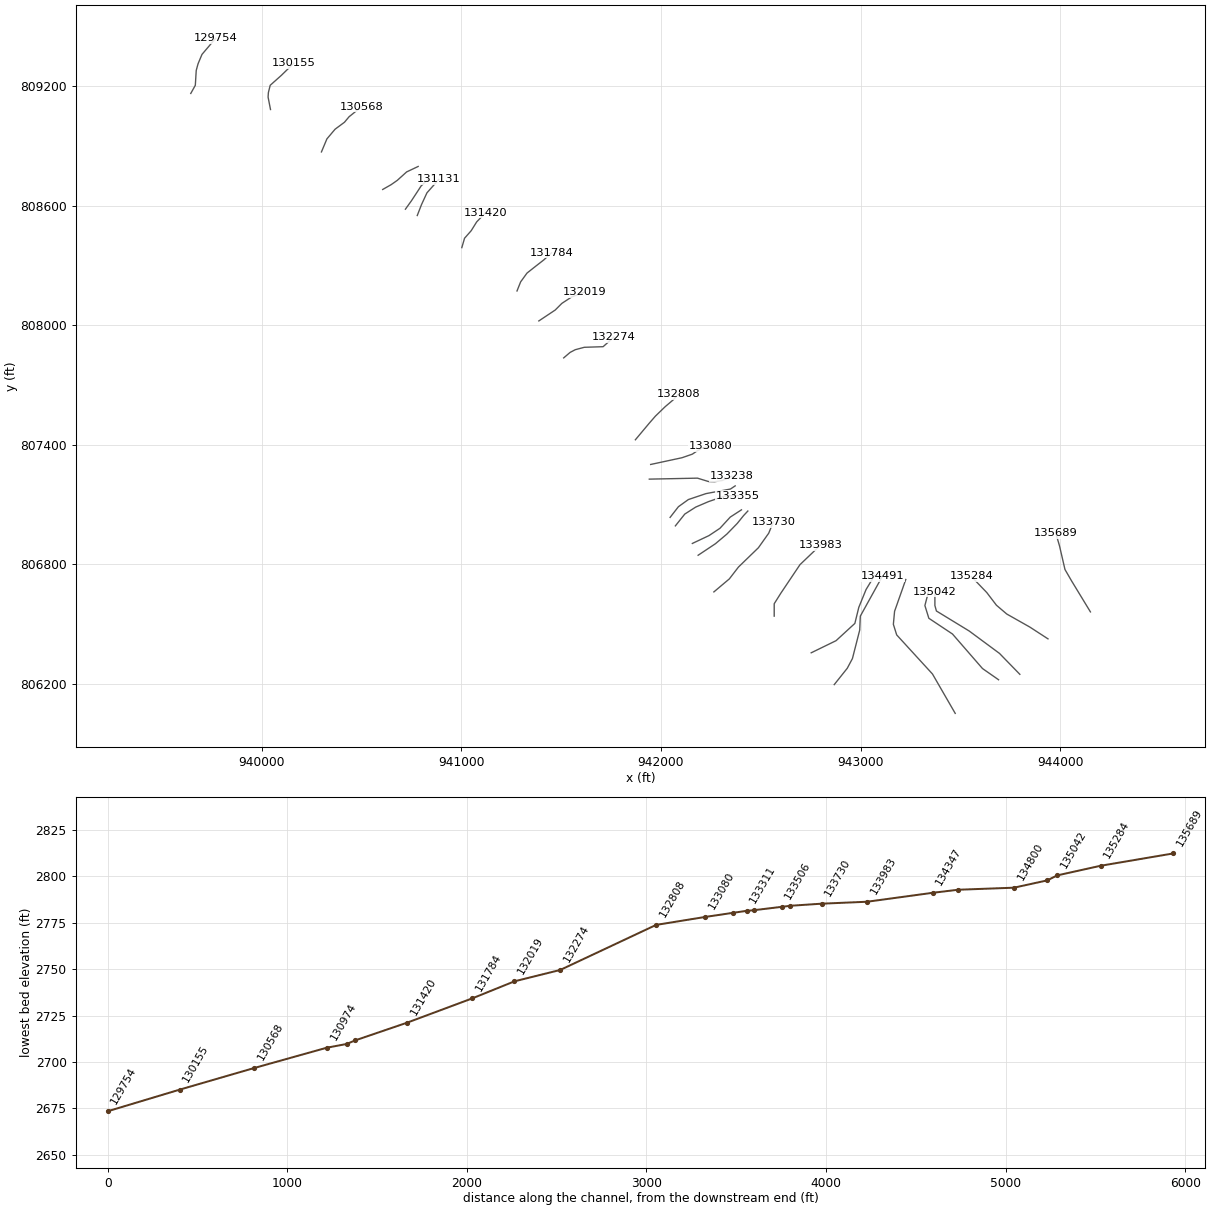
HEC-RAS study lds_big_laurel_crk.prj: lds_big_laurel_crk

--- lds_big_laurel_crk.g20 (geometry) --- (continued)

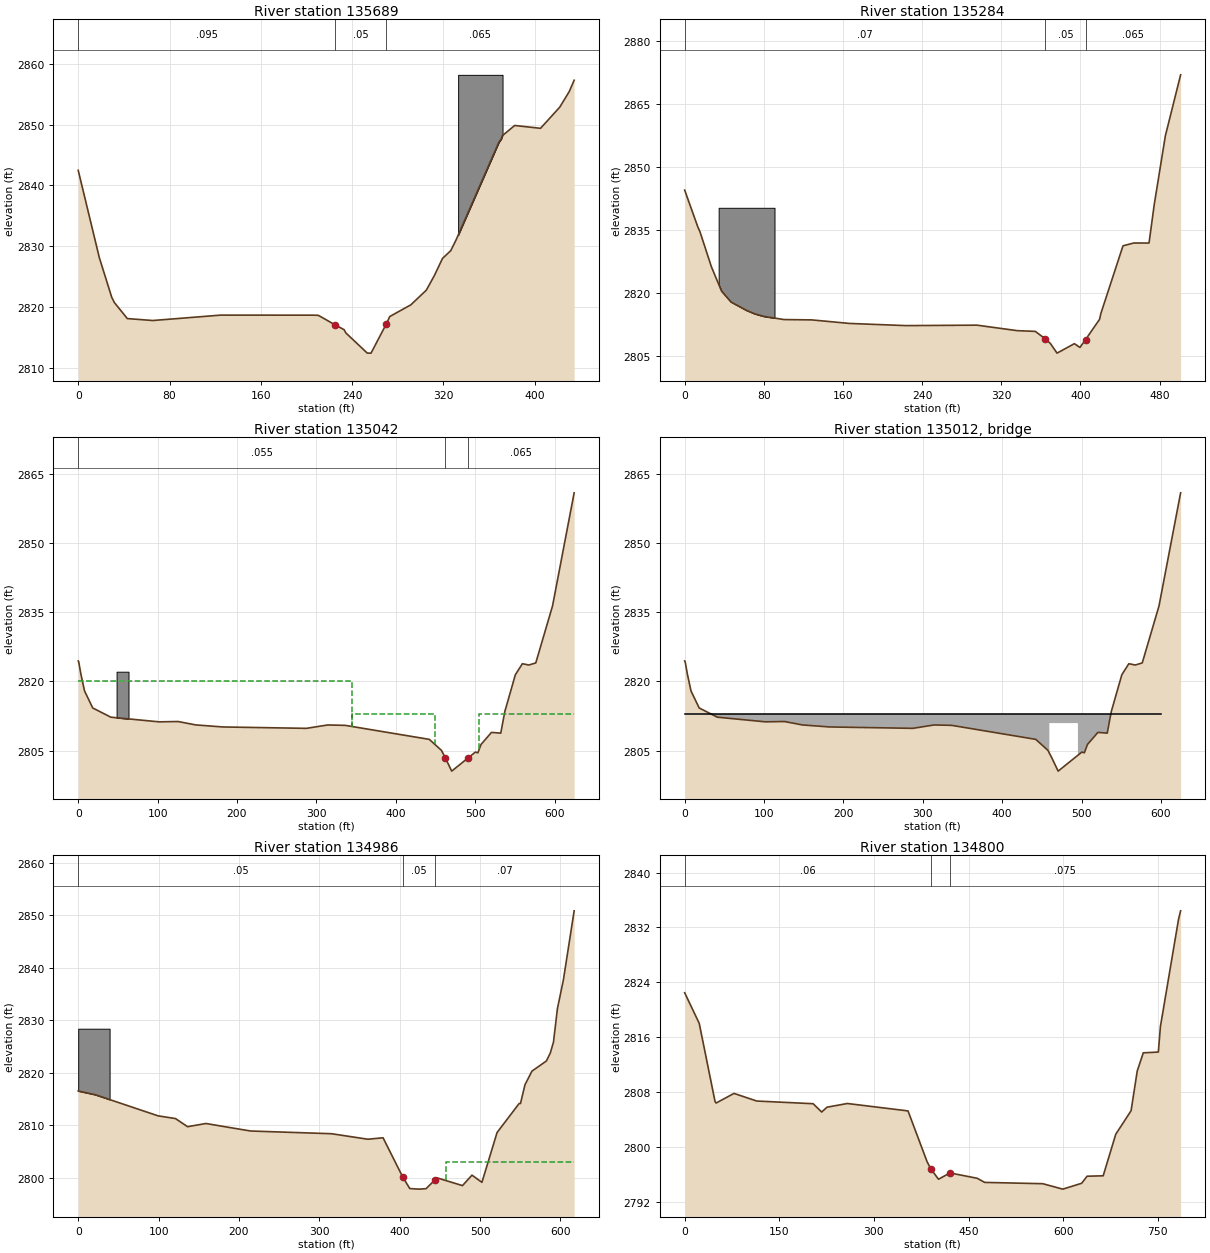
Type RM Length L Ch R = 1 ,135689  ,302.56,405.14,465.78
BEGIN DESCRIPTION:
135610.9
END DESCRIPTION:
XS GIS Cut Line= 5
  944151.9142132  806561.8691157   944057.731024  806716.8166439
  944024.3101255  806774.5422539   943996.966685   806893.032203
  943978.7373833  806955.3153944
#Sta/Elev= 30
       0 2842.48   18.49  2828.1   29.43 2821.54   31.69  2820.7   43.04 2818.06
   65.33 2817.74   124.9 2818.63  206.55 2818.62  210.44 2818.59  225.362816.994
  232.98 2816.23  234.49  2815.7  253.31 2812.37  256.56 2812.37  269.792817.119
  272.98  2818.4  291.43 2820.32  305.01 2822.74  312.08 2825.15  319.16 2827.96
  326.42 2829.25  331.33 2831.11  368.64 2847.12  370.66 2847.64  371.59 2848.17
  382.45 2849.86  405.06 2849.39   421.9 2852.87  430.29 2855.46  434.53 2857.31
#Mann= 3 , 0 , 0
       0    .095       0  225.36     .05       0  269.79    .065       0
#Block Obstruct= 1 ,-1
  332.88  371.79  2858.2
Bank Sta=225.36,269.79
Exp/Cntr=0.3,0.1

Type RM Length L Ch R = 1 ,135284  ,204.31,241.63,237.93
BEGIN DESCRIPTION:
135205.7
END DESCRIPTION:
XS GIS Cut Line= 6
   943939.241075  806426.6697416  943848.0955906   806485.914204
  943732.6443707  806551.2351003  943680.9941704  806595.2889901
  943632.3837233   806659.091034  943554.9099592  806739.6035271
#Sta/Elev= 30
       0 2844.47   13.22 2835.77   15.56 2834.51   27.01 2826.25   37.28 2820.45
   46.78 2817.88   62.26  2815.9      71 2815.04   80.18 2814.44  100.34  2813.7
  128.36 2813.62  166.57 2812.78  223.48 2812.26  295.33 2812.37  336.12 2811.06
  354.36 2810.89  364.41 2809.11  369.64    2808  376.32 2805.72  393.84 2807.97
  399.47 2807.07  405.172808.951   419.3 2813.76  420.58 2815.13  442.96 2831.23
  453.85  2831.9  469.26 2831.89  474.54 2841.05  485.79  2857.4  501.19 2871.88
#Mann= 3 , 0 , 0
       0     .07       0  364.41     .05       0  405.17    .065       0
#Block Obstruct= 1 ,-1
   34.32   90.782840.275
Bank Sta=364.41,405.17
Exp/Cntr=0.5,0.3

Type RM Length L Ch R = 1 ,135042  ,111.16,56.59,47.92
BEGIN DESCRIPTION:
134964.1
END DESCRIPTION:
XS GIS Cut Line= 6
  943798.2469153  806248.7448335  943696.1857672  806353.7525347
  943544.2759438  806466.1660499  943380.2132526  806566.4266972
  943372.6179663  806593.7701376  943372.6179663   806662.129763
#Sta/Elev= 30
       0 2824.43     .58 2824.28    3.37  2821.6    7.96 2817.93   18.28 2814.23
   41.11 2812.23  101.86 2811.22  125.75 2811.29  148.16 2810.55  182.48 2810.11
  287.36 2809.81  314.05 2810.54  336.21 2810.46   442.2 2807.42  457.52 2805.04
  462.57 2803.36  470.42 2800.53  490.49 2803.31  500.29 2804.66  503.43 2804.51
  507.35 2806.31  520.55 2808.93  532.24 2808.77  537.34 2813.45  550.63 2821.44
  559.46 2823.83   567.6 2823.55  576.34    2824  597.45 2836.37  624.67  2860.9
#Mann= 3 , 0 , 0
       0    .055       0  462.57     .05       0  490.49    .065       0
#XS Ineff= 3 ,-1
       0     345    2820     345  449.31 2812.95  505.31  624.67 2812.95
Permanent Ineff=
       F       F       F
#Block Obstruct= 1 ,-1
   48.32   63.352822.103
Bank Sta=462.57,490.49
Exp/Cntr=0.5,0.3

Type RM Length L Ch R = 3 ,135012  ,,,
Node Photo=H:\PROJ\06-0741\CE\GIS\DATA\FRENCH_BROAD_RIVER\SHAPEFILES\survey_data\photos\FBSTR_1257.JPG
BEGIN DESCRIPTION:
134933.1  FBSTR_1257
END DESCRIPTION:
Bridge Culvert--1,0,-1,-1, 0
Deck Dist Width WeirC Skew NumUp NumDn MinLoCord MaxHiCord MaxSubmerge Is_Ogee
22,12,3,0, 7, 7, , , 0.95, 0, 1,1,,
       0  459.31  459.31  477.31  495.31  495.31     600
 2812.95 2812.95 2812.95 2812.95 2812.95 2812.95 2812.95
                 2810.95 2810.95 2810.95
       0     406     406     424     442     442     600
 2812.95 2812.95 2812.95 2812.95 2812.95 2812.95 2812.95
                 2810.95 2810.95 2810.95
BR Coef=-1 , 0 , 0 ,, 0 ,,,0.8,0,,0,
WSPro=,,,, 1 ,,,, 0 ,,,, 0 ,,,,-1 ,-1 ,-1 , 0 , 0 , 0 , 0 , 0
BC Design=,, 0 ,, 0 ,,,,,,

Type RM Length L Ch R = 1 ,134986  ,222.72,185.18,137.84
BEGIN DESCRIPTION:
134907.5
END DESCRIPTION:
XS GIS Cut Line= 6
  943691.6281858  806221.5908655  943611.1156926   806277.797623
  943460.7257458  806450.9754772  943342.2357968  806529.9680937
  943322.4876427  806593.7701376  943342.2357968  806669.7250493
#Sta/Elev= 30
       0 2816.53   21.07 2815.82   99.34 2811.79  121.05 2811.27  136.11 2809.72
  158.86 2810.33  214.41  2808.9  315.28 2808.38  360.43 2807.33   379.3 2807.61
  403.722800.148  412.54 2797.93  423.64 2797.82  432.78  2797.9  443.93 2799.59
  446.92 2799.95  478.13 2798.49  489.92 2800.49   502.3 2799.11  521.16 2808.61
  548.67 2814.15  550.27 2814.13  555.87 2817.71  564.54 2820.31  582.54 2822.25
  587.38 2823.76  591.35 2825.85  596.24 2832.23  603.69 2837.71  617.06 2850.87
#Mann= 3 , 0 , 0
       0     .05       0  403.72     .05       0  443.93     .07       0
#XS Ineff= 2 , 0
       0     391    2804     457       0    2803
Permanent Ineff=
       F       F
#Block Obstruct= 1 ,-1
       0   39.042828.402
Bank Sta=403.72,443.93
Exp/Cntr=0.5,0.3

Type RM Length L Ch R = 1 ,134800  ,551.27,309.66,135.55
BEGIN DESCRIPTION:
134722.3
END DESCRIPTION:
XS GIS Cut Line= 6
   943474.397466   806052.971617  943360.4650985  806250.4541826
  943181.2118346  806446.4178957  943164.5013854  806499.5859242
  943170.5778193  806564.9068206  943226.7845768  806724.4129545
#Sta/Elev= 30
       0 2822.49   23.07 2818.03   48.17 2806.63   49.88 2806.43   78.17 2807.83
  114.22 2806.72  203.53 2806.33  217.17 2805.12  225.49 2805.82  257.82 2806.36
  353.94 2805.28  384.24 2797.87  390.39  2796.8  402.28 2795.33  420.31 2796.25
  463.59 2795.47  475.48 2794.87   567.5 2794.68  599.23 2793.89  629.11 2794.74
   637.7 2795.77  663.25 2795.83  683.16 2801.88  707.47 2805.31  717.21  2811.1
  726.79 2813.74  750.64 2813.85  753.95 2817.56  782.65 2833.19  785.96 2834.42
#Mann= 3 , 0 , 0
       0     .06       0  390.39     .05       0  420.31    .075       0
Bank Sta=390.39,420.31
Exp/Cntr=0.3,0.1

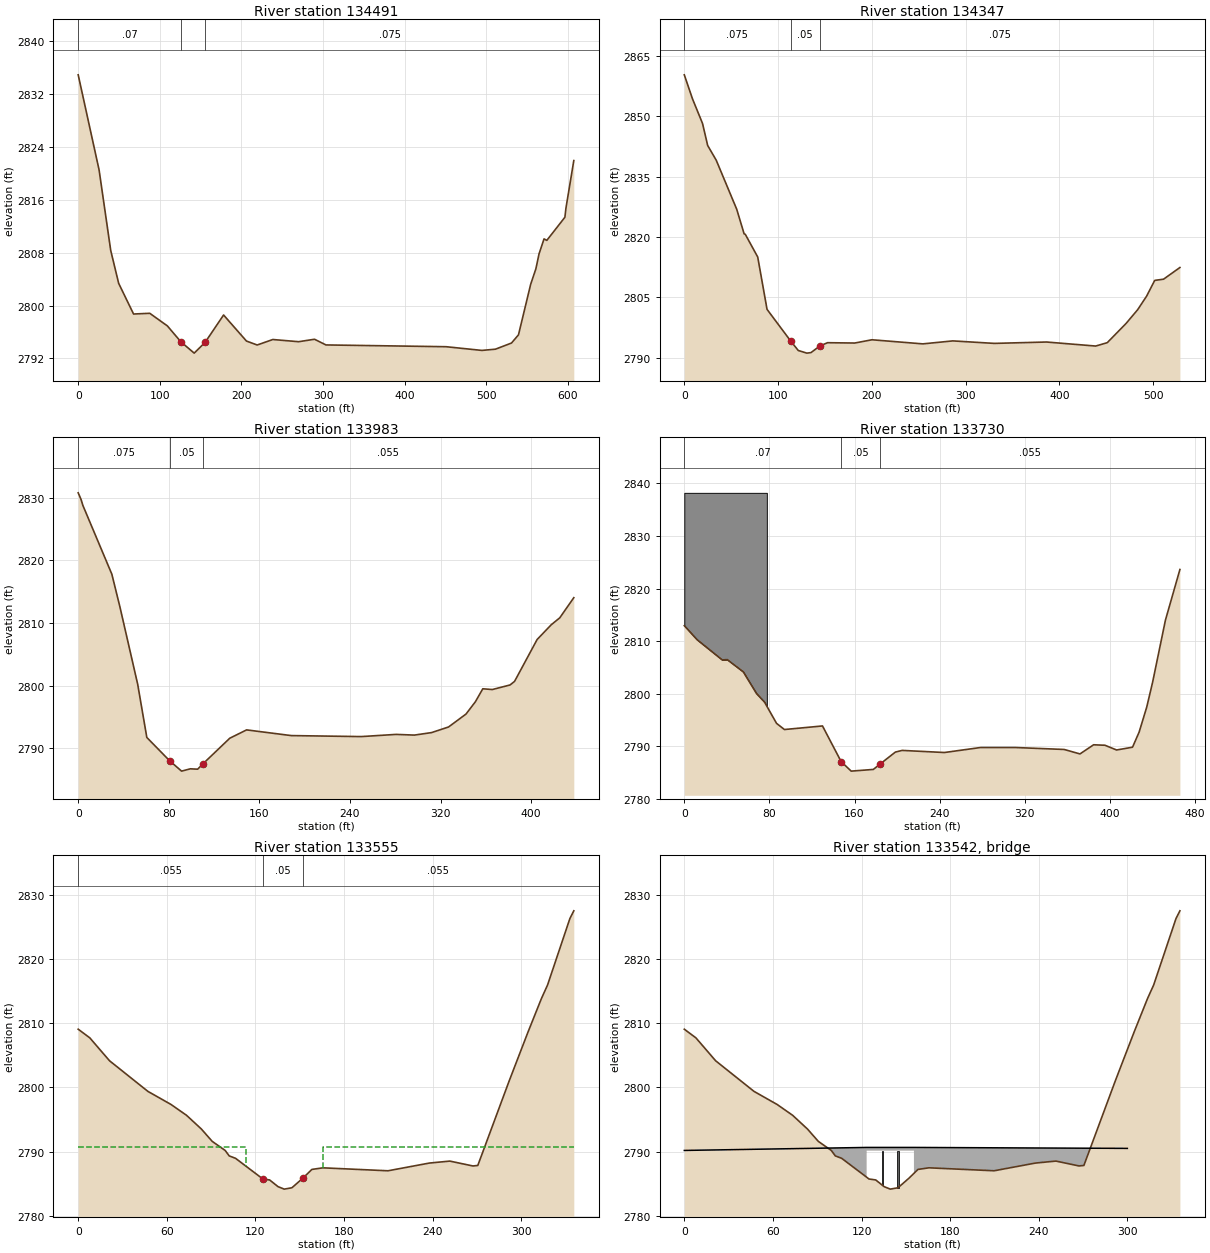
Type RM Length L Ch R = 1 ,134491  ,174.67,143.31,35.84
BEGIN DESCRIPTION:
134412.7
END DESCRIPTION:
XS GIS Cut Line= 6
  942868.2780491   806197.286154  942933.5989454  806279.3174996
  942959.4235334  806327.9279467  942995.8821369  806470.7236313
  942998.9198417  806540.6021091  943109.8145044  806741.1223796
#Sta/Elev= 30
       0 2834.92   25.61 2820.52   39.85 2808.34   49.58 2803.36   67.84 2798.71
    87.7 2798.82  109.29 2796.91  125.83  2794.5  142.14 2792.79  155.65 2794.44
  178.16 2798.56  206.16 2794.62  219.31 2794.02  238.47 2794.85  270.14 2794.52
  289.57 2794.89  303.61 2794.03  450.87 2793.76  494.64  2793.2  511.35 2793.39
  530.94 2794.32  539.49 2795.56  554.37 2803.18  560.84 2805.57  564.68 2807.81
  570.79 2810.08  574.22 2809.86  596.37 2813.36  597.63 2814.72  607.28 2821.94
#Mann= 3 , 0 , 0
       0     .07       0  125.83     .05       0  155.65    .075       0
Bank Sta=125.83,155.65
Exp/Cntr=0.3,0.1

Type RM Length L Ch R = 1 ,134347  ,330.33,364.48,339.35
BEGIN DESCRIPTION:
134269.4
END DESCRIPTION:
XS GIS Cut Line= 6
  942752.8258049  806356.7912638  942877.3921878  806417.5545786
  942971.5764012  806504.1435057  942991.3245554  806584.6559989
  943027.7831588  806674.2826308  943070.3171719  806744.1611086
#Sta/Elev= 30
       0 2860.31    8.78 2854.31   19.46 2848.21   24.91 2842.76   34.05 2839.09
   55.89 2826.91   63.82 2820.78   65.04 2820.67   78.31 2815.03   88.26 2802.01
  113.31 2794.19  121.54 2791.79   130.7 2791.13  135.13 2791.26  144.63 2792.92
   152.8 2793.72  181.81 2793.64  200.18 2794.45   254.4 2793.43  286.36 2794.17
  330.64 2793.55  386.34 2793.89  438.81 2792.89  451.15 2793.73   471.1 2798.48
  483.51 2801.91  493.02 2805.26  501.76 2809.21  511.17 2809.51  528.62 2812.41
#Mann= 3 , 0 , 0
       0    .075       0  113.31     .05       0  144.63    .075       0
Bank Sta=113.31,144.63
Exp/Cntr=0.3,0.1

Type RM Length L Ch R = 1 ,133983  ,261.5,252.28,227.02
BEGIN DESCRIPTION:
133904.9
END DESCRIPTION:
XS GIS Cut Line= 5
  942567.4961071  806540.6021091  942567.4961071  806602.8842764
  942600.9159815  806656.0533291  942696.6200715  806798.8479895
  942798.3995713   806896.070932
#Sta/Elev= 30
       0  2830.8    2.57 2829.72    4.11  2828.8   29.72  2817.8   36.92 2812.52
   52.54 2800.21   60.62  2791.7   80.782787.972   91.32 2786.32   99.06 2786.69
   105.5 2786.63  110.27  2787.5  133.88 2791.58  148.73 2792.91  188.18    2792
  250.03 2791.84  280.74 2792.19  296.98 2792.08  312.16 2792.48  327.13 2793.38
  342.51 2795.44  350.82 2797.41  357.34 2799.48  365.75 2799.36  381.41 2800.09
  385.39 2800.66  405.35 2807.36  417.78 2809.71  425.32 2810.82  437.73 2814.04
#Mann= 3 , 0 , 0
       0    .075       0   80.78     .05       0  110.27    .055       0
Bank Sta=80.78,110.27
Exp/Cntr=0.3,0.1

Type RM Length L Ch R = 1 ,133730  ,188.43,175.85,154.96
BEGIN DESCRIPTION:
133652.6
END DESCRIPTION:
XS GIS Cut Line= 6
   942265.196337   806662.129763  942342.6701011  806727.4506593
  942388.2428433  806786.6951217  942488.5034906  806883.9180642
  942540.1526667  806956.8342468  942562.9385257  807013.0410044
#Sta/Elev= 30
       0 2812.94   12.03 2810.27   35.63 2806.43    40.4 2806.48   55.45 2804.15
   67.84 2800.04   75.42  2798.4   86.69 2794.36   94.12 2793.19  129.87 2793.87
  147.41 2787.09  156.84 2785.28  177.62  2785.6  184.172786.649  198.32  2788.9
  204.74 2789.22  244.47 2788.82  278.36 2789.77  311.04 2789.77  356.99  2789.4
  371.82 2788.55  384.65 2790.29  395.31  2790.2  406.23  2789.3  421.22 2789.83
   427.4 2792.69  434.54 2797.44  440.03 2802.13  452.15    2814  465.74 2823.62
#Mann= 3 , 0 , 0
       0     .07       0  147.41     .05       0  184.17    .055       0
#Block Obstruct= 1 ,-1
       0   77.562838.201
Bank Sta=147.41,184.17
Exp/Cntr=0.5,0.3

Type RM Length L Ch R = 1 ,133555  ,58.53,48.24,35.99
BEGIN DESCRIPTION:
133476.7
END DESCRIPTION:
XS GIS Cut Line= 6
  942186.2026962  806845.9406083  942272.7916233  806903.6662183
  942330.5172333  806952.2766654  942382.1664094  807005.4457181
  942414.0674313  807044.9420264  942435.3344379  807067.7289095
#Sta/Elev= 30
       0 2809.07    7.86 2807.72   21.21 2804.15   47.18 2799.38   62.83 2797.34
   73.35 2795.65    83.4 2793.51   90.77 2791.58   99.52 2790.17  102.26 2789.32
  106.57 2788.94  125.08 2785.72  129.64 2785.57   135.3 2784.53   139.5 2784.14
  144.69 2784.35   152.12785.838  158.23 2787.21  165.64 2787.46  209.81    2787
  237.73  2788.2  251.64 2788.51  267.28 2787.75  270.59 2787.83  291.86 2801.02
  304.43 2808.53  313.72 2813.87  317.83 2815.96  332.97 2826.33   335.6 2827.52
#Mann= 3 , 0 , 0
       0    .055       0  125.08     .05       0   152.1    .055       0
#XS Ineff= 2 , 0
       0   113.5 2790.64   165.5       0 2790.64
Permanent Ineff=
       F       F
Bank Sta=125.08,152.1
Exp/Cntr=0.5,0.3

Type RM Length L Ch R = 3 ,133542  ,,,
Node Photo=H:\PROJ\06-0741\CE\GIS\DATA\FRENCH_BROAD_RIVER\SHAPEFILES\survey_data\photos\FBSTR_1258.JPG
BEGIN DESCRIPTION:
133461.2  FBSTR_1258
END DESCRIPTION:
Bridge Culvert--1,0,-1,-1, 0
Deck Dist Width WeirC Skew NumUp NumDn MinLoCord MaxHiCord MaxSubmerge Is_Ogee
9.5,12,2.6,0, 7, 7, , , 0.95, 0, 0,0,,
       0   123.5   123.5   139.5   155.5   155.5     300
 2790.17 2790.64 2790.64 2790.64 2790.64 2790.64 2790.49
                 2790.14 2790.14 2790.14
       0     134     134     150     166     166     300
 2790.17 2790.64 2790.64 2790.64 2790.64 2790.64 2790.49
                 2790.14 2790.14 2790.14
Pier Skew, UpSta & Num, DnSta & Num=  ,134.1, 2 ,144.6, 2 , 0 , 0 , 0 ,,
     .75     .75
    2780 2790.14
     .75     .75
    2780 2790.14
Pier Skew, UpSta & Num, DnSta & Num=  ,144.7, 2 ,155.2, 2 , 0 , 0 , 0 ,,
     .75     .75
    2780 2790.14
     .75     .75
    2780 2790.14
BR Coef=-1 , 0 , 0 ,, 0 ,,,0.8,0,,0,
WSPro=,,,, 1 ,,,, 0 ,,,, 0 ,,,,-1 ,-1 ,-1 , 0 , 0 , 0 , 0 , 0
BC Design=,, 0 ,, 0 ,,,,,,

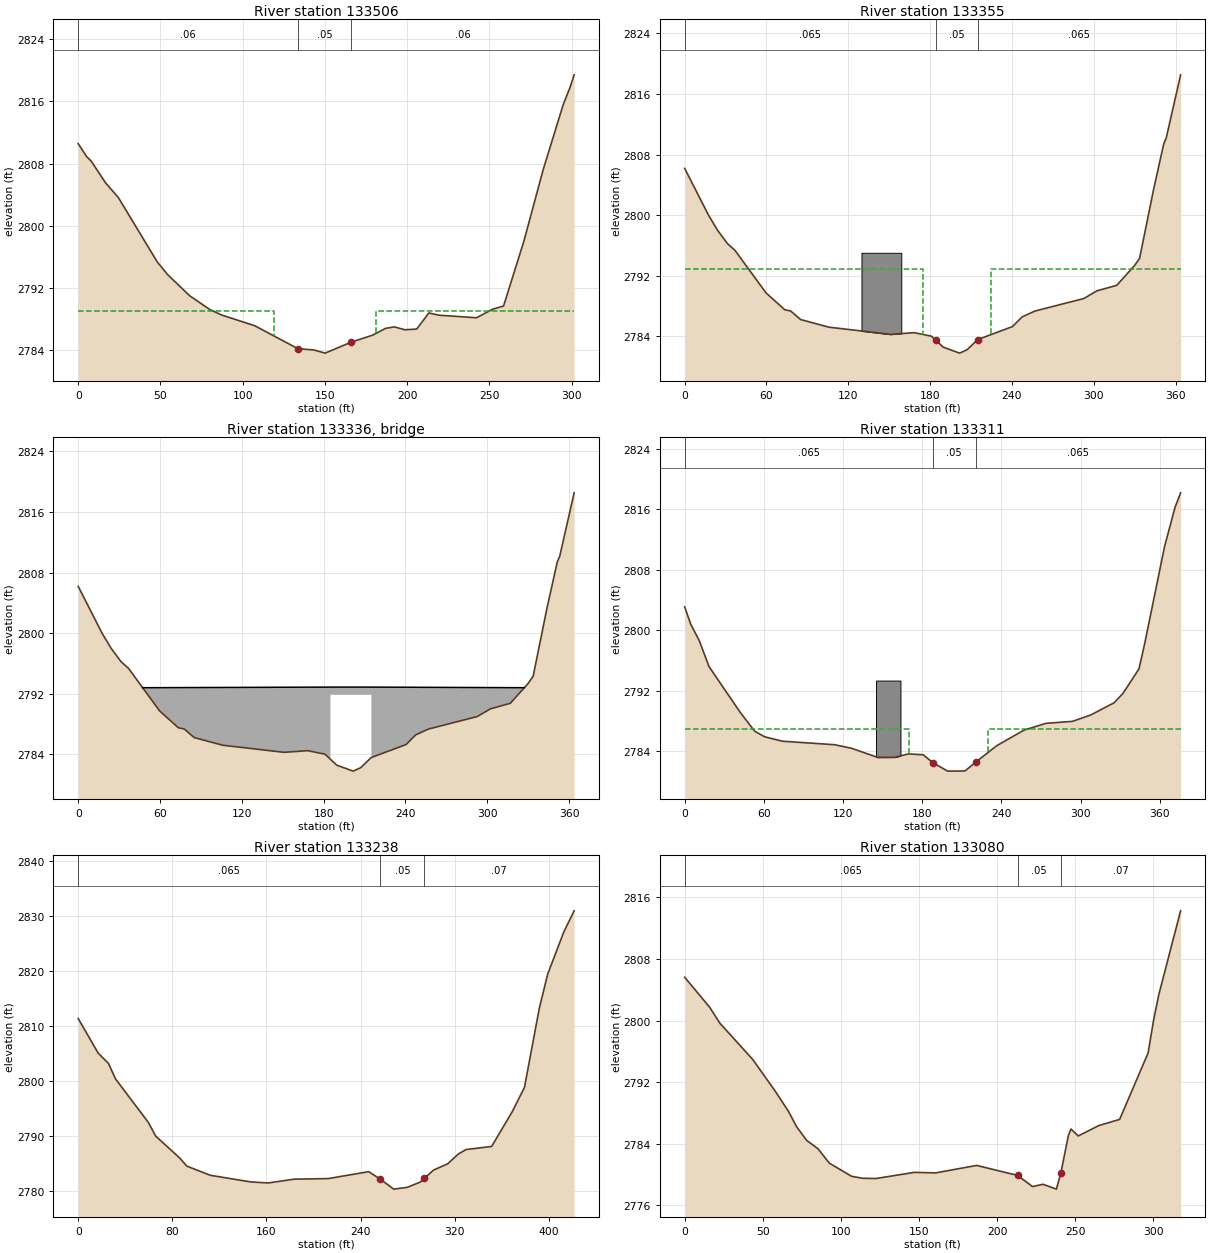
Type RM Length L Ch R = 1 ,133506  ,149.14,151.82,98.49
BEGIN DESCRIPTION:
133428.5
END DESCRIPTION:
XS GIS Cut Line= 5
  942157.3404033  806905.1850708  942240.8906014   806944.681379
  942295.5774823  806981.1399825  942347.2276826    807037.34674
  942403.4334159  807073.8053434
#Sta/Elev= 30
       0 2810.56    5.11  2808.9    7.91 2808.31   16.61 2805.51   24.35 2803.63
    48.1  2795.3   54.47 2793.65    67.8 2790.95   79.93 2789.19   87.07 2788.48
  107.22  2787.1  133.59 2784.13  143.48 2783.96  150.09 2783.56     1662784.981
  178.95 2785.87  186.81 2786.75  192.21 2786.94   198.6 2786.57  205.76 2786.66
  213.16 2788.74  219.21 2788.45   242.1 2788.12  251.89 2789.22  258.57 2789.64
  270.88 2797.96  282.57 2807.15  294.78 2815.56  299.04 2817.86  301.47 2819.43
#Mann= 3 , 0 , 0
       0     .06       0  133.59     .05       0     166     .06       0
#XS Ineff= 2 , 0
       0     119    2789     181       0    2789
Permanent Ineff=
       F       F
Bank Sta=133.59,166
Exp/Cntr=0.5,0.3

Type RM Length L Ch R = 1 ,133355  ,50.75,43.31,32.65
BEGIN DESCRIPTION:
133276.7
END DESCRIPTION:
XS GIS Cut Line= 6
  942072.2703287  806993.2928503  942119.3629475  807052.5373127
  942174.0498284  807087.4770637  942237.8518723  807114.8205041
  942321.4020703  807143.6838212  942386.7239908  807145.2026737
#Sta/Elev= 30
       0 2806.17    17.6 2799.96   24.18 2797.99   31.44 2796.23   36.86 2795.36
   59.62 2789.75   73.38 2787.52   77.77 2787.35   85.06 2786.22  105.93 2785.21
  150.97 2784.27  168.28 2784.49  180.93 2784.03   184.3 2783.47  189.61 2782.58
  201.63 2781.79  207.16 2782.24  214.88 2783.58  240.39 2785.29  247.48 2786.57
  256.84 2787.34  292.81    2789   302.3 2790.01  316.91 2790.74  329.89 2793.34
  333.64  2794.3  343.85 2803.34  351.32 2809.38  353.15 2810.16  363.73 2818.52
#Mann= 3 , 0 , 0
       0    .065       0   184.3     .05       0  214.88    .065       0
#XS Ineff= 2 , 0
       0     175 2792.88     225       0 2792.88
Permanent Ineff=
       F       F
#Block Obstruct= 1 ,-1
  129.66  158.862795.035
Bank Sta=184.3,214.88
Exp/Cntr=0.5,0.3

Type RM Length L Ch R = 3 ,133336  ,,,
Node Photo=H:\PROJ\06-0741\CE\GIS\DATA\FRENCH_BROAD_RIVER\SHAPEFILES\survey_data\photos\FBSTR_1778.JPG
BEGIN DESCRIPTION:
133256  FBSTR_1778
END DESCRIPTION:
Bridge Culvert--1,0,-1,-1, 0
Deck Dist Width WeirC Skew NumUp NumDn MinLoCord MaxHiCord MaxSubmerge Is_Ogee
15,12,2.6,0, 7, 7, , , 0.95, 0, 1,1,,
   47.19     185     185     200     215     215  327.19
  2792.8 2792.88 2792.88 2792.88 2792.88 2792.88  2792.8
                 2791.88 2791.88 2791.88
   26.26     185     185     200     215     215   337.4
 2792.81 2792.88 2792.88 2792.88 2792.88 2792.88  2792.8
                 2791.88 2791.88 2791.88
BR Coef=-1 , 0 , 0 ,, 0 ,,,0.8,0,,0,
WSPro=,,,, 1 ,,,, 0 ,,,, 0 ,,,,-1 ,-1 ,-1 , 0 , 0 , 0 , 0 , 0
BC Design=,, 0 ,, 0 ,,,,,,

Type RM Length L Ch R = 1 ,133311  ,152.36,73.11,48.79
BEGIN DESCRIPTION:
133233.4
END DESCRIPTION:
XS GIS Cut Line= 6
  942045.8742506  807035.8514436  942087.6288661  807089.5356566
  942137.3362053  807125.3244492  942225.8147364  807155.1494672
  942348.0951593  807178.0141877  942371.9553785  807193.9206591
#Sta/Elev= 30
       0 2803.11    4.64  2800.8   11.12 2798.62   18.42 2795.22   42.08 2789.16
   53.04 2786.67   60.59 2785.93   73.95 2785.35  113.67 2784.88  126.31 2784.42
  146.02 2783.22  159.39 2783.23   169.5 2783.66  180.65 2783.56  188.052782.519
  199.24 2781.39  212.41 2781.41  220.41 2782.56   236.2 2784.72  256.98  2786.8
  273.78 2787.71  293.83 2787.97  307.65 2788.81  325.33 2790.42  332.16 2791.67
  344.26 2794.91  348.45 2798.14  363.65 2811.09  371.62 2816.29  375.81 2818.19
#Mann= 3 , 0 , 0
       0    .065       0  188.05     .05       0  220.41    .065       0
#XS Ineff= 2 , 0
       0     170    2787     230       0    2787
Permanent Ineff=
       F       F
#Block Obstruct= 1 ,-1
  144.98  163.522793.367
Bank Sta=188.05,220.41
Exp/Cntr=0.5,0.3

Type RM Length L Ch R = 1 ,133238  ,90.53,158.4,184.12
BEGIN DESCRIPTION:
133160.3
END DESCRIPTION:
XS GIS Cut Line= 6
   941941.488224  807227.7215269  942183.0666705  807232.6928753
   942237.745358  807215.7919293  942268.5638264   807214.798479
  942307.3350183  807220.7632777  942355.0544326  807242.6345479
#Sta/Elev= 30
       0 2811.34   17.01 2805.05   25.73  2803.2   31.69  2800.4   59.79 2792.44
   65.83 2790.01   86.39 2786.01   92.33 2784.56  112.18  2782.9  146.57 2781.69
  161.49  2781.5   183.6 2782.19  212.48 2782.29  246.93 2783.55  256.872782.191
  268.21 2780.38  279.82 2780.71  290.83 2781.66  294.31 2782.33  302.06 2783.83
  314.13 2784.98  323.34 2786.78  329.77 2787.56  351.51 2788.13  369.15 2794.49
   379.4 2798.85  392.02  2813.2  399.15  2819.4  412.86 2827.07  421.64 2830.89
#Mann= 3 , 0 , 0
       0    .065       0  256.87     .05       0  294.31     .07       0
Bank Sta=256.87,294.31
Exp/Cntr=0.3,0.1

Type RM Length L Ch R = 1 ,133080  ,196.35,272.12,295.66
BEGIN DESCRIPTION:
133001.9
END DESCRIPTION:
XS GIS Cut Line= 6
  941948.4474973  807301.2890852  942105.5232624  807335.0899529
  942157.2185264  807352.9843492   942182.072196  807369.8852951
  942209.9092891   807384.797292  942249.6749556  807391.7565653
#Sta/Elev= 30
       0 2805.63   16.09 2801.71   22.45 2799.68   43.67 2794.92   58.02 2790.81
   66.47 2788.19   71.57 2786.23   78.13 2784.42   85.28 2783.36   92.54 2781.48
  106.89 2779.76  114.05 2779.51  122.48 2779.48  147.07 2780.28   160.6 2780.21
  186.87 2781.18  213.06 2779.88  222.59 2778.43  229.31 2778.73  237.89  2778.1
  240.75 2780.22  245.59  2785.1  247.21 2785.91  251.88 2785.01  265.04 2786.36
  278.35 2787.16  296.58 2795.79  300.21 2800.21   303.5 2803.44  317.38 2814.26
#Mann= 3 , 0 , 0
       0    .065       0  213.06     .05       0  240.75     .07       0
Bank Sta=213.06,240.75
Exp/Cntr=0.3,0.1

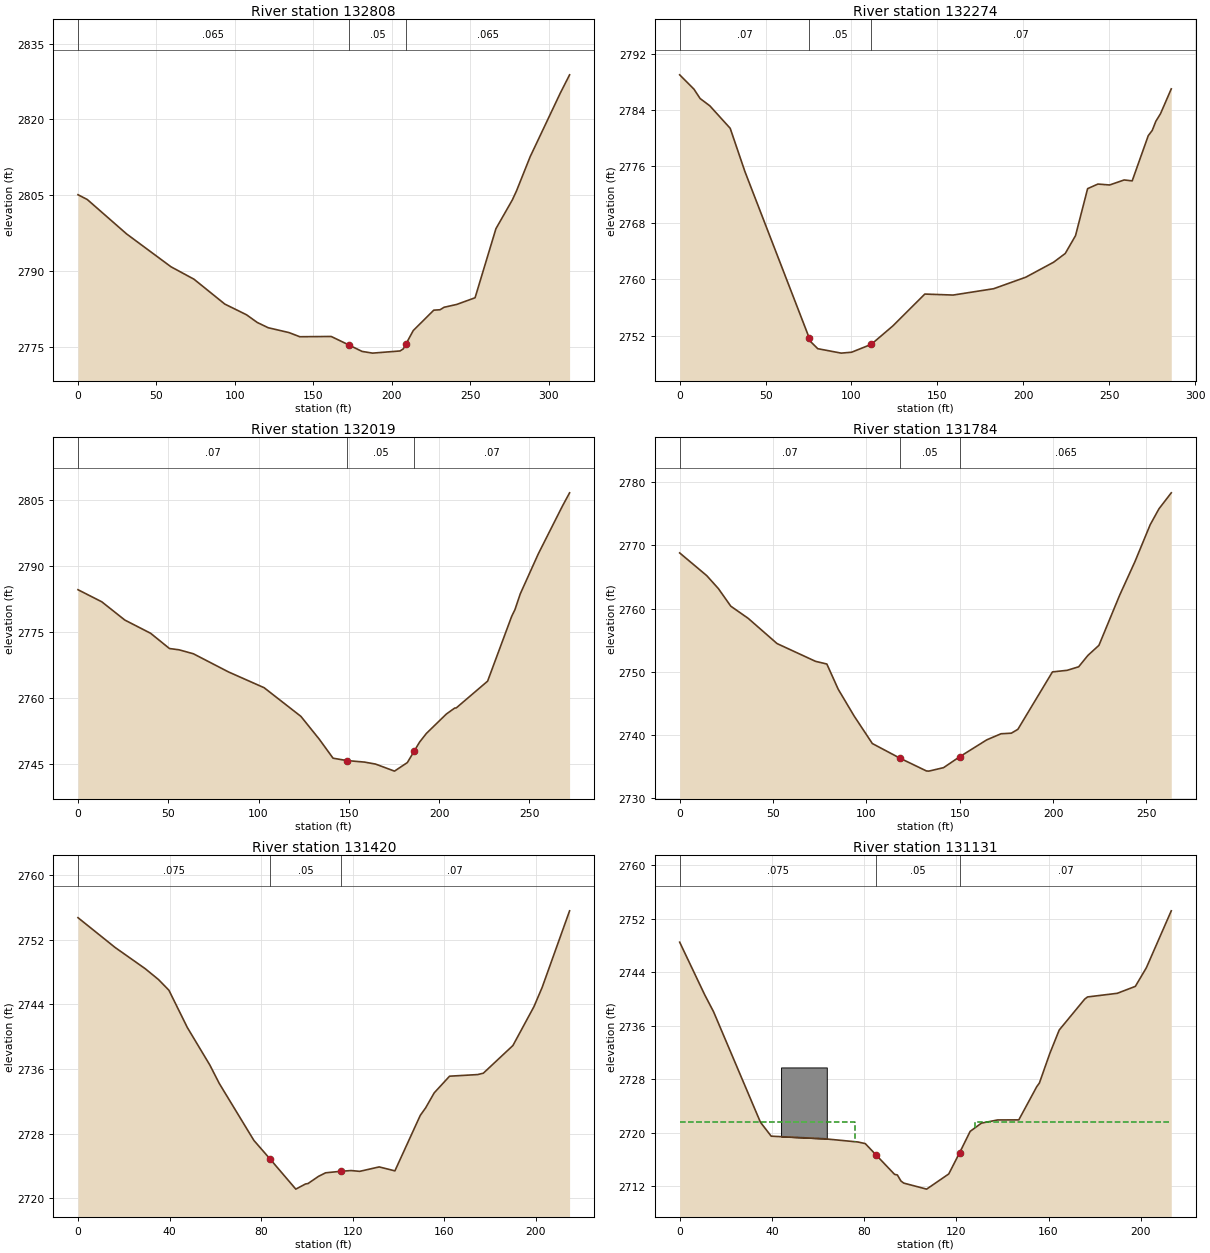
Type RM Length L Ch R = 1 ,132808  ,547.21,533.91,434.49
BEGIN DESCRIPTION:
132729.8
END DESCRIPTION:
XS GIS Cut Line= 6
  941871.8442824  807425.0627562  941941.7227602  807508.6129542
  941972.1049297  807543.5527052  942020.7164009  807590.6442998
  942061.7315616  807625.5840508  942086.0372972  807652.9274913
#Sta/Elev= 30
       0 2805.13    5.93 2804.18      31 2797.38   59.29 2790.89   73.92 2788.44
    93.6 2783.52  107.42 2781.41  114.32 2779.88  121.24 2778.85   134.5 2777.89
  141.39 2777.07  161.41 2777.12  172.62 2775.45  181.06 2774.17   187.8 2773.83
  205.33 2774.26   207.4 2774.68  209.212775.716  213.71 2778.29  226.79 2782.32
   230.8  2782.4  233.37 2782.89  241.42 2783.45  253.12 2784.77  266.42 2798.42
  276.87  2804.1  279.55  2805.9  288.21 2812.62   307.4 2825.18  313.37 2828.82
#Mann= 3 , 0 , 0
       0    .065       0  172.62     .05       0  209.21    .065       0
Bank Sta=172.62,209.21
Exp/Cntr=0.3,0.1

Type RM Length L Ch R = 1 ,132274  ,235.58,254.68,285.32
BEGIN DESCRIPTION:
132195.8
END DESCRIPTION:
XS GIS Cut Line= 6
  941512.6658955  807835.7561522  941544.5669174  807863.0995927
  941570.3915054  807876.7713129  941615.9652718  807888.9241807
   941710.148461  807891.9629098  941764.8363662  807940.5733568
#Sta/Elev= 30
       0 2788.99    8.31 2786.96    11.9 2785.63   17.58 2784.59   29.41 2781.41
   37.99 2775.27   75.34 2751.74   76.25 2751.17   80.37 2750.18   94.01 2749.55
  100.09 2749.68  111.48 2750.79  124.05  2753.4  142.68 2757.92  159.18 2757.78
  182.77 2758.68  201.45 2760.31  217.68 2762.44  224.41 2763.67   230.4  2766.2
  237.44 2772.86  243.43 2773.51  250.24 2773.38  258.71 2774.09  263.38 2773.96
  272.74 2780.37  275.05 2781.11  277.14  2782.4   279.9  2783.5  286.13    2787
#Mann= 3 , 0 , 0
       0     .07       0   75.34     .05       0  111.48     .07       0
Bank Sta=75.34,111.48
Exp/Cntr=0.3,0.1

Type RM Length L Ch R = 1 ,132019  ,225.52,234.71,242.19
BEGIN DESCRIPTION:
131941.2
END DESCRIPTION:
XS GIS Cut Line= 5
  941388.1005367    808021.08585  941470.1318823  808075.7737551
  941503.5517567  808109.1936295  941552.1632279  808141.0946514
  941615.9652718  808165.4003871
#Sta/Elev= 30
       0 2784.56   13.18 2781.82   25.95 2777.68   40.24 2774.68   50.65 2771.23
   56.03 2770.93   63.91 2770.04   83.36 2765.92   103.1 2762.34  123.47 2755.84
  133.65 2750.66  141.27 2746.36  148.86 2745.83  158.65 2745.48  164.79 2745.03
  175.29 2743.43  182.41 2745.37  186.37 2748.08   189.2 2750.02  192.97 2751.98
     204 2756.37  208.64 2757.73  209.49 2757.76  226.87 2763.83   240.2 2778.53
     242 2780.04  244.96 2783.63  254.96 2792.71  268.28 2803.51  272.27 2806.53
#Mann= 3 , 0 , 0
       0     .07       0  148.86     .05       0  186.37     .07       0
Bank Sta=148.86,186.37
Exp/Cntr=0.3,0.1

Type RM Length L Ch R = 1 ,131784  ,356.34,363.86,385.29
BEGIN DESCRIPTION:
131706.5
END DESCRIPTION:
XS GIS Cut Line= 6
  941278.7257506   808171.476821  941296.9540282  808217.0495631
  941328.8550501  808261.1034529  941365.3136535  808289.9657458
  941413.9251248  808327.9432016  941451.9025806  808362.8829526
#Sta/Elev= 30
       0 2768.82    14.5 2765.22   20.72 2763.17   27.38 2760.38   36.67 2758.46
   52.14 2754.46   72.79 2751.64   78.82 2751.22   84.89 2747.23   93.41 2742.99
  103.18 2738.62  117.772736.331  132.12 2734.28  133.42 2734.25  141.32  2734.8
  149.97 2736.53  164.49 2739.21   172.1 2740.17   177.6 2740.26  181.11 2740.87
  199.63 2749.97  207.51 2750.22  213.67 2750.78  218.61 2752.58  224.53 2754.18
  235.65 2762.14  243.83 2767.45  251.97 2773.28  256.68 2775.81  263.27 2778.34
#Mann= 3 , 0 , 0
       0     .07       0  117.77     .05       0  149.97    .065       0
Bank Sta=117.77,149.97
Exp/Cntr=0.3,0.1

Type RM Length L Ch R = 1 ,131420  ,268.48,289.85,289.01
BEGIN DESCRIPTION:
131342.6
END DESCRIPTION:
XS GIS Cut Line= 5
  941002.2495443  808388.7075407  941015.9212646  808435.7991353
  941049.3411389  808473.7765911  941076.6856036  808517.8304809
  941120.7394933  808563.4032231
#Sta/Elev= 30
       0 2754.72   16.24 2751.03   29.32 2748.42   35.16 2747.07   39.74 2745.74
    47.8 2741.12   57.65 2736.47   61.75  2734.2   76.88 2727.15   83.91 2724.86
    95.2 2721.12   99.45 2721.76  100.53 2721.81  105.12  2722.7  108.22 2723.14
  114.92 2723.33   119.4 2723.42  123.12 2723.32  131.64 2723.87  138.51 2723.38
   149.6 2730.25  151.92 2731.17   155.7 2733.04   162.4  2735.1  174.68  2735.3
  177.16 2735.47   190.1  2738.9   199.3 2743.72  202.88  2746.1  214.86 2755.57
#Mann= 3 , 0 , 0
       0    .075       0   83.91     .05       0  114.92     .07       0
Bank Sta=83.91,114.92
Exp/Cntr=0.5,0.3

Type RM Length L Ch R = 1 ,131131  ,58.16,45.42,41.32
BEGIN DESCRIPTION:
131052.7
END DESCRIPTION:
XS GIS Cut Line= 4
  940778.9423907  808549.7315028  940800.2093973   808604.419408
  940827.5538619  808663.6638704  940886.7983243  808730.5046433
#Sta/Elev= 30
       0 2748.49   10.87 2740.61   14.68  2738.1   35.03 2721.56    39.7 2719.47
   62.55 2719.09   77.34  2718.6   80.51 2718.36   85.222716.654   93.21 2713.76
   94.43 2713.67      96 2712.76   97.21 2712.45  107.13 2711.55  116.72 2713.82
   121.4 2716.97  126.01 2720.19  130.88 2721.42  137.95  2721.9  147.11 2721.91
   154.9 2726.88  156.04 2727.42   160.5 2731.79  164.64 2735.35  175.71 2739.98
  176.94  2740.3  189.81 2740.84  197.67 2741.88  202.45 2744.67  213.25 2753.18
#Mann= 3 , 0 , 0
       0    .075       0   85.22     .05       0   121.4     .07       0
#XS Ineff= 2 , 0
       0   76.13 2721.55  128.13       02721.555
Permanent Ineff=
       F       F
#Block Obstruct= 1 ,-1
   43.98   63.812729.754
Bank Sta=85.22,121.4
Exp/Cntr=0.5,0.3

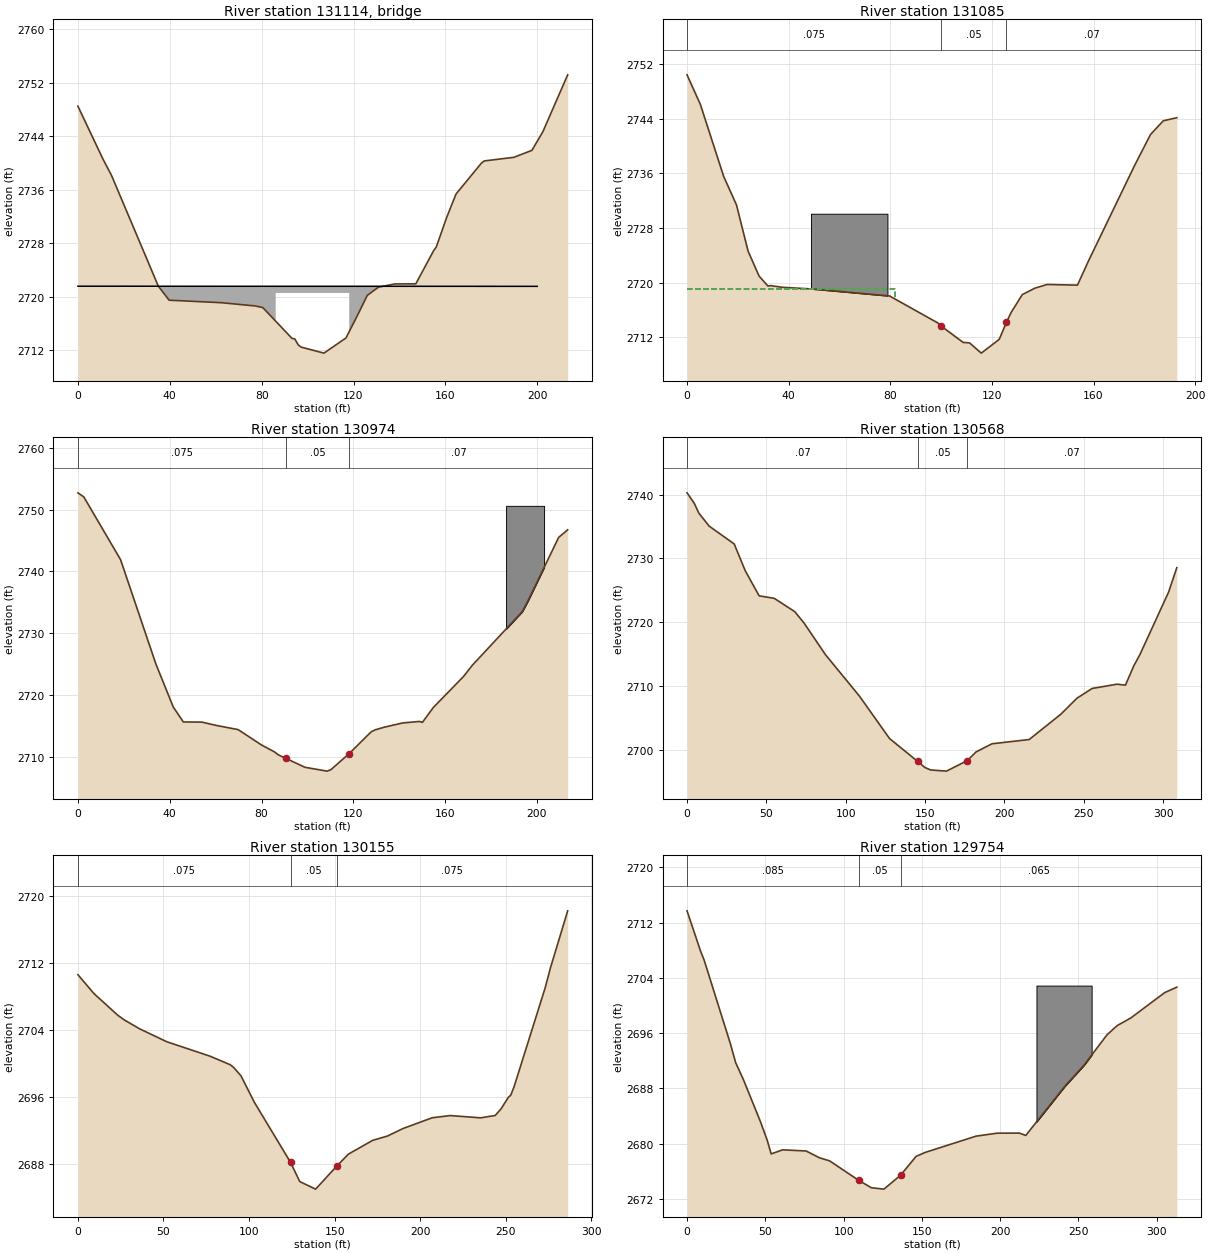
Type RM Length L Ch R = 3 ,131114  ,,,
Node Photo=H:\PROJ\06-0741\CE\GIS\DATA\FRENCH_BROAD_RIVER\SHAPEFILES\survey_data\photos\FBSTR_1777.JPG
BEGIN DESCRIPTION:
131030  FBSTR_1777
END DESCRIPTION:
Bridge Culvert--1,0,-1,-1, 0
Deck Dist Width WeirC Skew NumUp NumDn MinLoCord MaxHiCord MaxSubmerge Is_Ogee
16,12,2.6,0, 7, 7, , , 0.95, 0, 1,1,,
       0   86.13   86.13  102.13  118.13  118.13     200
 2721.56 2721.55 2721.55 2721.55 2721.55 2721.55 2721.54
                 2720.55 2720.55 2720.55
       0   96.82   96.82  112.82  128.82  128.82     200
 2721.56 2721.55 2721.55 2721.55 2721.55 2721.55 2721.54
                 2720.55 2720.55 2720.55
BR Coef=-1 , 0 , 0 ,, 0 ,,,0.8,0,,0,
WSPro=,,,, 1 ,,,, 0 ,,,, 0 ,,,,-1 ,-1 ,-1 , 0 , 0 , 0 , 0 , 0
BC Design=,, 0 ,, 0 ,,,,,,

Type RM Length L Ch R = 1 ,131085  ,131.01,110.74,94.09
BEGIN DESCRIPTION:
131007.3
END DESCRIPTION:
XS GIS Cut Line= 5
  940719.6979283  808581.6325248  940750.0790736  808624.1675621
  940778.9423907  808668.2214519  940798.6905448  808698.6036214
  940836.6680007  808733.5423482
#Sta/Elev= 29
       0 2750.41    5.24 2746.09   14.44 2735.52   19.46 2731.37   24.05 2724.58
   28.36 2720.95   31.82  2719.5      33 2719.55   37.36 2719.31   50.01 2719.04
   79.71 2718.04   98.75 2714.08  100.09 2713.68  101.08 2713.34  108.67 2711.24
  111.19 2711.17  115.82 2709.67  122.89 2711.69   125.7 2714.17   127.6 2715.64
  131.96 2718.24  136.86 2719.17   141.7 2719.72  153.67 2719.62  157.91 2723.08
  176.22 2737.18  182.42 2741.67  187.44 2743.68  192.78 2744.13
#Mann= 3 , 0 , 0
       0    .075       0  100.09     .05       0   125.7     .07       0
#XS Ineff= 2 , 0
       0   81.82    2719  143.82       0    2719
Permanent Ineff=
       F       F
#Block Obstruct= 1 ,-1
   48.79   78.882730.079
Bank Sta=100.09,125.7
Exp/Cntr=0.5,0.3

Type RM Length L Ch R = 1 ,130974  ,396.07,406.96,403.93
BEGIN DESCRIPTION:
130896.6
END DESCRIPTION:
XS GIS Cut Line= 5
  940605.7655607  808680.3743197  940648.2995739  808704.6800553
  940678.6817434  808725.9470618  940725.7743622  808768.4820992
  940783.4999722  808795.8255396
#Sta/Elev= 30
       0 2752.72    2.55 2752.07   18.59  2741.9   33.97 2725.02   41.54 2718.05
   45.94 2715.62   53.98  2715.6   60.04 2715.08   69.84 2714.38   79.94 2711.91
   85.73 2710.76    87.3  2710.3   90.472709.749   98.96 2708.28  108.57 2707.66
   110.2 2707.88  118.21  2710.5  127.83 2714.04  129.64 2714.36  133.59 2714.78
   141.5 2715.46  148.75  2715.7  150.12 2715.56  154.84 2717.95  168.04 2722.99
  171.88 2724.81  193.61 2733.48  196.07 2735.19  209.48  2745.5  213.41 2746.73
#Mann= 3 , 0 , 0
       0    .075       0   90.47     .05       0  118.21     .07       0
#Block Obstruct= 1 ,-1
  186.57  203.132750.613
Bank Sta=90.47,118.21
Exp/Cntr=0.3,0.1

Type RM Length L Ch R = 1 ,130568  ,380.33,412.61,403.38
BEGIN DESCRIPTION:
130489.6
END DESCRIPTION:
XS GIS Cut Line= 6
  940298.9071849  808868.7417223  940326.2516495  808934.0636428
  940367.2668103  808982.6740898  940414.3594291  809017.6138408
  940437.1452881  809044.9572813  940499.4284795   809095.087605
#Sta/Elev= 30
       0 2740.28    4.54 2738.65    7.41 2737.11   13.93 2735.06   29.71 2732.27
   36.69 2728.06   45.41 2724.14   55.01 2723.73   67.94 2721.64   73.87 2719.82
   87.22 2714.91  108.61 2708.42  127.57 2701.77  145.32 2698.17  149.85 2697.22
  153.55 2696.83  163.46 2696.65  176.41 2698.28  182.15 2699.66  192.19 2700.94
  215.55  2701.6  235.52 2705.57  245.63 2708.07  255.23 2709.61  270.94 2710.28
  276.24 2710.13  281.52 2713.17  285.35 2714.92  303.42 2724.71   308.6 2728.55
#Mann= 3 , 0 , 0
       0     .07       0  145.32     .05       0  176.41     .07       0
Bank Sta=145.32,176.41
Exp/Cntr=0.3,0.1

Type RM Length L Ch R = 1 ,130155  ,370.63,400.87,440.37
BEGIN DESCRIPTION:
130077.0
END DESCRIPTION:
XS GIS Cut Line= 6
  940043.6990093  809081.4158847  940031.5461415  809143.6990762
  940033.0660181  809166.4849352  940042.1801569  809202.9435386
  940098.3869145  809253.0738623  940160.6701059  809313.8371771
#Sta/Elev= 30
       0 2710.66    9.34 2708.41   23.34 2705.81   27.33 2705.23   36.11 2704.19
   51.98 2702.65   77.18 2700.93   89.02 2699.91   91.05 2699.58    95.3 2698.58
   103.1 2695.43   124.3 2688.24  129.65 2685.96  138.92 2685.06  151.212687.798
  158.09 2689.24  172.24 2690.88  180.93  2691.4  190.06  2692.3  207.06 2693.58
  217.57 2693.84  235.35 2693.57  243.83 2693.85  247.26 2694.64  251.57 2696.03
  252.87 2696.25  254.91  2697.3     273 2709.06  276.11 2711.46   286.2 2718.28
#Mann= 3 , 0 , 0
       0    .075       0   124.3     .05       0  151.21    .075       0
Bank Sta=124.3,151.21
Exp/Cntr=0.3,0.1

Type RM Length L Ch R = 1 ,129754  ,347.09,321.21,232.21
BEGIN DESCRIPTION:
129676.1
END DESCRIPTION:
XS GIS Cut Line= 6
  939644.1762967  809161.9273537  939666.9631799  809202.9435386
  939671.5207614  809277.3795979  939680.6349001  809310.7994722
  939700.3830543  809357.8910669  939768.7426796    809438.40356
#Sta/Elev= 30
       0  2713.7     8.7 2707.83   10.88  2706.6   27.74 2694.43   31.04 2691.73
   35.98 2689.28   46.92 2683.16   51.17 2680.52   53.74 2678.51   61.08  2679.1
   76.13 2678.93   84.44 2677.96   91.09  2677.5  109.81 2674.66  117.76 2673.61
  125.76 2673.41  136.38 2675.42   146.3 2678.15   152.2 2678.73  184.61 2681.08
  198.06 2681.51  212.31 2681.52  216.37 2681.18  241.32  2688.3   253.6 2691.36
  268.22 2695.74  274.72 2697.08  283.59 2698.21   305.1 2701.86  312.84 2702.65
#Mann= 3 , 0 , 0
       0    .085       0  109.81     .05       0  136.38    .065       0
#Block Obstruct= 1 ,-1
   223.2  258.432702.877
Bank Sta=109.81,136.38
Exp/Cntr=0.5,0.3