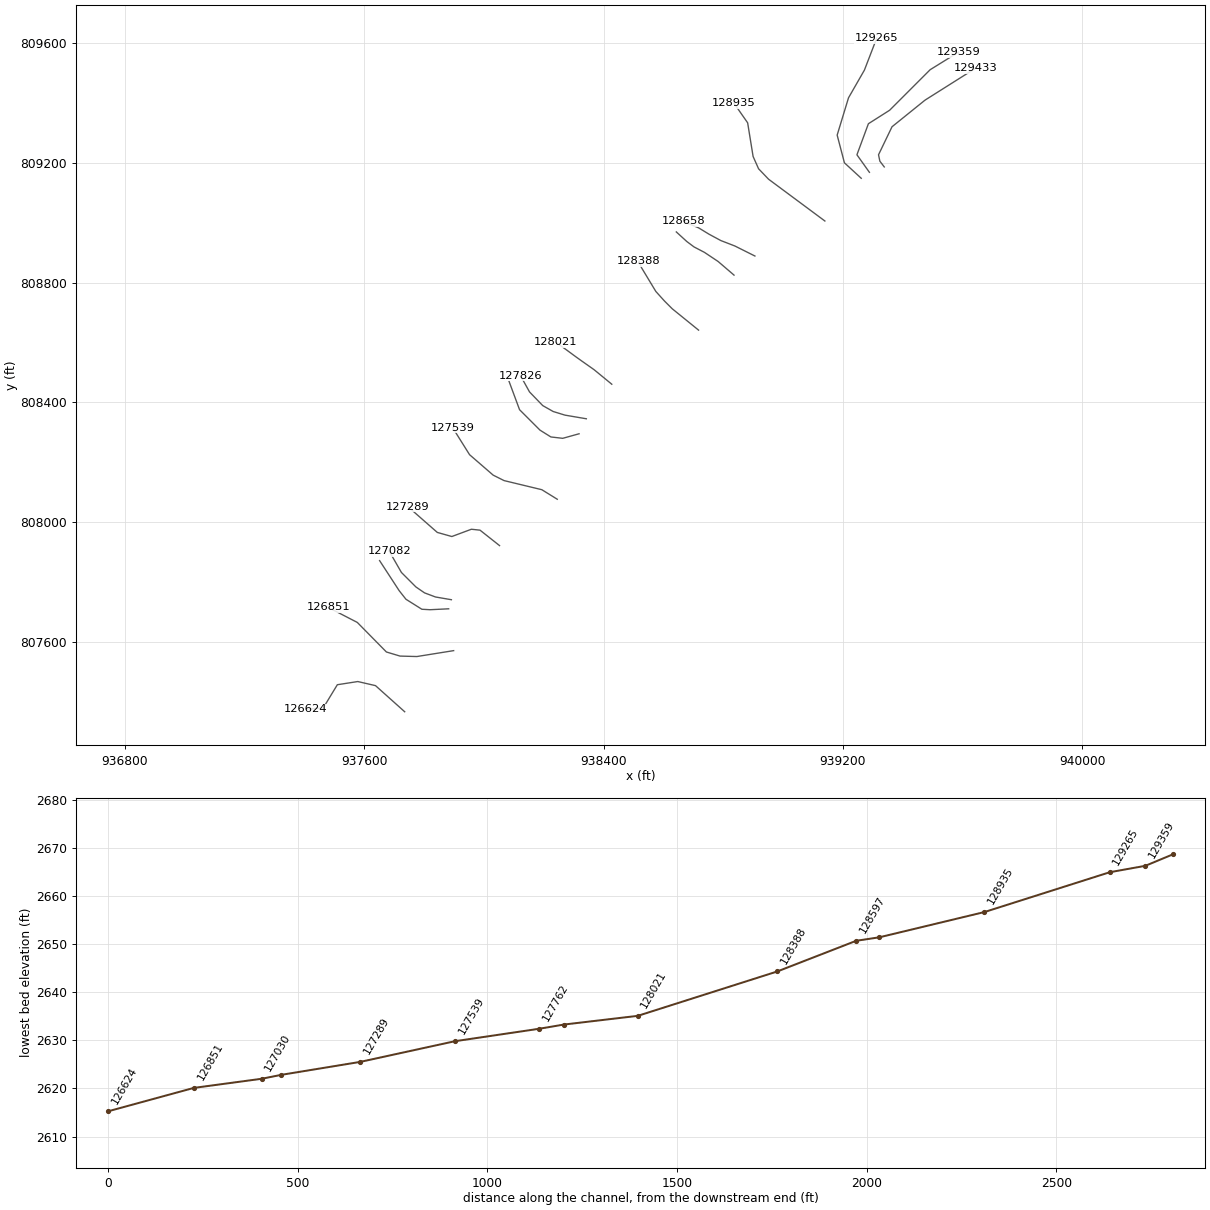
HEC-RAS study lds_big_laurel_crk.prj: lds_big_laurel_crk

--- lds_big_laurel_crk.g20 (geometry) --- (continued)

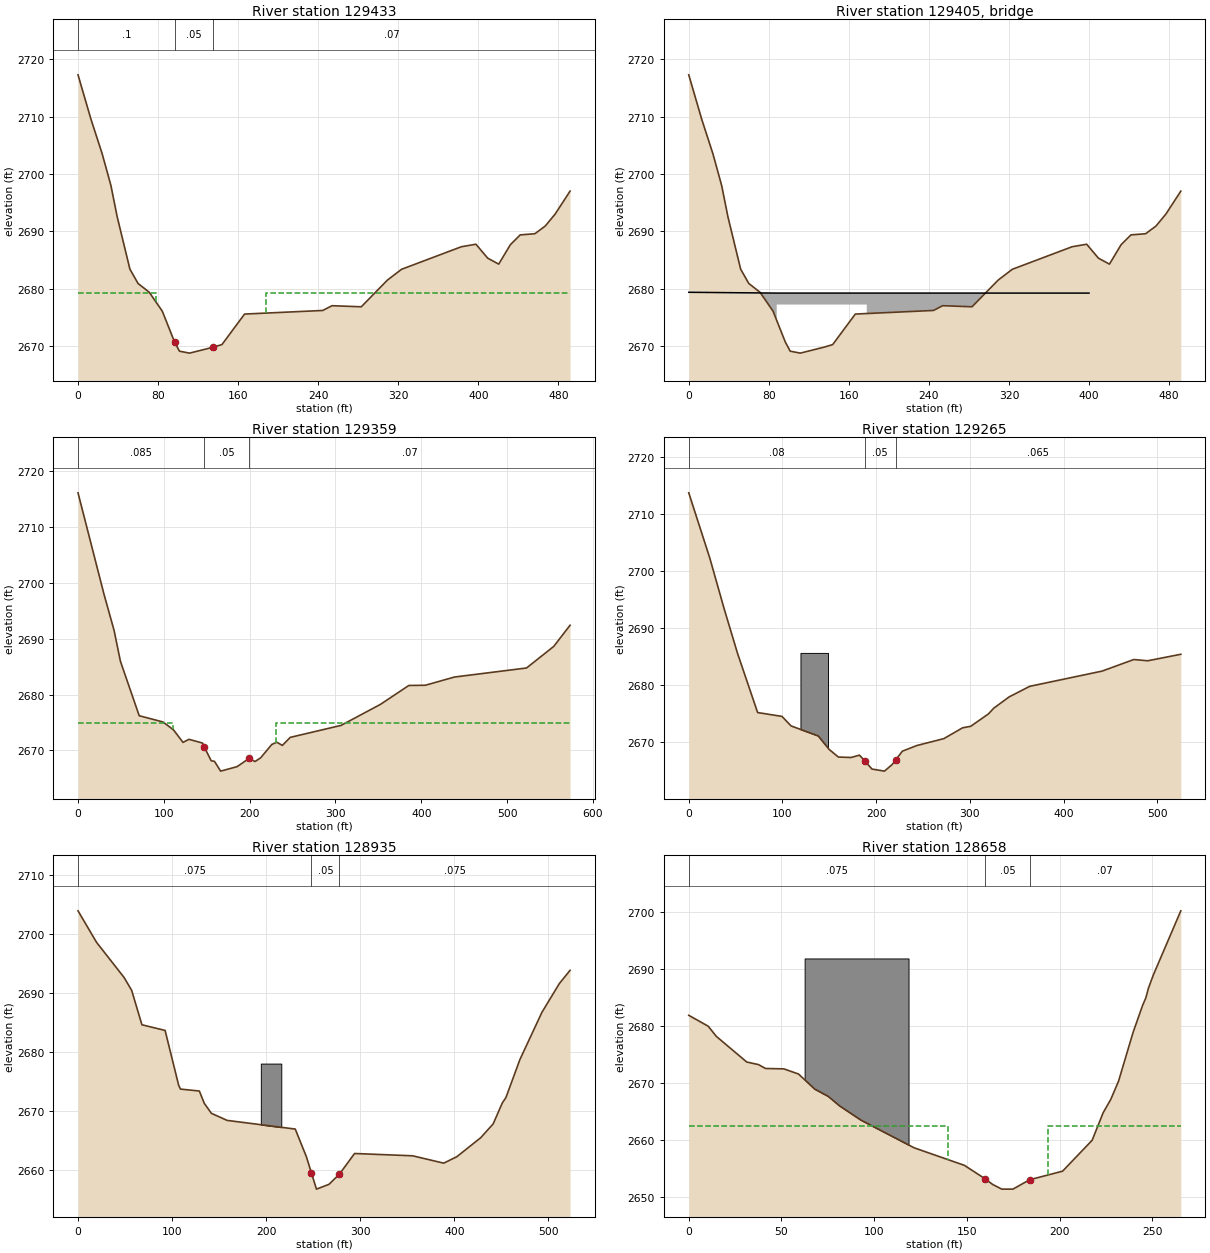
Type RM Length L Ch R = 1 ,129433  ,73.19,73.97,71.18
BEGIN DESCRIPTION:
129354.9
END DESCRIPTION:
XS GIS Cut Line= 6
  939338.3123954  809186.1880256  939323.6502973  809205.3616172
  939319.1388038  809226.7904435  939364.2537395  809320.4041911
  939474.7848198   809409.505421   939642.836675  809515.5250077
#Sta/Elev= 30
       0 2717.27   12.87 2709.57   24.14 2703.51   32.87 2697.98    39.1 2692.55
   51.87 2683.38   59.99 2680.89   71.25 2679.35   84.25 2676.05   96.49 2670.68
  101.39 2669.08  111.48 2668.74  135.03 2669.77  143.84 2670.23  166.43 2675.55
  244.59 2676.18  253.77 2677.01  283.09 2676.82  309.17 2681.47  323.35 2683.36
  383.09 2687.29  397.66 2687.73  409.43  2685.3  420.43 2684.26  432.04 2687.64
  441.92 2689.36  456.59 2689.56  466.93  2690.9  476.87    2693  491.74 2696.99
#Mann= 3 , 0 , 0
       0      .1       0   96.49     .05       0  135.03     .07       0
#XS Ineff= 2 , 0
       0   77.88 2679.21  187.88       0 2679.21
Permanent Ineff=
       F       F
Bank Sta=96.49,135.03
Exp/Cntr=0.5,0.3

Type RM Length L Ch R = 3 ,129405  ,,,
BEGIN DESCRIPTION:
129329  FBSTR_1274
END DESCRIPTION:
Bridge Culvert--1,0,-1,-1, 0
Deck Dist Width WeirC Skew NumUp NumDn MinLoCord MaxHiCord MaxSubmerge Is_Ogee
5,40,2.6,0, 7, 7, , , 0.95, 0, 1,1,,
       0   87.88   87.88  132.88  177.88  177.88     400
 2679.35 2679.21 2679.21 2679.21 2679.21 2679.21 2679.21
                 2677.21 2677.21 2677.21
       0  125.55  125.55  170.55  215.55  215.55     400
 2679.35 2679.21 2679.21 2679.21 2679.21 2679.21 2679.21
                 2677.21 2677.21 2677.21
BR Coef=-1 , 0 , 0 ,, 0 ,,,0.8,0,,0,
WSPro=,,,, 1 ,,,, 0 ,,,, 0 ,,,,-1 ,-1 ,-1 , 0 , 0 , 0 , 0 , 0
BC Design=,, 0 ,, 0 ,,,,,,

Type RM Length L Ch R = 1 ,129359  ,49.42,94.09,176.12
BEGIN DESCRIPTION:
129281
END DESCRIPTION:
XS GIS Cut Line= 6
  939288.6859661  809168.1420513  939246.9549067  809226.7904435
  939285.3031141  809330.5547956  939356.3583697  809375.6697313
  939491.7021525  809511.0135142  939586.4435175  809569.6619064
#Sta/Elev= 30
       0 2716.09   30.19    2698   42.07 2691.46    49.4 2685.97   71.31 2676.22
   99.09  2675.1  111.27 2673.69  122.36 2671.45  129.27    2672  145.16 2671.33
  147.01 2670.68  155.16 2668.17  159.01 2668.06  166.21 2666.31   185.3 2667.11
  199.28 2668.57  206.32 2668.03  212.83 2668.69   225.8 2671.08  231.72 2671.48
  238.12 2670.91  247.34 2672.35  306.53 2674.49  352.28 2678.24  385.46 2681.63
   404.7 2681.67  438.68 2683.14  522.67 2684.76  554.38 2688.62  573.39 2692.41
#Mann= 3 , 0 , 0
       0    .085       0  147.01     .05       0  199.28     .07       0
#XS Ineff= 2 , 0
       0  110.55    2675  230.55       0    2675
Permanent Ineff=
       F       F
Bank Sta=147.01,199.28
Exp/Cntr=0.5,0.3

Type RM Length L Ch R = 1 ,129265  ,196.16,330.23,437.49
BEGIN DESCRIPTION:
129186.9
END DESCRIPTION:
XS GIS Cut Line= 6
  939261.3640333  809148.2556335  939205.1572758  809199.9048096
  939180.8525644  809292.5701705   939218.828996  809417.1365535
  939271.9980487  809509.8008903  939313.0132094  809616.1379715
#Sta/Elev= 30
       0 2713.77   22.44 2702.34   37.83 2693.41   52.02 2685.64   73.52 2675.24
   99.42 2674.57  109.28 2672.89  138.05 2671.16  149.92 2668.76  159.71 2667.44
   173.1 2667.36  182.23 2667.77  188.052666.729  195.57 2665.33  208.86 2664.97
  217.21 2666.14  220.78 2666.91     228 2668.47  243.46 2669.46  272.29 2670.67
  292.31 2672.57  300.95 2672.83  319.98 2675.02  325.46    2676  341.99 2677.99
  363.93 2679.84  441.18 2682.51  475.02 2684.54  489.79 2684.32  525.17 2685.46
#Mann= 3 , 0 , 0
       0     .08       0  188.05     .05       0  220.78    .065       0
#Block Obstruct= 1 ,-1
  119.22  148.582685.703
Bank Sta=188.05,220.78
Exp/Cntr=0.3,0.1

Type RM Length L Ch R = 1 ,128935  ,257.55,276.73,402.57
BEGIN DESCRIPTION:
128856.6
END DESCRIPTION:
XS GIS Cut Line= 6
  939139.8363795   809005.460973  938951.4679527  809145.2179286
  938918.0480783  809180.1566554  938899.8187766  809221.1728403
  938881.5894749  809333.5853312  938836.0167327  809398.9072517
#Sta/Elev= 30
       0 2703.95   19.74 2698.59   48.94 2692.64   57.04 2690.44   67.94  2684.6
   92.56 2683.64  107.02 2674.32  108.93 2673.68     129 2673.35  134.22 2671.27
  141.81 2669.56   158.6 2668.36  230.95 2666.89  242.76  2662.2  248.142659.442
  253.51 2656.69  266.87 2657.51  277.98 2659.25     294 2662.74  355.72 2662.35
  388.77  2661.1  402.67 2662.19   428.1 2665.42  441.36 2667.77  451.06 2671.32
  454.92 2672.24  469.74 2678.68   493.1 2686.69  511.66 2691.59  523.11 2693.85
#Mann= 3 , 0 , 0
       0    .075       0  248.14     .05       0  277.98    .075       0
#Block Obstruct= 1 ,-1
  194.34   216.12678.009
Bank Sta=248.14,277.98
Exp/Cntr=0.5,0.3

Type RM Length L Ch R = 1 ,128658  ,80.84,61.21,50.77
BEGIN DESCRIPTION:
128579.9
END DESCRIPTION:
XS GIS Cut Line= 6
  938905.8952105  808888.4898764  938839.0554617   808921.910775
  938791.9628429  808940.1400767  938752.4665346  808961.4070833
  938717.5278078  808982.6740898  938667.3974842  809003.9421206
#Sta/Elev= 30
       0 2681.85   10.51 2679.94   14.82 2678.18   31.28 2673.68   37.68 2673.22
    41.4 2672.55   51.28 2672.48   59.21 2671.58   67.88 2668.96   75.15 2667.69
   81.31 2666.02   92.83 2663.53  121.65 2658.66  148.71  2655.6  159.88 2653.24
  163.92 2652.26  168.87 2651.44  174.88 2651.44   183.9 2653.08  201.66 2654.58
  217.61 2659.99  223.56 2664.81  227.67 2667.15  231.82  2670.3   239.7 2678.87
  244.79 2683.55  246.59 2684.92  247.93 2686.55  250.62 2688.91  265.44 2700.13
#Mann= 3 , 0 , 0
       0    .075       0  159.88     .05       0   183.9     .07       0
#XS Ineff= 2 , 0
       0  139.69 2662.44  193.69       0 2662.44
Permanent Ineff=
       F       F
#Block Obstruct= 1 ,-1
    62.5  118.562691.799
Bank Sta=159.88,183.9
Exp/Cntr=0.5,0.3

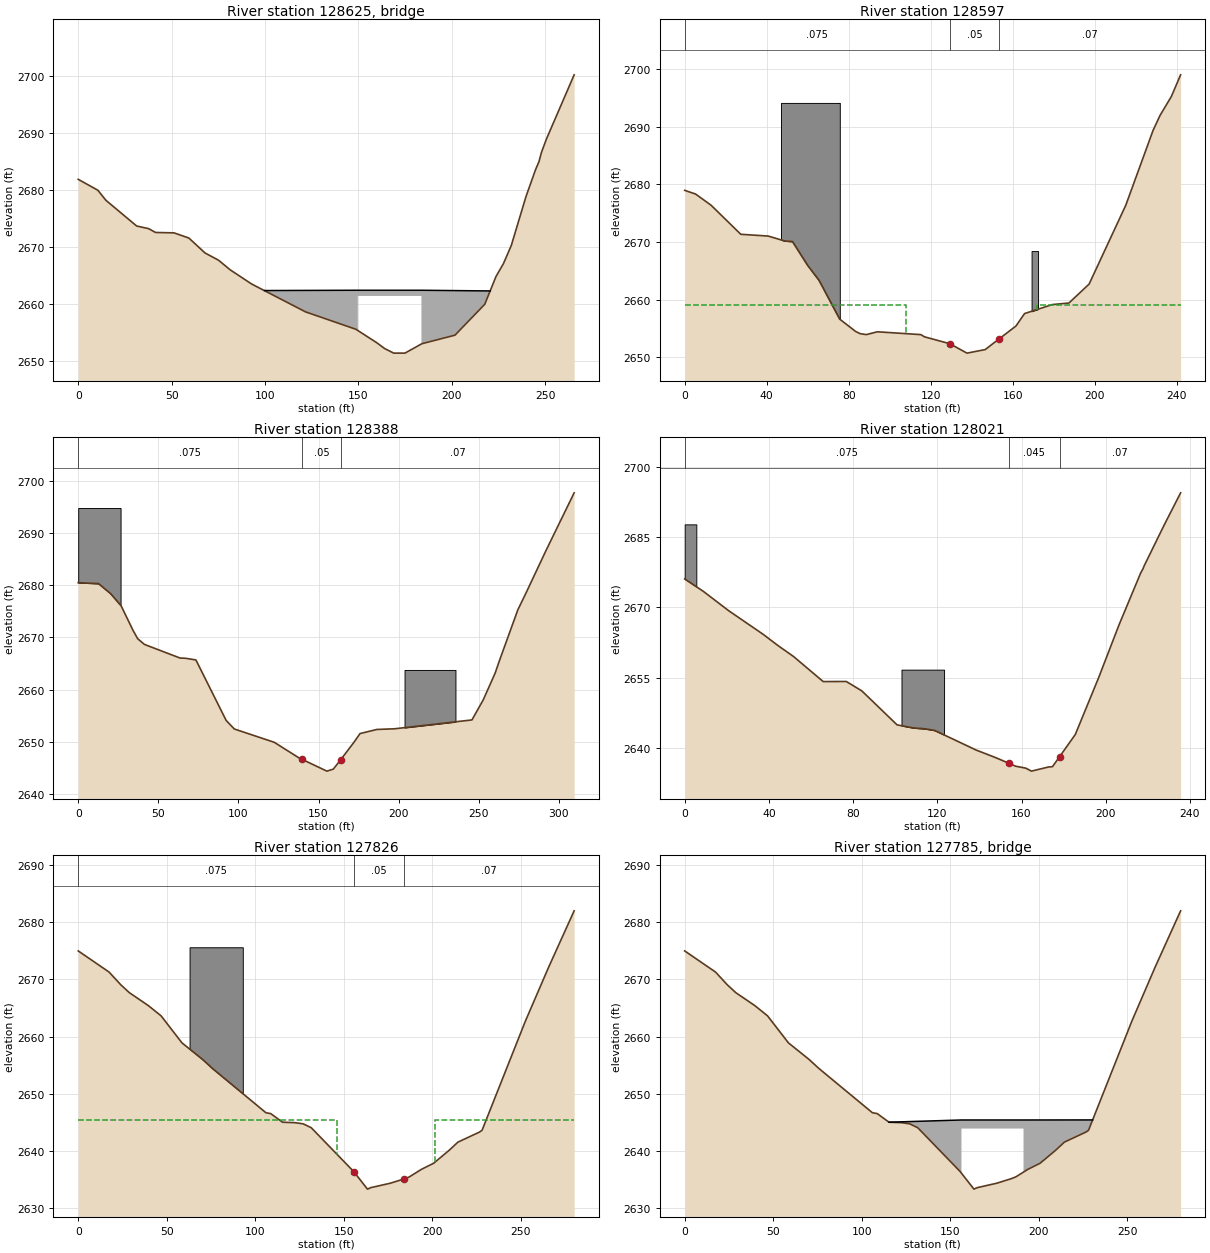
Type RM Length L Ch R = 3 ,128625  ,,,
Node Photo=H:\PROJ\06-0741\CE\GIS\DATA\FRENCH_BROAD_RIVER\SHAPEFILES\survey_data\photos\FBSTR_1776.JPG
BEGIN DESCRIPTION:
128543  FBSTR_1776
END DESCRIPTION:
Bridge Culvert--1,0,-1,-1, 0
Deck Dist Width WeirC Skew NumUp NumDn MinLoCord MaxHiCord MaxSubmerge Is_Ogee
30.5,12,2.6,0, 7, 7, , , 0.95, 0, 0,0,,
   99.72  149.69  149.69  166.69  183.69  183.69  220.49
 2662.39 2662.44 2662.44 2662.44 2662.44 2662.44 2662.32
                 2661.44 2661.44 2661.44
   66.88  122.88  122.88  139.88  156.88  156.88  196.56
 2662.41 2662.44 2662.44 2662.44 2662.44 2662.44 2662.45
                 2661.44 2661.44 2661.44
BR Coef=-1 , 0 , 0 ,, 0 ,,,0.8,0,,0,
WSPro=,,,, 1 ,,,, 0 ,,,, 0 ,,,,-1 ,-1 ,-1 , 0 , 0 , 0 , 0 , 0
BC Design=,, 0 ,, 0 ,,,,,,

Type RM Length L Ch R = 1 ,128597  ,220.5,208.09,172.51
BEGIN DESCRIPTION:
128518.7
END DESCRIPTION:
XS GIS Cut Line= 6
  938836.0167327  808824.6878325  938782.8487042  808870.2615989
   938737.275962  808900.6427442   938702.336211  808918.8720459
  938678.0304754  808937.1013477  938643.0917486  808969.0023696
#Sta/Elev= 30
       0 2678.94    5.31  2678.3   12.88 2676.36   27.36 2671.32   40.74 2671.01
    48.8 2670.16   52.55 2670.06   59.93 2665.94   65.49 2663.34   75.54 2656.63
   83.41 2654.46   85.47  2654.1   88.54 2653.92      94 2654.41  115.21 2653.92
  116.96 2653.54  129.34 2652.34  137.69 2650.71  146.56 2651.32  153.41 2653.19
  161.59 2655.41  165.78 2657.57  179.32 2659.13  187.42  2659.4  197.28 2662.69
  215.15 2676.35  228.48 2689.35  231.91 2691.96  237.39 2695.22   241.9 2698.97
#Mann= 3 , 0 , 0
       0    .075       0  129.34     .05       0  153.41     .07       0
#XS Ineff= 2 , 0
       0  107.88    2659  171.88       0    2659
Permanent Ineff=
       F       F
#Block Obstruct= 2 ,-1
   169.2  172.372668.405   46.99   75.66  2694.1
Bank Sta=129.34,153.41
Exp/Cntr=0.5,0.3

Type RM Length L Ch R = 1 ,128388  ,355.23,367.59,375
BEGIN DESCRIPTION:
128310.6
END DESCRIPTION:
XS GIS Cut Line= 6
  938717.5278078  808640.8769872  938629.4200283  808712.2753416
  938603.5954403  808738.0999296  938574.7321232  808770.0009516
   938526.120652  808850.5124206  938518.5253656  808871.7804513
#Sta/Elev= 30
       0 2680.52   12.65 2680.34    20.2 2678.42   26.85 2676.04   34.22 2671.36
   37.13 2669.76   41.34 2668.66   63.52 2666.05      67    2666   73.48 2665.68
   92.36 2654.06   97.44 2652.42  122.35 2649.87  137.77 2646.88  139.75 2646.59
  155.22 2644.33  159.23 2644.71  163.93 2646.55  172.13 2649.87  175.91 2651.54
   186.4 2652.33  197.48 2652.46  245.79 2654.16  252.85 2658.02  260.28 2663.16
   262.8 2665.41  274.42 2675.29  279.73 2678.66  292.02 2686.69  309.59 2697.77
#Mann= 3 , 0 , 0
       0    .075       0  139.75     .05       0  163.93     .07       0
#Block Obstruct= 2 ,-1
  203.71   235.52663.762       0   26.442694.857
Bank Sta=139.75,163.93
Exp/Cntr=0.3,0.1

Type RM Length L Ch R = 1 ,128021  ,193.98,195.39,177.94
BEGIN DESCRIPTION:
127943.0
END DESCRIPTION:
XS GIS Cut Line= 6
  938427.3798813  808460.1048709  938368.1354189  808508.7163421
   938327.119234   808537.578635  938305.8522274  808552.7702319
  938276.9889103  808574.0372384  938239.0114545  808601.3806789
#Sta/Elev= 30
       0 2676.08    8.85 2673.43   20.87 2669.31   37.14 2664.31   44.47 2661.82
   51.67 2659.55    65.8 2654.19   76.76 2654.21   84.14 2652.21  100.89 2644.96
  108.69 2644.31  114.18 2644.12  118.72 2643.78  138.41  2639.6  147.88 2637.95
  154.04 2636.76   157.2 2636.15     162 2635.74  164.72  2635.1  172.89 2635.99
  174.68 2636.04  178.05 2638.16  185.57 2642.93  196.62 2655.01  206.36 2666.33
  216.65 2677.39  217.68 2678.21  218.37 2678.97  227.73 2687.54  235.57 2694.43
#Mann= 3 , 0 , 0
       0    .075       0  154.04    .045       0  178.05     .07       0
#Block Obstruct= 2 ,-1
  102.98  123.212656.735       0    5.542687.707
Bank Sta=154.04,178.05
Exp/Cntr=0.5,0.3

Type RM Length L Ch R = 1 ,127826  ,83.91,63.89,50.28
BEGIN DESCRIPTION:
127747.6
END DESCRIPTION:
XS GIS Cut Line= 6
  938342.3108308  808344.6536509  938270.9124764  808356.8065187
  938231.4161681  808368.9593865  938196.4774413  808388.7075407
  938152.4235516  808434.2802829  938122.0413821   808488.968188
#Sta/Elev= 30
       0    2675   17.46 2671.29   24.01 2669.08   28.87 2667.69   39.66 2665.41
   46.79 2663.63   58.61 2658.89   70.17 2656.01   75.84  2654.4  106.01 2646.66
  108.71 2646.51   115.4    2645  122.38 2644.92  127.08 2644.71  131.62 2644.03
   155.6 2636.35  163.36 2633.28  165.22 2633.54  176.19 2634.31  184.15 2635.08
  186.99 2635.42   193.8 2636.74  200.76 2637.82  209.51 2640.09  214.43 2641.51
  226.67 2643.28  228.07 2643.59  252.57 2662.73  265.55 2672.07  280.07 2682.02
#Mann= 3 , 0 , 0
       0    .075       0   155.6     .05       0  184.15     .07       0
#XS Ineff= 2 , 0
       0  146.33 2645.39  201.33       0 2645.39
Permanent Ineff=
       F       F
#Block Obstruct= 1 ,-1
   62.88   92.942675.638
Bank Sta=155.6,184.15
Exp/Cntr=0.5,0.3

Type RM Length L Ch R = 3 ,127785  ,,,
Node Photo=H:\PROJ\06-0741\CE\GIS\DATA\FRENCH_BROAD_RIVER\SHAPEFILES\survey_data\photos\FBSTR_1268A.JPG
BEGIN DESCRIPTION:
127709.8  FBSTR_1268A
END DESCRIPTION:
Bridge Culvert--1,0,-1,-1, 0
Deck Dist Width WeirC Skew NumUp NumDn MinLoCord MaxHiCord MaxSubmerge Is_Ogee
31,12,2.6,0, 7, 7, , , 0.95, 0, 1,1,,
   115.4  156.33  156.33  173.33  191.33  191.33  230.37
    2645 2645.39 2645.39 2645.39 2645.39 2645.39  2645.4
                 2643.89 2643.89 2643.89
   90.95  184.81  184.81  201.81  219.81  219.81  258.89
 2645.27 2645.39 2645.39 2645.39 2645.39 2645.39 2645.38
                 2643.89 2643.89 2643.89
BR Coef=-1 , 0 , 0 ,, 0 ,,,0.8,0,,0,
WSPro=,,,, 1 ,,,, 0 ,,,, 0 ,,,,-1 ,-1 ,-1 , 0 , 0 , 0 , 0 , 0
BC Design=,, 0 ,, 0 ,,,,,,

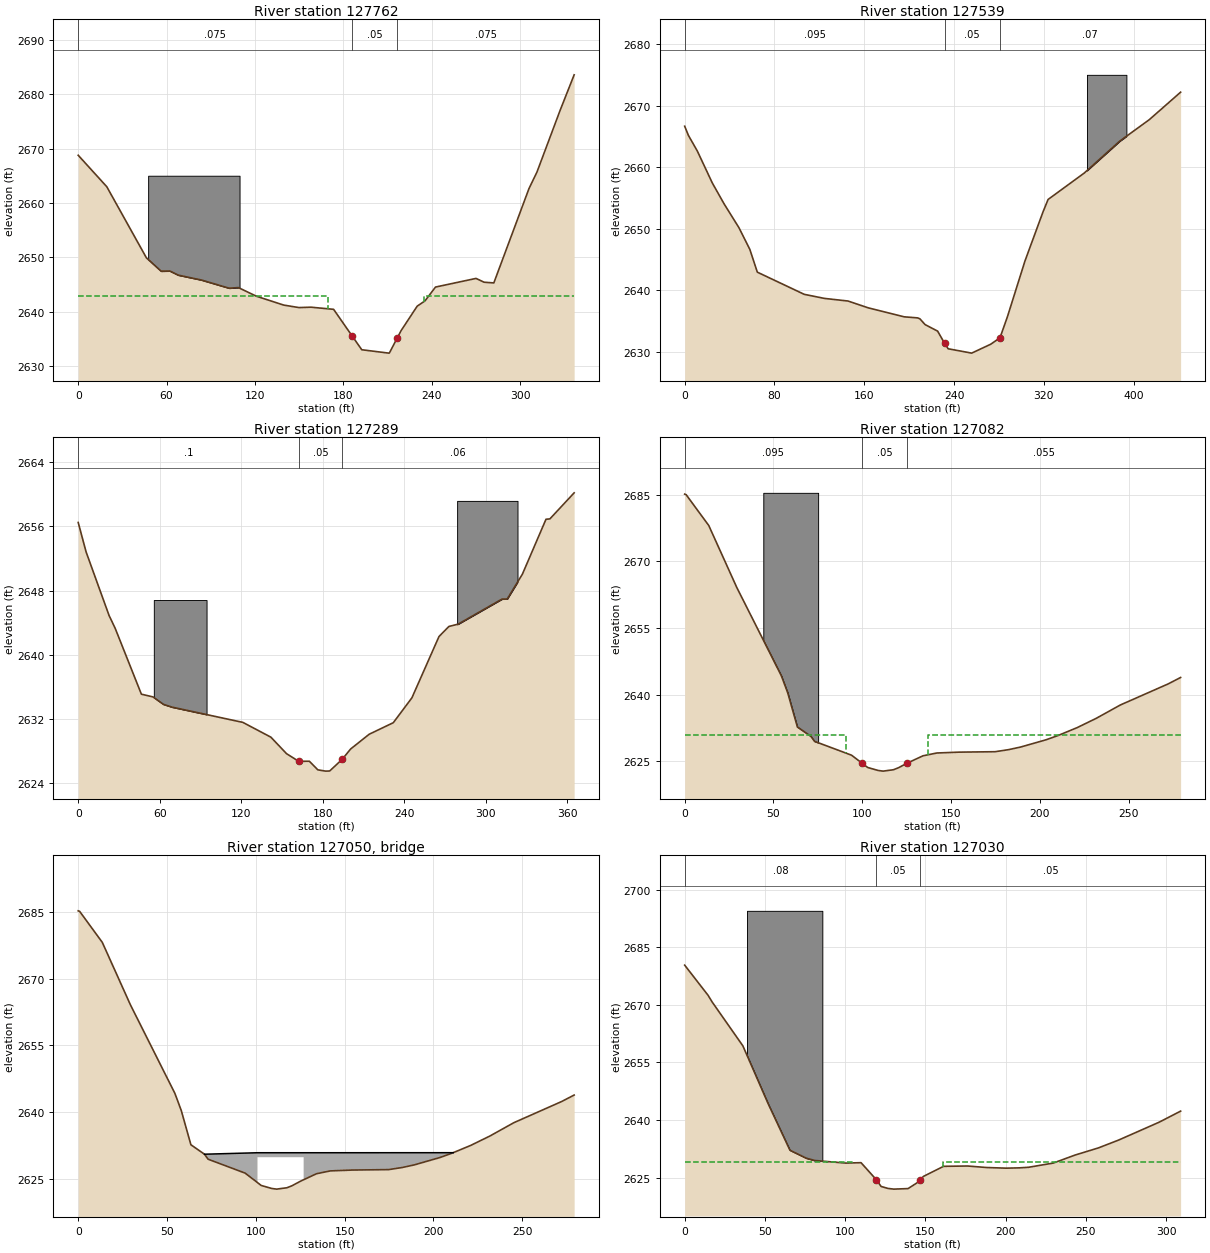
Type RM Length L Ch R = 1 ,127762  ,180.5,222.92,253.74
BEGIN DESCRIPTION:
127683.7
END DESCRIPTION:
XS GIS Cut Line= 6
  938318.0050952  808294.5233273  938263.3171901  808279.3327546
  938223.8208818  808283.8893119  938187.3622784  808306.6761951
   938119.002653  808375.0358204  938084.0639262  808469.2190097
#Sta/Elev= 30
       0 2668.78    19.4    2663   46.36 2649.91   56.32 2647.47    62.2 2647.51
   67.92 2646.75   83.68 2645.85  102.47 2644.35  108.81 2644.46  120.85 2642.89
  139.51 2641.25  149.88 2640.79   158.1 2640.86  173.41 2640.47  186.032635.559
  192.54 2633.04  210.87 2632.42  211.28 2632.44  216.562635.176  219.24 2636.55
  230.17 2641.05   235.5 2642.03   242.6 2644.56  270.12 2646.15  275.61 2645.45
  282.21 2645.32   306.1 2662.67  311.48 2665.68  327.19 2677.01  336.75 2683.56
#Mann= 3 , 0 , 0
       0    .075       0  186.03     .05       0  216.56    .075       0
#XS Ineff= 2 , 0
       0  169.81    2643  234.81       0    2643
Permanent Ineff=
       F       F
#Block Obstruct= 1 ,-1
   47.48  109.552665.022
Bank Sta=186.03,216.56
Exp/Cntr=0.5,0.3

Type RM Length L Ch R = 1 ,127539  ,222.17,249.41,274.96
BEGIN DESCRIPTION:
127460.8
END DESCRIPTION:
XS GIS Cut Line= 6
  938245.0878884  808075.7737551  938193.4387123  808107.6747771
  938067.3534769  808138.0559224  938030.8958977  808156.2852241
   937951.902257  808224.6448495  937895.6954994  808314.2714814
#Sta/Elev= 30
       0 2666.67    3.37 2665.17   11.26 2662.65   24.56 2657.48   35.04 2654.09
   48.39 2650.18   58.08 2646.66   64.74 2642.97  106.52 2639.37  124.44 2638.71
  145.57 2638.28  163.66 2637.17  195.47 2635.72  207.67 2635.54  209.68 2635.38
  214.19 2634.46  225.42 2633.39   231.6 2631.42  234.78 2630.53  255.75 2629.82
  272.66 2631.26  280.98 2632.31  287.57 2635.71  303.23 2644.78  319.24 2652.72
  323.86 2654.78  356.08 2659.07  387.75 2664.26  413.91 2667.72  441.94  2672.2
#Mann= 3 , 0 , 0
       0    .095       0   231.6     .05       0  280.98     .07       0
#Block Obstruct= 1 ,-1
  358.47  393.622675.019
Bank Sta=231.6,280.98
Exp/Cntr=0.3,0.1

Type RM Length L Ch R = 1 ,127289  ,276.47,207.89,158.18
BEGIN DESCRIPTION:
127211.4
END DESCRIPTION:
XS GIS Cut Line= 6
  938052.1629043  807920.8252027  937986.8420079  807972.4743788
  937957.9786909  807975.5131078  937892.6577945  807951.2073722
  937844.0463233  807964.8790924  937745.3055526  808051.4680195
#Sta/Elev= 30
       0 2656.48    5.81 2652.81   22.72  2644.9   27.23  2643.3   46.52  2635.1
   55.09 2634.76   62.77 2633.83   69.27 2633.48  121.23 2631.59  141.87 2629.75
  153.43 2627.69  162.37 2626.74  170.22 2626.75  176.46 2625.68  182.21 2625.52
   185.2 2625.54  194.46    2627  200.57 2628.27  214.25 2630.11  232.02 2631.55
  245.74 2634.65  265.68 2642.28  272.94 2643.53  279.75 2643.82  312.06 2646.94
  315.91 2646.95  327.08 2650.04  344.47 2656.88  347.37 2656.93   365.2 2660.17
#Mann= 3 , 0 , 0
       0      .1       0  162.37     .05       0  194.46     .06       0
#Block Obstruct= 2 ,-1
  279.02  323.492659.167   55.67   94.512646.821
Bank Sta=162.37,194.46
Exp/Cntr=0.5,0.3

Type RM Length L Ch R = 1 ,127082  ,47.09,51.92,43.39
BEGIN DESCRIPTION:
127003.5
END DESCRIPTION:
XS GIS Cut Line= 6
  937891.1389421  807740.0530864  937837.9698894  807749.1672251
   937801.511286  807762.8389454  937772.6489931  807782.5870995
  937724.0375219  807831.1985707  937683.0223612   807902.595901
#Sta/Elev= 30
       0 2685.16     .81 2685.04   13.56  2678.1   29.37 2664.13   54.43 2644.28
   58.01 2640.46   63.45 2632.77    71.1 2630.65   73.12 2629.53   93.94 2626.42
   99.842624.632  103.04 2623.65  108.94 2622.98   111.7 2622.83  117.53 2623.14
  120.33 2623.58  125.29 2624.63   134.2 2626.28  141.98 2626.91  154.39  2627.1
  174.83  2627.2  182.32 2627.66  189.16 2628.25  203.55 2629.89  210.15 2630.83
     221 2632.62  231.74 2634.71  245.29 2637.71  272.15 2642.44  279.24  2643.9
#Mann= 3 , 0 , 0
       0    .095       0   99.84     .05       0  125.29    .055       0
#XS Ineff= 2 , 0
       0   90.94 2630.98  136.94       0 2630.98
Permanent Ineff=
       F       F
#Block Obstruct= 1 ,-1
   44.26   75.142685.451
Bank Sta=99.84,125.29
Exp/Cntr=0.5,0.3

Type RM Length L Ch R = 3 ,127050  ,,,
Node Photo=H:\PROJ\06-0741\CE\GIS\DATA\FRENCH_BROAD_RIVER\SHAPEFILES\survey_data\photos\FBSTR_1775.JPG
BEGIN DESCRIPTION:
126971.6  FBSTR_1775
END DESCRIPTION:
Bridge Culvert--1,0,-1,-1, 0
Deck Dist Width WeirC Skew NumUp NumDn MinLoCord MaxHiCord MaxSubmerge Is_Ogee
25,12,2.6,0, 7, 7, , , 0.95, 0, 1,1,,
    71.1  100.94  100.94  113.94  126.94  126.94  211.15
 2630.65 2630.98 2630.98 2630.98 2630.98 2630.98 2630.99
                 2629.98 2629.98 2629.98
   75.69  119.66  119.66  132.66  145.66  145.66  244.06
 2630.08 2630.98 2630.98 2630.98 2630.98 2630.98 2630.98
                 2629.98 2629.98 2629.98
BR Coef=-1 , 0 , 0 ,, 0 ,,,0.8,0,,0,
WSPro=,,,, 1 ,,,, 0 ,,,, 0 ,,,,-1 ,-1 ,-1 , 0 , 0 , 0 , 0 , 0
BC Design=,, 0 ,, 0 ,,,,,,

Type RM Length L Ch R = 1 ,127030  ,171.8,178.83,202.06
BEGIN DESCRIPTION:
126951.6
END DESCRIPTION:
XS GIS Cut Line= 6
  937882.0237792  807709.6709169  937819.7405877  807706.6321878
  937792.3971472  807708.1520644  937739.2291187  807741.5719388
  937716.4422355  807770.4352559  937651.1213392   807870.694879
#Sta/Elev= 30
       0 2680.34   14.55  2672.5   17.16 2670.72   36.25 2659.33   51.99 2644.26
   65.58 2632.14   75.69 2630.08   80.95 2629.47  100.37 2628.79  109.87  2628.9
  119.44 2624.45  122.36 2622.71  126.55  2622.2  130.24 2622.01  139.18 2622.15
  144.54 2623.59   146.7 2624.48  148.78 2625.33  161.31 2627.95   176.3 2628.03
  188.02 2627.64  200.31 2627.47  208.61 2627.55  214.26  2627.7   229.7  2628.8
  243.12 2630.87  257.74 2632.74  270.38 2634.79  295.55 2639.43  308.98 2642.32
#Mann= 3 , 0 , 0
       0     .08       0  119.44     .05       0   146.7     .05       0
#XS Ineff= 2 , 0
       0  104.99    2629  160.66       0    2629
Permanent Ineff=
       F       F
#Block Obstruct= 1 ,-1
   38.83   85.762694.486
Bank Sta=119.44,146.7
Exp/Cntr=0.5,0.3

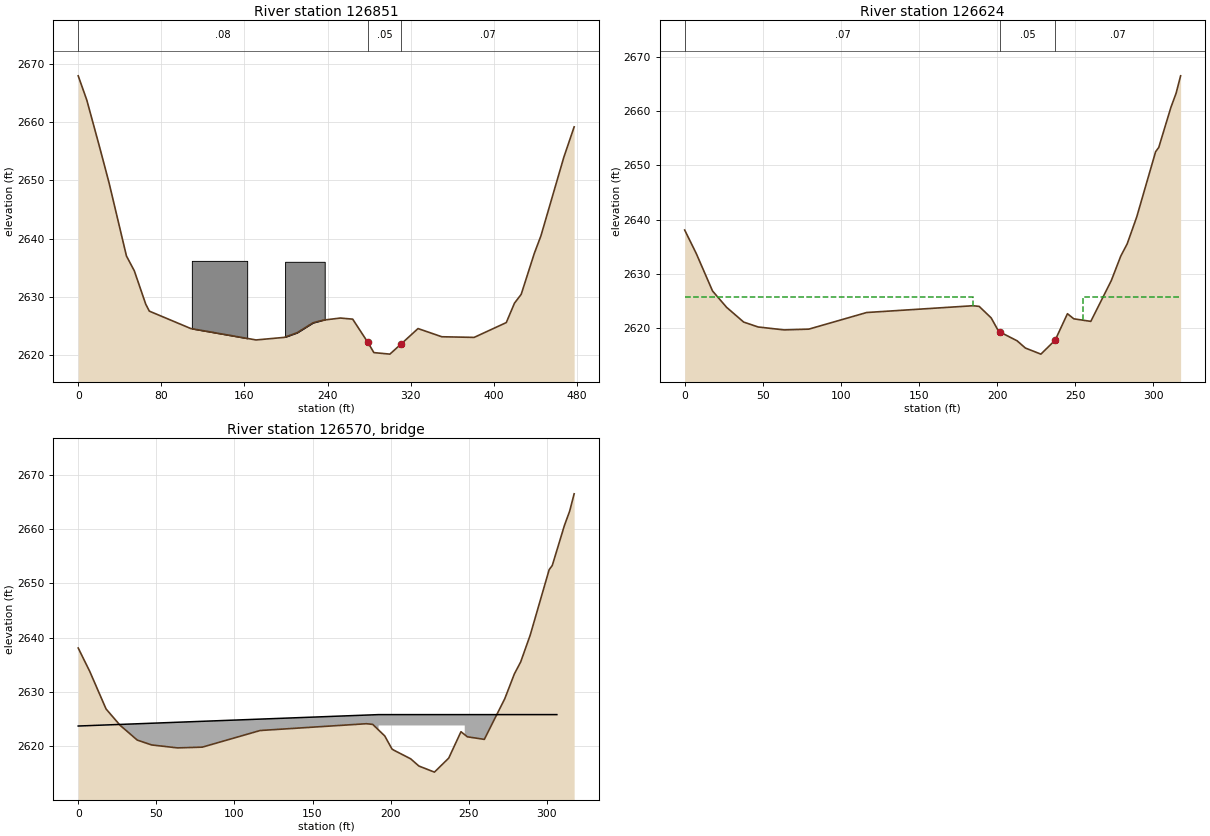
Type RM Length L Ch R = 1 ,126851  ,145.26,226.54,333.47
BEGIN DESCRIPTION:
126772.8
END DESCRIPTION:
XS GIS Cut Line= 6
  937898.7342284  807569.9139613  937775.6866979  807550.1658071
  937719.4809646  807551.6846596  937673.9071982  807565.3563798
  937576.6852799  807664.0981747  937479.4633617  807714.2284983
#Sta/Elev= 30
       0 2668.01    8.26 2663.84   20.82 2655.59   29.68  2649.6   46.43    2637
   53.99 2634.45   64.97 2628.72   68.44 2627.51  108.28 2624.52  171.17 2622.55
  198.28 2622.99  210.65 2623.79  225.96  2625.5  235.35 2625.95  252.27 2626.32
  264.17 2626.13  278.682622.147  284.57 2620.37  299.97 2620.11  310.74 2621.85
  327.05 2624.51  349.93  2623.1  381.05 2622.99  411.97 2625.54  419.89 2628.89
  426.31 2630.39  438.94 2637.44  445.34 2640.48   467.4 2654.02   477.3 2659.22
#Mann= 3 , 0 , 0
       0     .08       0  278.68     .05       0  310.74     .07       0
#Block Obstruct= 2 ,-1
   199.1  237.23    2636  109.37  162.612636.159
Bank Sta=278.68,310.74
Exp/Cntr=0.5,0.3

Type RM Length L Ch R = 1 ,126624  ,67.19,106.26,94.74
BEGIN DESCRIPTION:
126546.2
END DESCRIPTION:
XS GIS Cut Line= 6
  937735.0443372  807365.6482806   937637.449619  807452.9438889
  937578.2041324  807466.6156091  937509.8455312  807455.9815937
  937462.7529124  807378.5078296  937405.0273024  807373.9502481
#Sta/Elev= 30
       0 2638.08   7.415 2633.76  17.826 2626.86  26.858 2623.84  37.781 2621.13
   47.02 2620.23  63.666 2619.69  79.454 2619.83 116.469 2622.89 184.548 2624.14
 188.516 2624.02 196.207  2621.9 200.872 2619.48 202.105 2619.26 212.822 2617.68
 218.108 2616.35 228.028 2615.23 237.183 2617.81 245.027 2622.67 249.125 2621.73
  259.98 2621.26 273.064 2628.75  279.17 2633.29  283.26 2635.53 289.366 2640.48
 301.469  2652.5 303.469 2653.28 311.244 2660.65 314.576 2663.26 317.472 2666.47
#Mann= 3 , 0 , 0
       0     .07       0 202.105     .05       0 237.183     .07       0
#XS Ineff= 2 , 0
       0 184.617 2625.82 255.093       0 2625.82
Permanent Ineff=
       F       F
Bank Sta=202.105,237.183
Skew Angle= 40
Exp/Cntr=0.5,0.3

Type RM Length L Ch R = 3 ,126570  ,,,
BEGIN DESCRIPTION:
126490  FBSTR_1261
END DESCRIPTION:
Bridge Culvert--1,0,-1,-1, 0
Deck Dist Width WeirC Skew NumUp NumDn MinLoCord MaxHiCord MaxSubmerge Is_Ogee
23,56,2.6,40, 7, 7, , , 0.95, 0, 1,1,,
       0 192.277 192.277 214.492 247.432 247.432 306.418
 2623.72 2625.82 2625.82 2625.82 2625.82 2625.82 2625.82
                 2623.82 2623.82 2623.82
       0 163.681 163.681 191.258 218.836 218.836     300
 2623.72 2625.82 2625.82 2625.82 2625.82 2625.82 2625.82
                 2623.82 2623.82 2623.82
BR Coef=-1 , 0 , 0 ,, 0 ,,,0.8,0,,0,
WSPro=,,,, 1 ,,,, 0 ,,,, 0 ,,,,-1 ,-1 ,-1 , 0 , 0 , 0 , 0 , 0
BC Design=,, 0 ,, 0 ,,,,,,