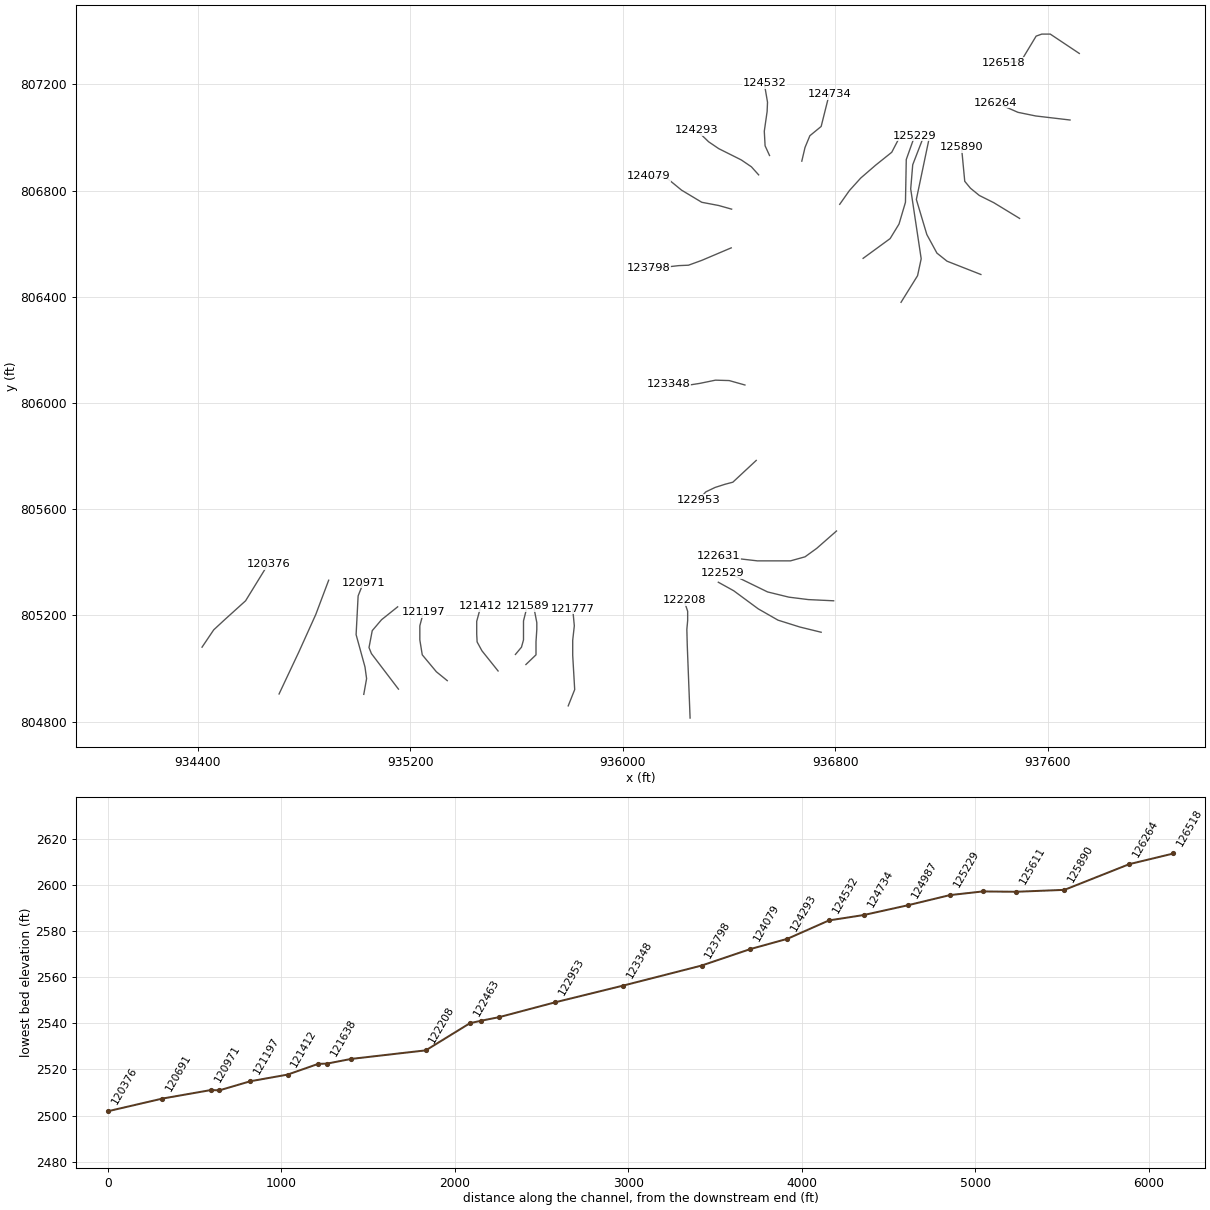
HEC-RAS study lds_big_laurel_crk.prj: lds_big_laurel_crk

--- lds_big_laurel_crk.g20 (geometry) --- (continued)

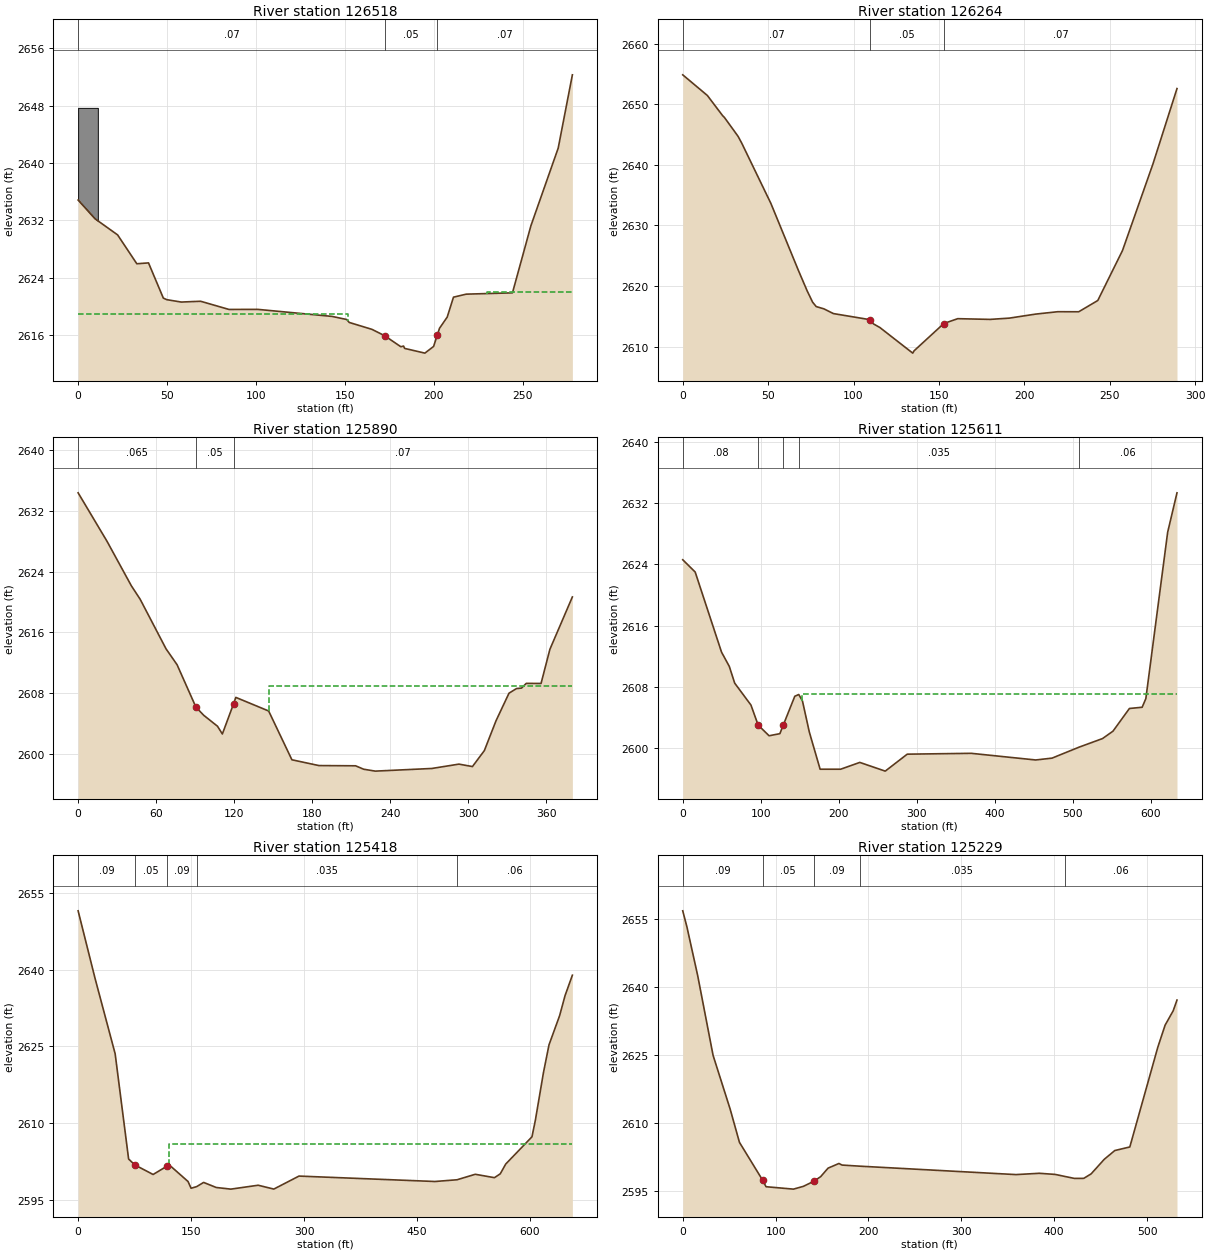
Type RM Length L Ch R = 1 ,126518  ,295.89,254.4,171.06
BEGIN DESCRIPTION:
126440.0
END DESCRIPTION:
XS GIS Cut Line= 6
  937719.4809646  807316.2246381  937610.1051543   807389.141845
  937578.2041324   807389.141845  937556.9371258  807381.5455345
  937499.2115158  807285.8424686  937435.4094719  807281.2859113
#Sta/Elev= 30
       0 2634.84   9.468 2632.24  22.192 2629.99  32.994 2625.97  39.566 2626.09
  47.901 2621.19  49.847 2620.97  57.974 2620.64  68.875 2620.75  84.793 2619.61
 101.026 2619.62  142.76 2618.64  150.98 2618.21 152.405  2617.8 165.167 2616.84
  172.26 2615.96 181.415 2614.42 182.962 2614.51 183.514 2614.19  194.92 2613.53
 199.823 2614.46 201.9682616.092 203.147 2616.99 207.483 2618.55 210.999 2621.32
 218.185 2621.74 244.154 2621.92 254.534 2631.27  269.87 2642.07 277.837 2652.27
#Mann= 3 , 0 , 0
       0     .07       0  172.26     .05       0 201.968     .07       0
#XS Ineff= 2 , 0
       0 151.677    2619 229.813       0    2622
Permanent Ineff=
       F       F
#Block Obstruct= 1 ,-1
       0  11.0772647.673
Bank Sta=172.26,201.968
Skew Angle= 40
Exp/Cntr=0.5,0.3

Type RM Length L Ch R = 1 ,126264  ,398.15,373.71,331.8
BEGIN DESCRIPTION:
126185.6
END DESCRIPTION:
XS GIS Cut Line= 4
  937684.5412136   807065.574044  937555.4182734  807080.7646167
  937488.5775004   807094.436337  937405.0273024  807130.8949404
#Sta/Elev= 30
       0 2654.88   14.42 2651.47   23.35 2648.14   24.44 2647.83   32.38 2644.73
   34.56 2643.59   51.62 2633.64   67.71 2622.59   72.91 2619.17   76.04 2617.34
   78.14 2616.61   82.67 2616.23   88.22 2615.45  108.25 2614.51  109.74 2614.31
  111.61 2613.76  115.43 2613.15  134.67 2608.92  135.45  2609.3  152.86 2613.81
  161.03 2614.61  179.95 2614.49   191.2  2614.7  206.77 2615.37  219.63 2615.76
  231.86 2615.75  243.02 2617.61  257.49 2625.86  275.32 2640.16   289.4 2652.61
#Mann= 3 , 0 , 0
       0     .07       0  109.74     .05       0  152.86     .07       0
Bank Sta=109.74,152.86
Exp/Cntr=0.3,0.1

Type RM Length L Ch R = 1 ,125890  ,269.52,279.11,179.3
BEGIN DESCRIPTION:
125811.9
END DESCRIPTION:
XS GIS Cut Line= 6
  937494.6539343  806694.9136243  937397.4320161  806754.1591109
  937342.7441109  806781.5025514  937309.3242366  806808.8459919
    937288.05723  806834.6705799  937275.9043622  806962.2746677
#Sta/Elev= 30
       0 2634.35   22.25 2627.97   40.97 2622.12   47.68 2620.37   67.59 2613.85
   76.08 2611.76   90.59 2606.18   96.62 2605.11  107.14 2603.68  110.89 2602.66
  119.51 2606.63  121.24 2607.47  146.49 2605.68  164.36 2599.27  185.12 2598.51
  213.31 2598.48  219.54 2598.03  228.46 2597.78  271.98 2598.13  292.77  2598.7
  303.16 2598.38  312.32 2600.48  321.29  2604.4  331.26 2608.02  337.03 2608.63
  340.87 2608.69  344.55 2609.31   355.9  2609.3  362.69 2613.78  379.99 2620.67
#Mann= 3 , 0 , 0
       0    .065       0   90.59     .05       0  119.51     .07       0
#XS Ineff= 2 , 0
       0                  146.49       0    2609
Permanent Ineff=
       F       F
Bank Sta=90.59,119.51
Exp/Cntr=0.3,0.1

Type RM Length L Ch R = 1 ,125611  ,287.58,192.33,37.64
BEGIN DESCRIPTION:
125532.8
END DESCRIPTION:
XS GIS Cut Line= 6
  937348.8205448  806483.7593385  937221.2164571  806533.8896622
  937183.2390012  806564.2718317  937145.2615454  806634.1503095
  937105.7652371  806766.3119787  937152.8568317  806991.1379848
#Sta/Elev= 30
       0 2624.62   15.97 2623.01   49.73 2612.53    59.7 2610.66   66.61 2608.47
   87.47  2605.6   96.67 2602.98  110.67 2601.58  124.52 2601.85  128.922602.979
  143.68 2606.75  148.77 2606.98  153.51 2606.13   162.3 2602.07  176.15  2597.2
  202.46  2597.2  227.02 2598.09  259.64 2596.95  287.86 2599.17  369.94 2599.28
  452.52 2598.41  473.47 2598.65  508.48  2600.1   538.2 2601.21  551.64 2602.18
  572.73 2605.15  589.05 2605.31  593.79 2606.44  621.76 2628.22  633.72 2633.38
#Mann= 5 ,-1 , 0
       0     .08       0   96.67     .05       0  128.92     .09       0
  148.77    .035       0  508.48     .06       0
#XS Ineff= 2 , 0
       0                   153.5       0    2607
Permanent Ineff=
       F       F
Bank Sta=96.67,128.92
Exp/Cntr=0.3,0.1

Type RM Length L Ch R = 1 ,125418  ,206.83,189.28,25.41
BEGIN DESCRIPTION:
125340.4
END DESCRIPTION:
XS GIS Cut Line= 6
  937048.0396271  806378.9421339  937110.3228186   806479.201757
  937123.9945388  806543.0038009  937084.4982305   806805.808287
  937092.0935168  806896.9537714  937133.1086776  807003.2908526
#Sta/Elev= 30
       0 2651.47   22.44 2638.29   49.17 2623.54   67.04 2602.98   75.28 2601.82
    99.6 2599.95  118.33 2601.61  120.47 2601.89  145.97 2598.58  149.99 2597.26
  157.42 2597.58  166.66  2598.4  183.37 2597.41   202.8 2597.09  239.08 2597.85
  259.88  2597.1  293.31 2599.64  473.88 2598.58  503.23 2598.92  527.35 2599.99
  552.84 2599.33  560.58 2600.08  567.78 2601.98  602.69 2607.31  607.23 2610.57
  617.96 2619.87  625.32 2625.28   639.4 2630.98  646.65 2634.91  656.36 2638.89
#Mann= 5 ,-1 , 0
       0     .09       0   75.28     .05       0  118.33     .09       0
  157.42    .035       0  503.23     .06       0
#XS Ineff= 2 , 0
       0                  120.47       0    2606
Permanent Ineff=
       F       F
Bank Sta=75.28,118.33
Exp/Cntr=0.3,0.1

Type RM Length L Ch R = 1 ,125229  ,226.72,242.27,94.6
BEGIN DESCRIPTION:
125151.2
END DESCRIPTION:
XS GIS Cut Line= 6
  936905.2439425  806544.5236775  937007.0234422  806618.9587126
  937040.4443408  806673.6466177  937064.7500764  806755.6779634
  937067.7877812  806916.7019255  937099.6888032  807006.3285574
#Sta/Elev= 30
       0 2656.81    4.49 2653.29   16.16 2642.48   32.67 2624.97   51.11 2613.09
   61.06 2605.81   85.89 2597.51   89.68 2596.03  119.21  2595.5     130 2596.12
   141.2 2597.24  148.47 2598.24  156.45 2600.12  168.17 2601.15  171.57  2600.8
  190.41 2600.56  358.91  2598.7  383.98 2598.99  401.01 2598.74  411.07 2598.31
  421.66 2597.86  431.76 2597.87  439.71 2598.86  453.85 2602.07   465.2    2604
  481.37 2604.79  511.52 2626.77  519.38 2631.63  528.07 2634.79  532.16 2637.15
#Mann= 5 ,-1 , 0
       0     .09       0   85.89     .05       0   141.2     .09       0
  190.41    .035       0  411.07     .06       0
Bank Sta=85.89,141.2
Exp/Cntr=0.3,0.1

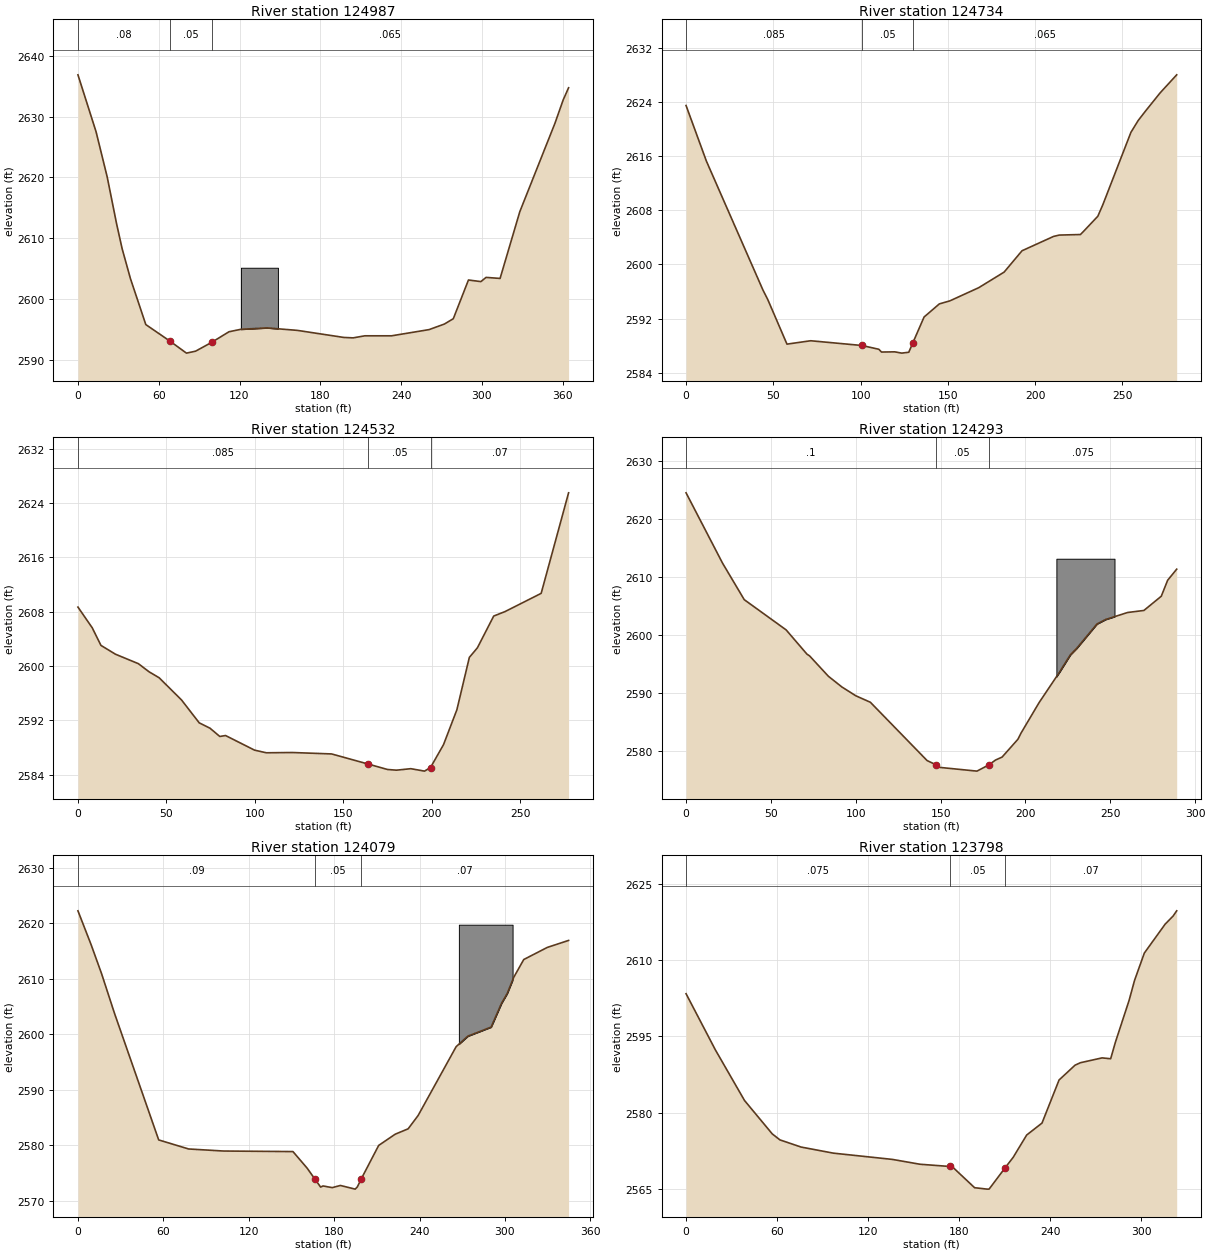
Type RM Length L Ch R = 1 ,124987  ,239.27,253.03,291.95
BEGIN DESCRIPTION:
124908.9
END DESCRIPTION:
XS GIS Cut Line= 6
  936817.1371871   806748.082677  936853.5947664  806799.7318531
  936896.1298037  806846.8234477  936952.3365613  806895.4349189
  937013.0998761  806944.0463902  937052.5972086  807020.0002777
#Sta/Elev= 30
       0 2636.89   13.49  2627.5    21.7 2620.11   28.73 2612.35   32.83 2608.27
   38.96 2603.38   50.39  2595.8   68.24 2593.09   80.59  2591.1   87.38 2591.42
   99.31 2592.87  112.21 2594.62  121.07 2595.02  140.58 2595.25  163.04 2594.84
  197.51 2593.68  204.37 2593.61  213.16 2593.95  232.97 2593.95  260.81 2594.97
  272.13 2595.88  278.79 2596.76  290.04 2603.13  299.28 2602.87  303.14 2603.56
  313.53 2603.39   328.2 2614.38  354.31 2628.93   360.4 2632.76  364.41 2634.76
#Mann= 3 , 0 , 0
       0     .08       0   68.24     .05       0   99.31    .065       0
#Block Obstruct= 1 ,-1
  121.06  148.532605.152
Bank Sta=68.24,99.31
Exp/Cntr=0.3,0.1

Type RM Length L Ch R = 1 ,124734  ,153.11,201.72,232.6
BEGIN DESCRIPTION:
124655.9
END DESCRIPTION:
XS GIS Cut Line= 5
  936674.3415025  806910.6254916  936686.4943703  806962.2746677
   936704.723672  807006.3285574  936747.2587093  807041.2683084
  936777.6398547  807162.7959623
#Sta/Elev= 30
       0 2623.51   11.66 2615.28   44.08  2596.2    46.8 2594.82    57.8 2588.22
   71.39 2588.72  100.74 2588.02  110.42 2587.46  111.94 2587.05  119.52 2587.08
  123.55 2586.89  127.58 2587.02  129.99 2588.46  136.34 2592.23  145.09 2594.17
  151.13 2594.62  167.67 2596.57  182.18 2598.87  192.45 2602.03  210.53 2604.15
  213.82 2604.35  225.91 2604.43  227.56 2604.86  235.89 2607.14  238.79 2608.87
  254.84 2619.55  258.98 2621.29  262.97 2622.62  271.59 2625.39  281.05 2628.05
#Mann= 3 , 0 , 0
       0    .085       0  100.74     .05       0  129.99    .065       0
Bank Sta=100.74,129.99
Exp/Cntr=0.3,0.1

Type RM Length L Ch R = 1 ,124532  ,101.61,239.47,298.34
BEGIN DESCRIPTION:
124454.1
END DESCRIPTION:
XS GIS Cut Line= 6
  936552.8138486  806931.8935224  936536.1033994  806968.3511016
  936533.0656945  807023.0390067  936543.6997099   807097.475066
  936545.2185623  807132.4137928  936533.0656945   807203.811123
#Sta/Elev= 30
       0 2608.68    8.08 2605.63   13.01 2603.04   21.23 2601.74   34.17 2600.35
   40.24 2599.15   45.94 2598.27   58.57 2595.01   68.58 2591.64   74.68 2590.85
   80.23 2589.63   83.47 2589.77   99.87 2587.62  106.53 2587.23  121.26 2587.27
  143.45 2587.06   164.32585.559  175.09 2584.77  180.18 2584.67  188.24 2584.89
     196 2584.53  199.38 2585.06  206.73 2588.42   214.3 2593.56  221.35 2601.27
  225.92 2602.69  235.13 2607.36  241.48 2608.01  261.97  2610.7  277.47  2625.5
#Mann= 3 , 0 , 0
       0    .085       0   164.3     .05       0  199.38     .07       0
Bank Sta=164.3,199.38
Exp/Cntr=0.3,0.1

Type RM Length L Ch R = 1 ,124293  ,189.66,213.8,207.51
BEGIN DESCRIPTION:
124214.7
END DESCRIPTION:
XS GIS Cut Line= 6
  936511.7986879  806858.9763155  936484.4542233   806889.358485
  936446.4767674  806915.1830731   936361.407717  806957.7181104
  936323.4302611  806983.5426984  936279.3763714  807026.0767116
#Sta/Elev= 30
       0  2624.5   21.48  2612.4   34.29  2606.1   58.99 2600.89   71.24 2596.72
   72.81 2596.41   83.87 2592.91   91.85 2591.06  100.08 2589.54  108.62 2588.43
  142.05 2578.39  147.07  2577.7  149.57 2577.21  171.43 2576.57   178.5 2577.65
  182.33 2578.47  186.26 2578.99  195.56 2582.05  197.48 2583.15  208.08 2588.38
  220.04 2593.59  226.49  2596.6  230.21 2597.71  242.17 2601.91  247.34 2602.69
  260.24 2603.89  269.83 2604.24  280.07 2606.69  283.82 2609.44  289.16 2611.35
#Mann= 3 , 0 , 0
       0      .1       0  147.07     .05       0   178.5    .075       0
#Block Obstruct= 1 ,-1
  218.25  252.512613.152
Bank Sta=147.07,178.5
Exp/Cntr=0.3,0.1

Type RM Length L Ch R = 1 ,124079  ,171.91,281.17,345.28
BEGIN DESCRIPTION:
124000.9
END DESCRIPTION:
XS GIS Cut Line= 6
  936410.0191882  806729.8533753   936361.407717  806743.5250955
  936297.6056731  806755.6779634  936221.6507614  806801.2507055
  936162.4062989  806849.8621768   936098.604255  806852.8998816
#Sta/Elev= 30
       0 2622.23     9.3  2616.1   16.58 2610.93   25.69 2603.77   56.74 2580.98
   77.77 2579.35  102.26 2578.98  151.09 2578.88  161.13 2575.87  166.58  2573.9
  170.52 2572.49  172.21 2572.69  178.69 2572.39  184.41 2572.78  194.79 2572.12
  196.29 2572.51  199.172574.011  211.32 2579.99  222.93 2582.01  232.02 2582.98
  239.04 2585.38  265.77 2597.78  273.97 2599.66  290.31 2601.29  297.72 2605.62
  301.57 2607.31  306.21 2610.25  313.25 2613.46  329.78 2615.64  344.75  2616.9
#Mann= 3 , 0 , 0
       0     .09       0  166.58     .05       0  199.17     .07       0
#Block Obstruct= 1 ,-1
  267.66   305.42619.734
Bank Sta=166.58,199.17
Exp/Cntr=0.3,0.1

Type RM Length L Ch R = 1 ,123798  ,493.79,450.14,453.15
BEGIN DESCRIPTION:
123719.7
END DESCRIPTION:
XS GIS Cut Line= 6
  936408.4993116  806584.0199858  936297.6056731   806536.927367
  936247.4753494  806518.6990895   936211.016746  806517.1792129
  936171.5204377  806512.6226556   936098.604255  806506.5462217
#Sta/Elev= 30
       0 2603.37   19.32 2592.33   38.53 2582.38   56.77 2575.83   61.83 2574.65
   75.75 2573.24   97.06 2572.04  135.96 2570.81  154.09 2569.86  173.82 2569.42
  175.49 2569.34   190.1 2565.25  198.32 2564.97  199.66 2564.98  210.31  2569.2
  215.54 2571.23   224.4  2575.6   234.5 2577.95  245.75 2586.42  256.29 2589.33
   259.8 2589.81  274.08 2590.76  279.73 2590.59  282.86 2593.84  291.89 2602.07
  295.48    2606  301.92 2611.36  315.63 2617.04  320.89 2618.64  323.24 2619.66
#Mann= 3 , 0 , 0
       0    .075       0  173.82     .05       0  210.31     .07       0
Bank Sta=173.82,210.31
Exp/Cntr=0.3,0.1

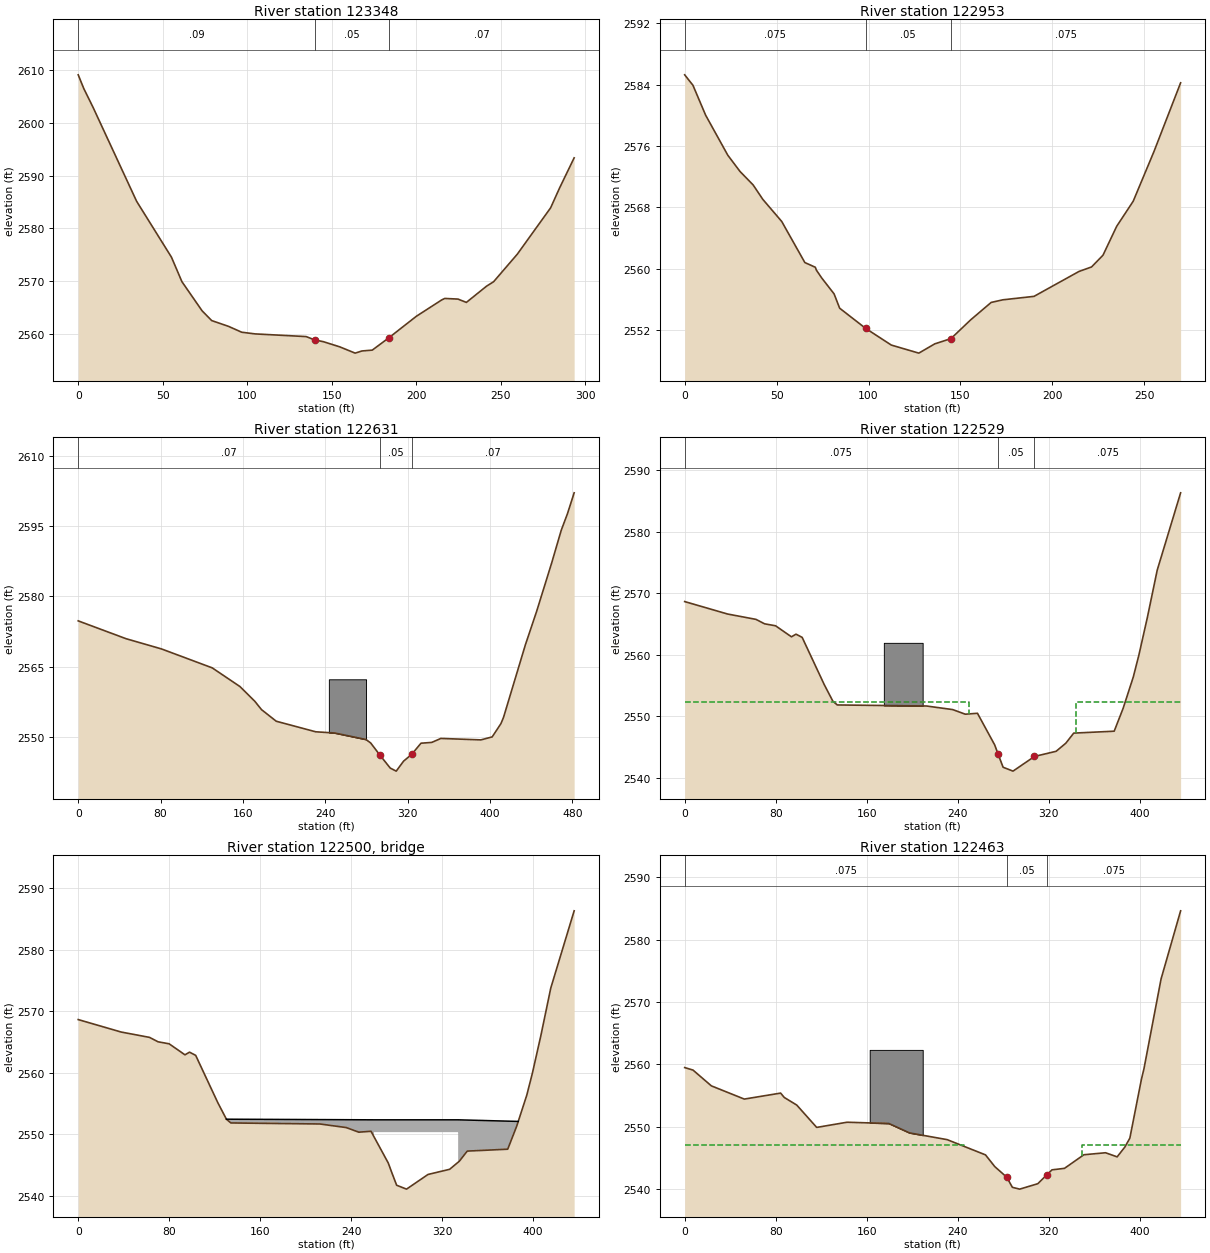
Type RM Length L Ch R = 1 ,123348  ,357.39,394.48,423.14
BEGIN DESCRIPTION:
123269.5
END DESCRIPTION:
XS GIS Cut Line= 6
  936460.1484877  806067.5272008  936400.9040252  806084.2366259
  936349.2548491  806085.7554783  936290.0103867  806073.6036347
  936232.2847767  806064.4884717  936171.5204377  806072.0837581
#Sta/Elev= 30
       0 2609.16    3.29 2606.56    8.79 2602.98   34.56 2585.15   55.15 2574.55
   61.34  2569.9   73.32 2564.35   78.96 2562.51   88.93 2561.41   96.71  2560.3
  104.62 2559.98  134.83 2559.47  140.062558.822  145.06  2558.5  154.64 2557.53
  163.83 2556.33  167.85 2556.74  173.95  2556.9  183.68 2559.22  200.01 2563.32
  214.98 2566.42  216.86 2566.71  224.64 2566.59  229.63 2565.96   241.6 2569.05
  245.72 2569.88  259.74 2575.11  279.46 2583.91  284.76 2587.68  293.38  2593.4
#Mann= 3 , 0 , 0
       0     .09       0  140.06     .05       0  183.68     .07       0
Bank Sta=140.06,183.68
Exp/Cntr=0.3,0.1

Type RM Length L Ch R = 1 ,122953  ,394.69,321.9,278.37
BEGIN DESCRIPTION:
122875.1
END DESCRIPTION:
XS GIS Cut Line= 6
   936502.683525  805783.4557081  936414.5757455  805701.4243625
  936385.7134526  805693.8290762  936347.7359967  805681.6762084
  936312.7962457  805664.9657591  936285.4528053  805634.5835896
#Sta/Elev= 30
       0 2585.27     4.5 2583.91   11.39 2580.02   23.44 2574.81    30.1 2572.69
   37.25 2570.93   42.52 2569.05   52.78 2566.18   65.36 2560.83   71.04 2560.22
   71.62 2559.85   74.48 2558.84   81.26 2556.75   84.28 2554.89   98.37 2552.27
  112.36 2550.09  127.33 2549.04  136.04 2550.25  144.81 2550.93  155.52 2553.37
  166.68 2555.64  173.04 2555.98  189.98 2556.43  214.42 2559.67  221.28 2560.26
   227.5 2561.79  234.94 2565.55  243.94 2568.82  255.26 2575.31  269.71 2584.23
#Mann= 3 , 0 , 0
       0    .075       0   98.37     .05       0  144.81    .075       0
Bank Sta=98.37,144.81
Exp/Cntr=0.3,0.1

Type RM Length L Ch R = 1 ,122631  ,152.18,102.08,66.26
BEGIN DESCRIPTION:
122553.2
END DESCRIPTION:
XS GIS Cut Line= 6
  936804.9843193  805517.6135172  936730.5482601  805452.2926209
  936686.4943703  805420.3915989  936631.8064652  805405.2000021
  936507.2411064  805405.2000021   936361.407717  805421.9104513
#Sta/Elev= 30
       0 2574.76   46.43 2570.95    80.9 2568.76  130.17 2564.71  157.13 2560.71
  171.52 2557.57  178.04 2555.78  192.34  2553.3  230.69 2551.04  249.08 2550.78
  279.52 2549.39  284.12 2548.64  293.212546.003  303.08 2543.28  308.88 2542.63
  316.01 2544.76  323.95 2546.23  332.95  2548.6  343.37 2548.77  352.27 2549.62
  391.15 2549.31  402.08 2549.95  410.59 2552.79  413.11 2554.13  434.35 2569.65
  445.21 2576.76  459.76 2587.07  469.15 2594.13  475.22 2597.69   481.7 2602.14
#Mann= 3 , 0 , 0
       0     .07       0  293.21     .05       0  323.95     .07       0
#Block Obstruct= 1 ,-1
  243.45  279.572562.265
Bank Sta=293.21,323.95
Exp/Cntr=0.5,0.3

Type RM Length L Ch R = 1 ,122529  ,109.51,66.44,47.97
BEGIN DESCRIPTION:
122451.1
END DESCRIPTION:
XS GIS Cut Line= 6
   936794.350304  805254.8100553  936698.6472381  805259.3666126
  936625.7300313  805268.4817755  936545.2185623  805288.2299297
  936417.6144745  805350.5131211  936376.5982896  805358.1084075
#Sta/Elev= 30
       0 2568.64   37.71 2566.62   62.69 2565.75   70.24 2565.03   79.92 2564.71
   93.86 2562.92   97.89 2563.35  103.29 2562.83  122.66 2555.18   130.3 2552.47
  134.18 2551.86  212.59 2551.69  235.61 2551.11  246.73 2550.36  257.42 2550.51
  272.58 2545.37  275.442543.938  279.97 2541.75  288.67 2541.12  307.53  2543.5
  326.58 2544.34  335.09 2545.65  342.04 2547.29  377.63  2547.6  385.48 2551.31
  394.41 2556.39  399.33 2559.95  406.78 2566.05  415.47 2573.75  436.03 2586.29
#Mann= 3 , 0 , 0
       0    .075       0  275.44     .05       0  307.53    .075       0
#XS Ineff= 2 , 0
       0  250.01 2552.37  344.11       0 2552.37
Permanent Ineff=
       F       F
#Block Obstruct= 1 ,-1
   175.1  209.222561.942
Bank Sta=275.44,307.53
Exp/Cntr=0.5,0.3

Type RM Length L Ch R = 3 ,122500  ,,,
BEGIN DESCRIPTION:
122423  FBSTR_1245
END DESCRIPTION:
Bridge Culvert--1,0,-1,-1, 0
Deck Dist Width WeirC Skew NumUp NumDn MinLoCord MaxHiCord MaxSubmerge Is_Ogee
15,29,2.6,0, 7, 7, , , 0.95, 0, 1,1,,
   130.3  260.01  260.01  296.01  334.01  334.01  386.86
 2552.47 2552.37 2552.37 2552.37 2552.37 2552.37 2552.11
                 2550.37 2550.37 2550.37
  103.98  260.17  260.17  297.17  334.17  334.17  395.75
 2552.41 2552.37 2552.37 2552.37 2552.37 2552.37 2552.36
                 2550.37 2550.37 2550.37
BR Coef=-1 , 0 , 0 ,, 0 ,,,0.8,0,,0,
WSPro=,,,, 1 ,,,, 0 ,,,, 0 ,,,,-1 ,-1 ,-1 , 0 , 0 , 0 , 0 , 0
BC Design=,, 0 ,, 0 ,,,,,,

Type RM Length L Ch R = 1 ,122463  ,397.95,254.2,170.35
BEGIN DESCRIPTION:
122384.6
END DESCRIPTION:
XS GIS Cut Line= 6
  936747.2587093  805136.3201063  936666.7462162  805156.0682604
  936584.7148706  805181.8928484  936510.2788113  805224.4278858
  936417.6144745  805292.7875111  936359.8888645  805324.6885331
#Sta/Elev= 30
       0 2559.48    7.31 2559.08   23.45 2556.55   52.39 2554.43   84.33 2555.39
   87.52 2554.69   98.51 2553.47  116.02 2549.89  142.67 2550.72  179.42 2550.52
  197.55 2549.01  230.68 2547.93  264.37 2545.49  272.57  2543.6  283.07 2541.91
  287.98 2540.29  294.44    2540  310.35 2540.87   318.3  2542.3  322.82 2543.09
  333.79 2543.33  350.84 2545.51  369.87 2545.83  380.07 2545.17  386.87 2546.75
  391.23 2548.17  401.43 2557.62  403.62 2559.28  418.67 2573.68  435.85  2584.6
#Mann= 3 , 0 , 0
       0    .075       0  283.07     .05       0   318.3    .075       0
#XS Ineff= 2 , 0
       0  245.16    2547  349.17       0    2547
Permanent Ineff=
       F       F
#Block Obstruct= 1 ,-1
  162.61   209.22562.314
Bank Sta=283.07,318.3
Exp/Cntr=0.5,0.3

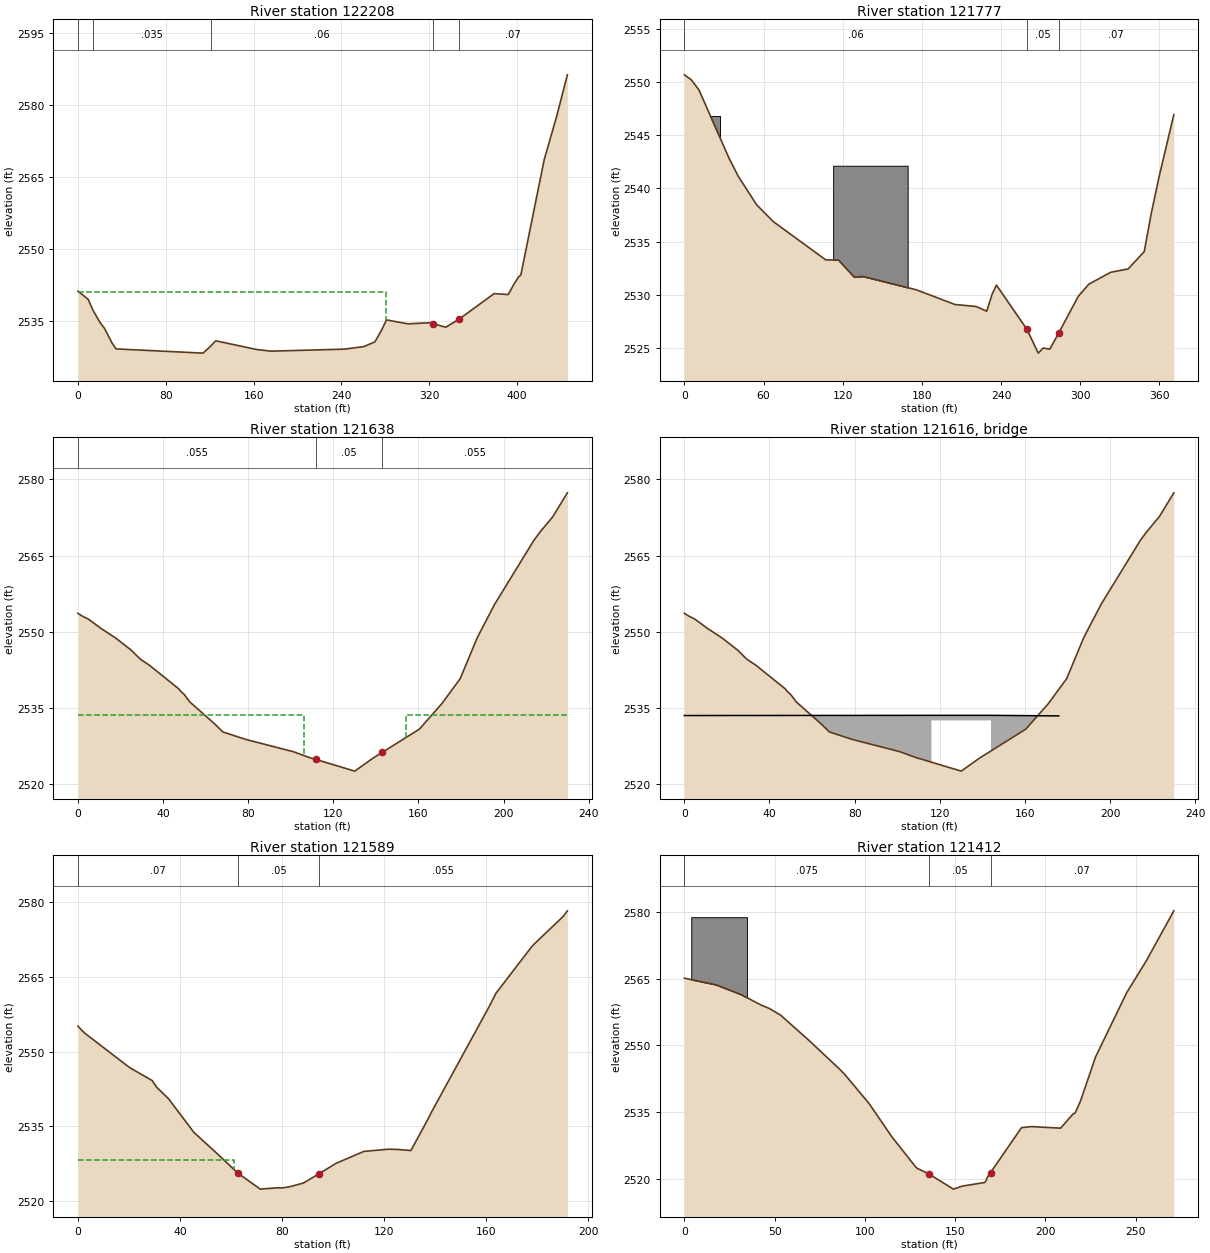
Type RM Length L Ch R = 1 ,122208  ,432.93,430.96,430.28
BEGIN DESCRIPTION:
122130.4
END DESCRIPTION:
XS GIS Cut Line= 6
  936253.6183547  804813.1988459  936242.9177679   805087.708635
  936241.3989155  805146.9541216  936244.4366204   805180.373996
  936244.4366204   805215.313747  936230.7649001  805256.3289077
#Sta/Elev= 30
       0 2541.18    9.38 2539.46   13.84 2537.14   20.05 2534.68   24.18 2533.43
   31.09 2530.37   34.73 2529.13  113.93 2528.25  121.03 2529.73  125.53 2530.82
  163.09 2528.99  175.71 2528.66  242.64 2529.08  260.35 2529.61  270.45 2530.59
  276.43    2533     281 2535.17  300.64 2534.35  321.73 2534.59  323.05  2534.4
  335.03 2533.65  347.12 2535.33  379.02 2540.65  391.86 2540.46  397.14 2542.65
  401.33 2544.13  403.37 2544.56  424.65 2568.59  436.14 2577.74  445.71 2586.24
#Mann= 5 ,-1 , 0
       0     .09       0   13.84    .035       0  121.03     .06       0
  323.05     .05       0  347.12     .07       0
#XS Ineff= 2 , 0
       0     281    2541               0
Permanent Ineff=
       F       F
Bank Sta=323.05,347.12
Exp/Cntr=0.3,0.1

Type RM Length L Ch R = 1 ,121777  ,141.62,139.37,141.53
BEGIN DESCRIPTION:
121699.5
END DESCRIPTION:
XS GIS Cut Line= 6
  935794.6135709  804859.0020276  935818.9776846  804920.3972588
  935811.4940334  805049.7311792  935811.4940334  805105.9379367
  935817.5704673  805160.6258419  935811.4940334  805224.4278858
#Sta/Elev= 30
       0 2550.68     5.2 2550.22   11.09 2549.26   33.74 2542.88    40.8 2541.16
    54.7 2538.48   67.48 2536.88  107.18 2533.29  116.75 2533.28   128.7 2531.67
   135.2 2531.74   175.8 2530.48  205.05  2529.1  221.15 2528.91  229.12 2528.47
   233.2 2530.06  236.52 2530.92  259.54 2526.78  268.19 2524.53  271.98 2525.01
  276.92  2524.9  283.54 2526.38  298.52 2529.87  306.63 2531.02   323.2 2532.13
  336.31 2532.44   348.5 2534.07  353.81 2537.65  359.83 2541.14  370.93 2546.94
#Mann= 3 , 0 , 0
       0     .06       0  259.54     .05       0  283.54     .07       0
#Block Obstruct= 2 ,-1
  112.74  169.242542.138       0   27.05 2546.81
Bank Sta=259.54,283.54
Exp/Cntr=0.5,0.3

Type RM Length L Ch R = 1 ,121638  ,58.73,49.18,43.33
BEGIN DESCRIPTION:
121560.1
END DESCRIPTION:
XS GIS Cut Line= 6
  935635.2794985  805014.7924524  935673.2569544  805051.2510558
  935673.2569544  805099.8615028  935676.2946592  805146.9541216
  935676.2946592  805172.7787097  935665.6606439  805227.4655906
#Sta/Elev= 30
       0 2553.62    2.04 2553.07    4.87 2552.48   11.04 2550.58   17.62 2548.78
   25.01 2546.36   29.41 2544.54   33.46 2543.42   47.48 2538.69   48.29 2538.23
    49.9 2537.63   52.65 2536.11   64.12 2531.86   68.11 2530.22   78.73 2528.76
  101.26 2526.32  109.36 2525.08  111.872524.791  130.09 2522.49  138.65 2525.05
  143.09 2526.21  160.45 2530.77  171.11 2535.85  179.63 2540.73  187.68 2548.84
  195.84 2555.41   214.2 2567.97  217.06  2569.6  223.16 2572.67  229.98 2577.37
#Mann= 3 , 0 , 0
       0    .055       0  111.87     .05       0  143.09    .055       0
#XS Ineff= 2 , 0
       0  106.09 2533.49  154.09       0 2533.49
Permanent Ineff=
       F       F
Bank Sta=111.87,143.09
Exp/Cntr=0.5,0.3

Type RM Length L Ch R = 3 ,121616  ,,,
Node Photo=H:\PROJ\06-0741\CE\GIS\DATA\FRENCH_BROAD_RIVER\SHAPEFILES\survey_data\photos\FBSTR_1774.JPG
BEGIN DESCRIPTION:
121535.6  FBSTR_1774
END DESCRIPTION:
Bridge Culvert--1,0,-1,-1, 0
Deck Dist Width WeirC Skew NumUp NumDn MinLoCord MaxHiCord MaxSubmerge Is_Ogee
16,14,2.6,0, 7, 7, , , 0.95, 0, 1,1,,
       0  116.09  116.09  130.09  144.09  144.09  175.93
 2533.45 2533.49 2533.49 2533.49 2533.49 2533.49 2533.38
                 2532.49 2532.49 2532.49
   46.24   76.15   76.15   90.15  104.15  104.15  133.89
 2533.43 2533.49 2533.49 2533.49 2533.49 2533.49  2533.4
                 2532.49 2532.49 2532.49
BR Coef=-1 , 0 , 0 ,, 0 ,,,0.8,0,,0,
WSPro=,,,, 1 ,,,, 0 ,,,, 0 ,,,,-1 ,-1 ,-1 , 0 , 0 , 0 , 0 , 0
BR D #Sta/Elev= 37
       0 2555.15    1.65 2554.24    2.84 2553.67   20.28 2546.81   28.16 2544.51
   29.14  2544.2    30.8 2542.91   35.59 2540.51   55.41 2533.82   64.26 2529.68
   72.54 2525.68   73.97 2525.18   77.73 2523.82   80.52 2522.76   81.53 2522.41
   88.21 2522.68   90.15 2522.65   93.26 2522.92   98.38 2523.64  104.53 2525.53
  111.03 2527.53  111.19  2527.6  111.44 2527.62  121.72 2530.43  125.56 2530.37
  130.44 2530.16  135.37 2534.78  137.77 2537.13  137.88 2537.19  138.14 2537.52
  161.21 2559.16  163.79 2561.75  177.58 2570.96   178.3 2571.37  178.88 2571.69
  190.08 2577.15  191.74 2578.29
BR D #Mann= 3
       0     .07   72.54     .05  104.53    .055
BR D Banks=72.54,104.53
BC Design=,, 0 ,, 0 ,,,,,,

Type RM Length L Ch R = 1 ,121589  ,150.87,177.23,177.85
BEGIN DESCRIPTION:
121510.9
END DESCRIPTION:
XS GIS Cut Line= 6
  935595.7821661  805052.7699082  935618.5690493  805080.1133487
  935626.1643356  805107.4578134  935626.1643356  805151.5106789
  935626.1643356  805178.8551436  935639.8360558  805233.5420245
#Sta/Elev= 30
       0 2555.15    1.65 2554.24    2.84 2553.67   20.28 2546.81   29.14  2544.2
    30.8 2542.91   35.59 2540.51   45.41 2533.82   54.26 2529.68   62.54 2525.68
   71.43 2522.41   78.21 2522.68   80.15 2522.65   83.26 2522.92   88.38 2523.64
   94.53 2525.53  101.19  2527.6     112 2529.98  121.72 2530.43  125.56 2530.37
  130.44 2530.16  135.37 2534.78  137.88 2537.19  138.14 2537.52  161.21 2559.16
  163.79 2561.75  177.58 2570.96  178.88 2571.69  190.08 2577.15  191.74 2578.29
#Mann= 3 , 0 , 0
       0     .07       0   62.54     .05       0   94.53    .055       0
#XS Ineff= 2 , 0
       0   61.15  2528.3  119.15       0 2528.31
Permanent Ineff=
       F       F
Bank Sta=62.54,94.53
Exp/Cntr=0.5,0.3

Type RM Length L Ch R = 1 ,121412  ,200.15,215.01,216.12
BEGIN DESCRIPTION:
121333.7
END DESCRIPTION:
XS GIS Cut Line= 6
  935530.4612697  804990.4867168  935469.6979549  805066.4416285
  935451.4686532  805099.8615028  935449.9487766  805130.2436724
  935449.9487766  805177.3362912  935465.1403734  805233.5420245
#Sta/Elev= 30
       0  2565.1   17.55 2563.61   31.51  2561.4   41.97 2559.17   47.09 2558.29
   53.28 2556.81   69.04 2551.12   86.42 2544.51   89.14 2543.34  102.28 2536.97
   114.9  2529.5  127.91 2522.82  128.94 2522.41  135.34 2521.18  149.01 2517.74
  153.95 2518.42  166.32 2519.23  166.91  2519.5  167.87 2520.45  169.56 2521.44
   186.7 2531.54  192.15 2531.78  208.38 2531.43  215.16 2534.57   216.4 2534.82
   219.3 2537.43  227.76 2547.44  244.97 2561.84   255.8 2568.97  271.08 2580.22
#Mann= 3 , 0 , 0
       0    .075       0  135.34     .05       0  169.56     .07       0
#Block Obstruct= 1 ,-1
    3.82   34.662578.793
Bank Sta=135.34,169.56
Exp/Cntr=0.3,0.1

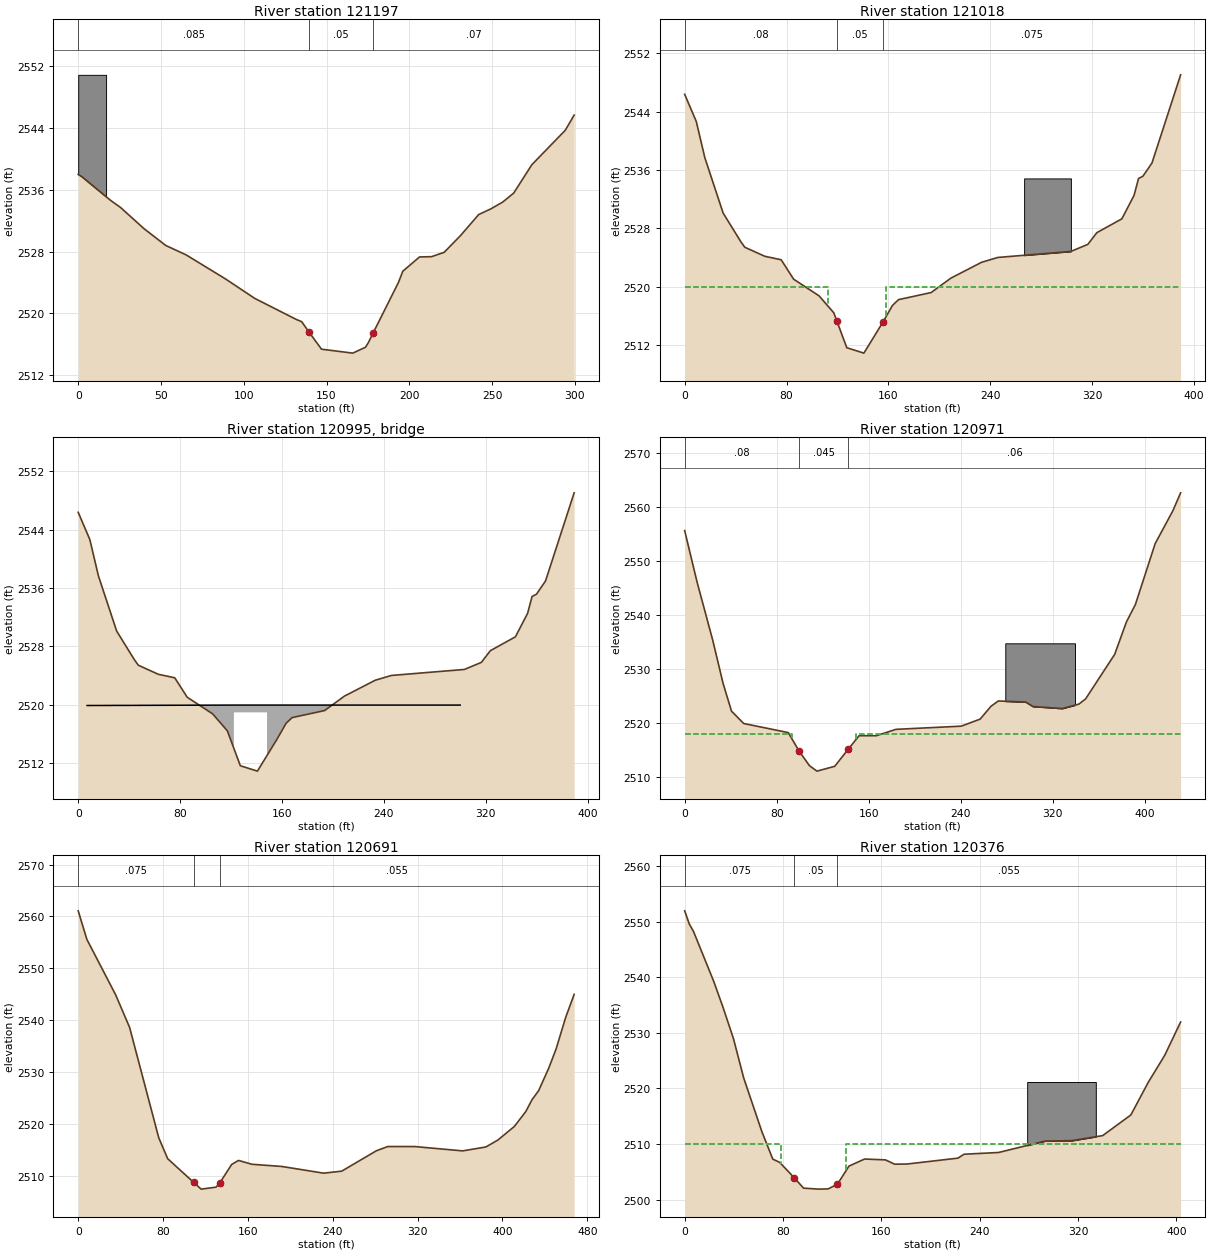
Type RM Length L Ch R = 1 ,121197  ,164.98,178.26,179.93
BEGIN DESCRIPTION:
121118.7
END DESCRIPTION:
XS GIS Cut Line= 6
  935339.0551381  804954.0281134  935298.0399774  804987.4490119
  935244.8709247  805051.2510558  935235.7567859  805107.4578134
  935235.7567859  805160.6258419  935249.4285061   805212.275018
#Sta/Elev= 30
       0 2537.97    1.94 2537.72   19.45 2534.63   25.64 2533.68   39.84 2530.94
   52.84 2528.79   65.31 2527.55   88.95 2524.46  106.63 2521.94   131.7 2519.22
  134.99 2518.93  139.582517.538  146.99 2515.37  165.88 2514.86  173.55 2515.62
   175.3 2516.22  178.18 2517.47  193.52 2524.02  196.09 2525.45  206.23  2527.3
   213.4 2527.33  221.05 2527.89  230.79 2530.02  241.95 2532.78  249.43 2533.53
  256.48  2534.4  263.08 2535.55  274.08 2539.23  294.22 2543.67  299.61 2545.64
#Mann= 3 , 0 , 0
       0    .085       0  139.58     .05       0  178.18     .07       0
#Block Obstruct= 1 ,-1
       0   16.842550.847
Bank Sta=139.58,178.18
Exp/Cntr=0.5,0.3

Type RM Length L Ch R = 1 ,121018  ,87.48,47.21,62.2
BEGIN DESCRIPTION:
120940.4
END DESCRIPTION:
XS GIS Cut Line= 6
  935155.2442927  804922.1270914   935053.464793  805055.8076131
  935044.3506542  805078.5944963   935056.503522  805142.3965402
  935091.4422488  805183.4117009  935152.2065879  805232.0231721
#Sta/Elev= 30
       0 2546.38    9.13 2542.65   15.84 2537.69    30.2 2530.11   44.16 2526.17
   47.21 2525.43   62.89 2524.19   75.81 2523.71   85.57 2521.05  105.53 2518.77
   117.1 2516.45  119.552515.302  127.32 2511.66  140.73 2510.92  155.95 2515.24
  163.22 2517.46  167.95 2518.25  193.55 2519.22  209.11  2521.2  233.23 2523.37
  245.97 2524.03  303.25 2524.85  316.62 2525.82  323.65 2527.42  343.34 2529.32
  352.93 2532.54  356.43 2534.85  359.87 2535.16  366.99 2536.97  389.48 2549.05
#Mann= 3 , 0 , 0
       0     .08       0  119.55     .05       0  155.95    .075       0
#XS Ineff= 2 , 0
       0  112.26 2519.97  158.26       0 2519.97
Permanent Ineff=
       F       F
#Block Obstruct= 1 ,-1
  266.58   303.32534.857
Bank Sta=119.55,155.95
Exp/Cntr=0.5,0.3

Type RM Length L Ch R = 3 ,120995  ,,,
Node Photo=H:\PROJ\06-0741\CE\GIS\DATA\FRENCH_BROAD_RIVER\SHAPEFILES\survey_data\photos\FBSTR_1246.JPG
BEGIN DESCRIPTION:
120920.5  FBSTR_1246
END DESCRIPTION:
Bridge Culvert--1,0,-1,-1, 0
Deck Dist Width WeirC Skew NumUp NumDn MinLoCord MaxHiCord MaxSubmerge Is_Ogee
12,10,2.6,0, 7, 7, , , 0.95, 0, 1,1,,
       7  122.26  122.26  135.26  148.26  148.26     300
 2519.91 2519.97 2519.97 2519.97 2519.97 2519.97 2519.97
                 2518.97 2518.97 2518.97
   41.88  108.07  108.07  122.07  134.07  134.07     400
  2519.7 2519.97 2519.97 2519.97 2519.97 2519.97 2519.88
                 2518.97 2518.97 2518.97
BR Coef=-1 , 0 , 0 ,, 0 ,,,0.8,0,,0,
WSPro=,,,, 1 ,,,, 0 ,,,, 0 ,,,,-1 ,-1 ,-1 , 0 , 0 , 0 , 0 , 0
BC Design=,, 0 ,, 0 ,,,,,,

Type RM Length L Ch R = 1 ,120971  ,303.14,280.54,173.12
BEGIN DESCRIPTION:
120893.2
END DESCRIPTION:
XS GIS Cut Line= 6
  935024.6025001  804902.3789373  935035.2354913  804961.6244239
  935029.1590574  805005.6783136   934995.739183  805127.2059675
  935003.3344693   805273.039357  935023.0826235  805323.1686565
#Sta/Elev= 30
       0 2555.57   10.78 2546.05   24.42 2535.26    33.4 2527.29   40.72 2522.16
   51.32 2519.88   90.04  2518.2   99.42 2514.79  108.46 2512.08  114.95 2511.07
   130.4 2511.96  142.01 2515.08   151.6 2517.62  166.61 2517.62  183.62  2518.8
  240.43 2519.39  256.79 2520.69  266.33 2523.08  272.62 2524.05  296.43 2523.85
  302.75 2523.02  328.16 2522.65  342.66 2523.47  348.52 2524.44  373.77 2532.67
  383.93 2538.65  391.76 2541.89  408.97 2553.17  424.41 2559.27  431.08 2562.56
#Mann= 3 , 0 , 0
       0     .08       0   99.42    .045       0  142.01     .06       0
#XS Ineff= 2 , 0
       0   93.07    2518  149.07       0    2518
Permanent Ineff=
       F       F
#Block Obstruct= 1 ,-1
  278.68  339.252534.719
Bank Sta=99.42,142.01
Exp/Cntr=0.5,0.3

Type RM Length L Ch R = 1 ,120691  ,330.22,314.66,258.39
BEGIN DESCRIPTION:
120612.7
END DESCRIPTION:
XS GIS Cut Line= 5
  934705.5912564  804903.8988139  934754.2027277   805007.197166
  934780.0273157   805061.884047  934843.8293596  805203.1608792
  934892.4408308  805332.2838194
#Sta/Elev= 30
       0 2561.09    8.17 2555.58   35.34 2544.86   48.45  2538.6   75.93 2517.29
   84.39 2513.24  108.91 2508.66  115.91 2507.37  129.94 2507.75   133.7 2508.62
  144.66 2512.13  151.15 2512.91  163.81 2512.17  192.15 2511.74  231.42 2510.45
  248.46 2510.84  281.13 2514.77  291.81 2515.59  317.29 2515.59  362.53 2514.75
   384.4 2515.51  395.76 2516.85  411.29 2519.48     422 2522.34  427.87 2524.61
  434.11 2526.37   443.6 2530.68  450.54 2534.38  459.78 2540.61  467.63 2544.96
#Mann= 3 , 0 , 0
       0    .075       0  108.91     .05       0   133.7    .055       0
Bank Sta=108.91,133.7
Exp/Cntr=0.5,0.3

Type RM Length L Ch R = 1 ,120376  ,42.15,45.1,54.53
BEGIN DESCRIPTION:
120298.0
END DESCRIPTION:
XS GIS Cut Line= 5
  934415.4443541  805080.1133487  934459.4982438  805145.4352692
  934500.5134045  805183.4117009  934579.5070453  805254.8100553
  934664.5760957  805393.0471343
#Sta/Elev= 30
       0    2552    3.69 2549.66    7.23 2548.26   23.59 2539.32   30.89 2534.82
   39.64 2529.02   48.08 2521.85   62.74 2512.27   71.67 2507.28   77.28 2506.69
   89.34 2503.87   96.71 2502.05  109.25 2501.87  116.72 2501.91  124.27 2502.75
  133.68 2506.02  146.38 2507.29   163.3 2507.14  170.95 2506.36  180.82 2506.39
  222.25 2507.45  227.36 2508.16  255.39 2508.47  293.21 2510.53  315.09  2510.6
  340.08 2511.51     363 2515.23  377.13  2521.1  390.52 2525.96  403.48 2531.97
#Mann= 3 , 0 , 0
       0    .075       0   89.34     .05       0  124.27    .055       0
#XS Ineff= 2 , 0
       0   78.43 2509.99  131.43       0 2509.99
Permanent Ineff=
       F       F
#Block Obstruct= 1 ,-1
  278.64  334.47 2521.17
Bank Sta=89.34,124.27
Exp/Cntr=0.5,0.3