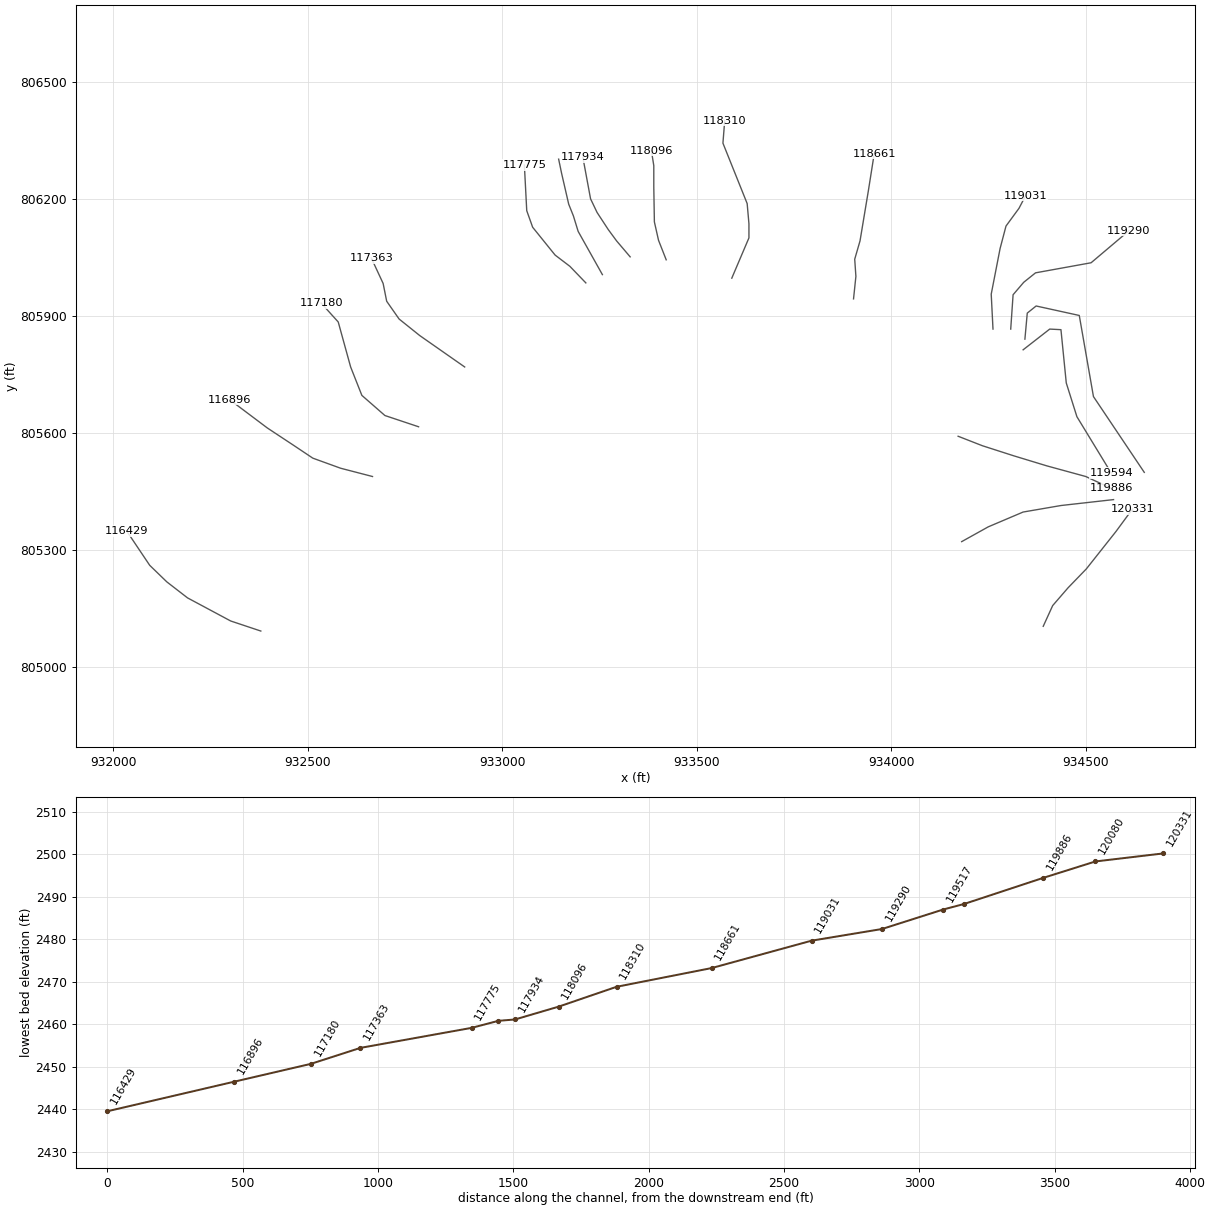
HEC-RAS study lds_big_laurel_crk.prj: lds_big_laurel_crk

--- lds_big_laurel_crk.g20 (geometry) --- (continued)

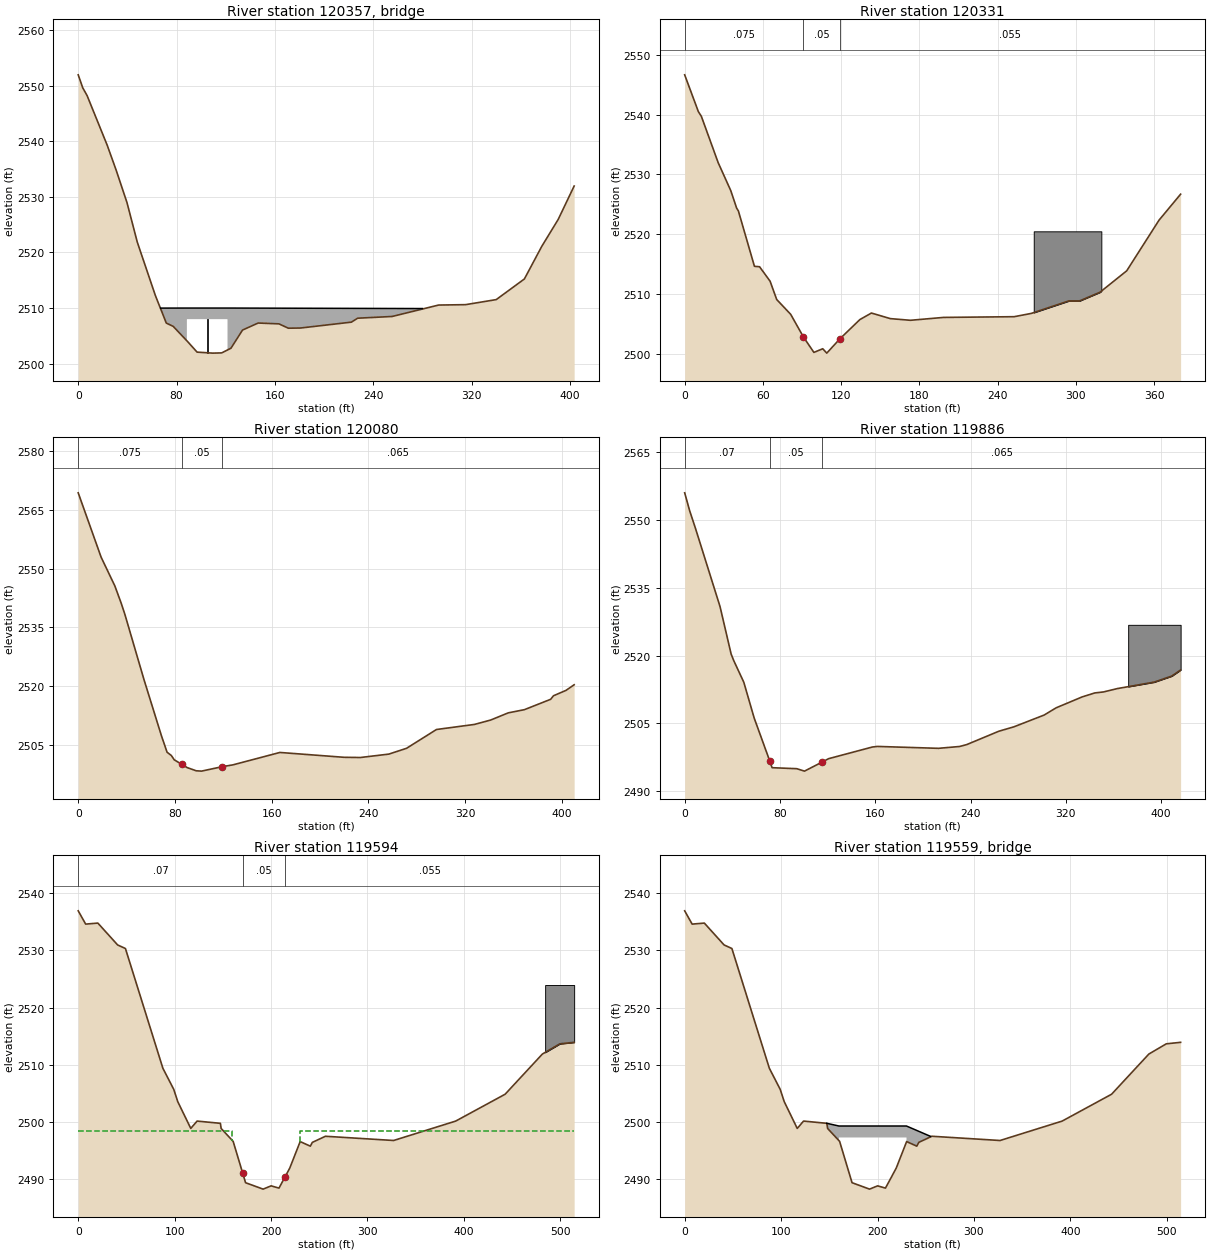
Type RM Length L Ch R = 3 ,120357  ,,,
BEGIN DESCRIPTION:
120277  FBSTR_1246A
END DESCRIPTION:
Bridge Culvert--1,0,-1,-1, 0
Deck Dist Width WeirC Skew NumUp NumDn MinLoCord MaxHiCord MaxSubmerge Is_Ogee
11,12,2.6,0, 7, 7, , , 0.95, 0, 1,1,,
    67.1   88.43   88.43  105.43  121.43  121.43  279.98
 2509.98 2509.99 2509.99 2509.99 2509.99 2509.99  2509.9
                 2507.99 2507.99 2507.99
   69.16   85.98   85.98  102.98  118.98  118.98  313.74
 2509.98 2509.99 2509.99 2509.99 2509.99 2509.99 2509.98
                 2507.99 2507.99 2507.99
Pier Skew, UpSta & Num, DnSta & Num=  ,104.93, 2 ,102.48, 2 , 0 , 0 , 0 ,,
       1       1
    2500 2507.99
       1       1
    2500 2507.99
BR Coef=-1 , 0 , 0 ,, 0 ,,,0.8,0,,0,
WSPro=,,,, 1 ,,,, 0 ,,,, 0 ,,,,-1 ,-1 ,-1 , 0 , 0 , 0 , 0 , 0
BC Design=,, 0 ,, 0 ,,,,,,

Type RM Length L Ch R = 1 ,120331  ,272.31,251.32,136.55
BEGIN DESCRIPTION:
120252.9
END DESCRIPTION:
XS GIS Cut Line= 6
  934391.1386185  805104.4190843  934415.4443541  805157.5871128
  934454.9406624  805203.1608792   934502.032257  805251.7713262
  934577.9871687  805347.4743921   934620.522206  805405.2000021
#Sta/Elev= 30
       0 2546.63   10.49 2540.49   12.78 2539.71   25.67 2531.98   35.32 2527.32
   39.87 2524.37   41.18 2523.92    53.5 2514.67   57.42  2514.6   65.52 2512.18
   70.57 2509.13   81.32 2506.65   91.112502.861   99.11  2500.3  105.88 2500.91
  108.97 2500.18  118.97 2502.55  134.36 2505.78  143.22 2506.87  157.73 2505.94
  173.07 2505.66  198.55 2506.14  252.69 2506.26  265.86 2506.81  294.71  2508.9
  302.88  2508.9  318.48 2510.34     339 2513.92  363.77 2522.37  380.33 2526.71
#Mann= 3 , 0 , 0
       0    .075       0   91.11     .05       0  118.97    .055       0
#XS Ineff= 2 , 0
       0   70.98    2506  136.43       0    2506
Permanent Ineff=
       F       F
#Block Obstruct= 1 ,-1
  267.69  319.53 2520.51
Bank Sta=91.11,118.97
Exp/Cntr=0.5,0.3

Type RM Length L Ch R = 1 ,120080  ,228.38,193.87,81.31
BEGIN DESCRIPTION:
120001.6
END DESCRIPTION:
XS GIS Cut Line= 5
  934181.5031851   805321.649804  934249.8628104  805359.6272599
  934339.4894424  805397.6047157  934436.7113606   805414.315165
  934571.9107348  805429.5057377
#Sta/Elev= 30
       0 2569.38   18.95 2552.94   30.31  2545.6   35.51 2541.23   38.63 2538.31
   54.39 2521.69   68.76 2507.41    73.5 2503.12   77.04 2502.28   79.46 2501.18
   85.62 2500.04    90.1  2499.2   97.55 2498.38  101.97 2498.29  119.35 2499.44
  127.85 2499.88  166.84 2503.06  219.93 2501.82  233.45 2501.77     257 2502.64
  271.66 2504.13  296.34 2508.92  327.79 2510.22   341.2 2511.34   355.7 2513.17
  369.11 2513.99  390.81 2516.64  393.13 2517.54  403.52 2518.92  410.24 2520.35
#Mann= 3 , 0 , 0
       0    .075       0   85.62     .05       0  119.35    .065       0
Bank Sta=85.62,119.35
Exp/Cntr=0.3,0.1

Type RM Length L Ch R = 1 ,119886  ,340.09,291.56,95.53
BEGIN DESCRIPTION:
119807.7
END DESCRIPTION:
XS GIS Cut Line= 6
  934172.3880221  805592.0495764  934234.6712136  805567.7438408
  934315.1837068  805541.9192528  934400.2527572  805516.0946648
  934500.5134045  805488.7512243  934565.8343009  805458.3690548
#Sta/Elev= 30
       0 2556.06    4.19 2552.09    9.04 2548.21    29.7 2530.84   38.98 2520.36
   41.11 2518.94   49.63  2514.1   58.33 2506.18   71.43 2496.64   73.38 2495.17
   94.05 2494.95  100.56 2494.41  115.48 2496.43  120.83 2497.17  157.52 2499.75
  161.84 2499.88  213.08 2499.46  230.82 2499.87  236.67 2500.28  263.73 2503.25
  276.41 2504.23  301.71 2506.83  311.76 2508.43  333.63 2510.85  344.24 2511.73
  351.55 2511.95  363.26  2512.7  394.16 2514.13  408.85 2515.47  416.28 2516.82
#Mann= 3 , 0 , 0
       0     .07       0   71.43     .05       0  115.48    .065       0
#Block Obstruct= 1 ,-1
  372.25  416.282526.822
Bank Sta=71.43,115.48
Exp/Cntr=0.5,0.3

Type RM Length L Ch R = 1 ,119594  ,64.64,77.5,62.11
BEGIN DESCRIPTION:
119516.2
END DESCRIPTION:
XS GIS Cut Line= 6
  934339.4894424  805813.8378776  934407.8490677  805867.0059062
  934436.7113606  805865.4870537  934450.3830809   805728.767803
  934477.7275455  805642.1799001  934565.8343009   805497.865363
#Sta/Elev= 30
       0 2536.88    7.74 2534.56   20.38 2534.74   40.88 2530.92   48.97  2530.3
   87.79  2509.4    99.1  2505.7  103.22 2503.57  116.73 2498.89  123.29 2500.17
  147.42 2499.78  148.24 2498.88  160.68 2496.63   170.62491.072  173.57 2489.41
  191.75 2488.29  200.04 2488.86  208.21 2488.47  214.26 2490.35  219.43 2491.98
  230.18 2496.59  240.73 2495.79  242.79 2496.45  256.39 2497.52  327.07 2496.78
  391.47 2500.17  442.74 2504.86  481.35 2511.87  499.46 2513.66  514.31 2513.92
#Mann= 3 , 0 , 0
       0     .07       0   170.6     .05       0  214.26    .055       0
#XS Ineff= 2 , 0
       0     160  2498.5     230       0  2498.5
Permanent Ineff=
       F       F
#Block Obstruct= 1 ,-1
  484.23  514.312523.923
Bank Sta=170.6,214.26
Exp/Cntr=0.5,0.3

Type RM Length L Ch R = 3 ,119559  ,,,
Node Photo=H:\PROJ\06-0741\CE\GIS\DATA\FRENCH_BROAD_RIVER\SHAPEFILES\survey_data\photos\FBSTR_1248.JPG
BEGIN DESCRIPTION:
119470.2  FBSTR_1248
END DESCRIPTION:
Bridge Culvert--1,0,-1,-1, 0
Deck Dist Width WeirC Skew NumUp NumDn MinLoCord MaxHiCord MaxSubmerge Is_Ogee
18,52,2.6,0, 5, 5, , , 0.95, 0, 0,0,,
  147.42     160     195     230  254.97
 2499.78 2499.31 2499.31 2499.31  2497.5
         2497.31 2497.31 2497.31
  222.96  235.05  270.05  305.05  323.23
 2497.96 2499.31 2499.31 2499.31 2497.51
         2497.31 2497.31 2497.31
BR Coef=-1 , 0 , 0 ,, 0 ,,,0.8,0,,0,
WSPro=,,,, 1 ,,,, 0 ,,,, 0 ,,,,-1 ,-1 ,-1 , 0 , 0 , 0 , 0 , 0
BC Design=,, 0 ,, 0 ,,,,,,

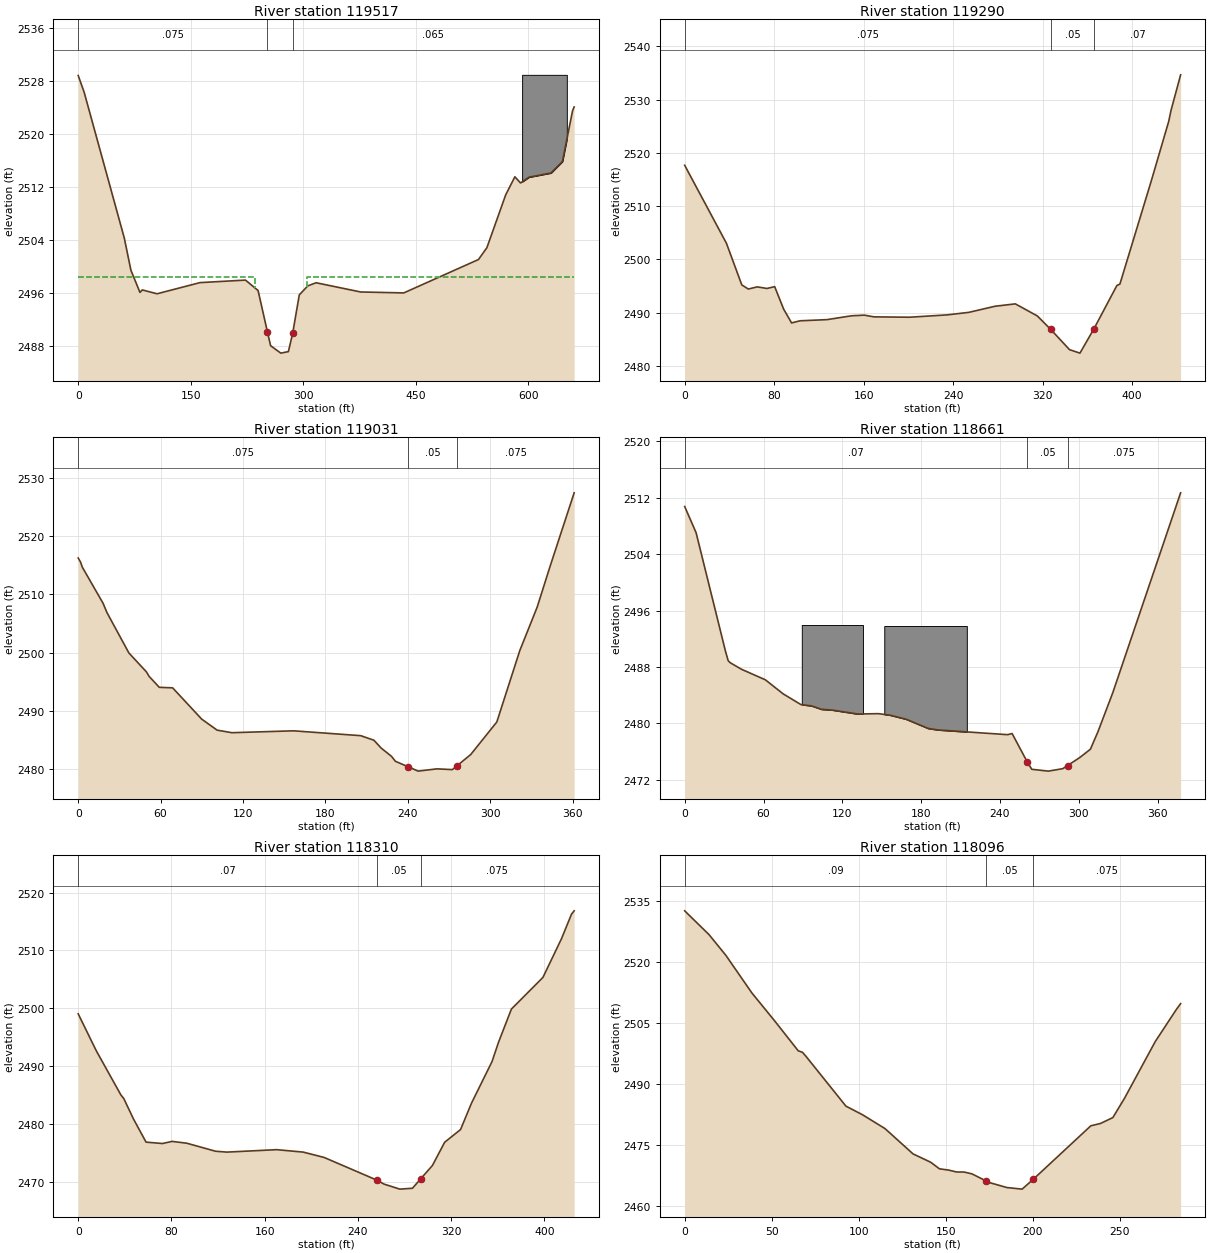
Type RM Length L Ch R = 1 ,119517  ,44.56,226.1,622.04
BEGIN DESCRIPTION:
119438.7
END DESCRIPTION:
XS GIS Cut Line= 6
  934344.0459997  805841.1813181  934350.1224336   805908.022091
  934372.9093168  805926.2503686  934483.8029553  805901.9456571
  934520.2615587  805693.8290762  934650.9043755  805499.3842155
#Sta/Elev= 30
       0 2528.79    7.86  2526.3   61.44 2504.31   70.26 2499.46   82.34 2496.12
   85.39  2496.5  105.11 2495.92  162.32  2497.6  222.96 2497.98  239.76 2496.41
  252.182490.185  256.45  2488.1  270.05 2486.98  280.14 2487.21   285.9 2489.99
  294.66 2495.75  306.03 2497.11  317.07 2497.58  376.54 2496.19  433.98 2496.05
  533.53 2501.08  544.72 2502.86  569.79 2510.82  582.01 2513.54  589.55 2512.61
  600.75 2513.48  630.13 2514.11  645.42 2515.85  658.92 2523.48  661.03 2524.06
#Mann= 3 , 0 , 0
       0    .075       0  252.18     .05       0   285.9    .065       0
#XS Ineff= 2 , 0
       0  235.05  2498.5  305.05       0  2498.5
Permanent Ineff=
       F       F
#Block Obstruct= 1 ,-1
  591.68  651.262528.898
Bank Sta=252.18,285.9
Exp/Cntr=0.5,0.3

Type RM Length L Ch R = 1 ,119290  ,58.4,259.83,268.21
BEGIN DESCRIPTION:
119212.6
END DESCRIPTION:
XS GIS Cut Line= 6
  934307.5884204  805867.0059062  934313.6648543  805955.1136857
  934341.0082948  805987.0147076  934371.3904643  806011.3204432
  934514.1851248  806037.1450313  934611.4080672  806119.1763769
#Sta/Elev= 30
       0 2517.67   37.34 2503.02   51.05 2495.21   56.89 2494.43    64.8 2494.84
   73.63 2494.54   80.46 2494.88   88.52 2490.64   95.56 2488.07  103.14 2488.47
  127.25 2488.69  149.17 2489.41  160.56 2489.53  169.21 2489.21  200.94 2489.14
  234.57 2489.58  253.89 2490.05  277.41  2491.2  295.55 2491.65  315.24 2489.38
  327.142486.865  344.02 2483.05  353.33  2482.4  365.912486.996  386.33 2495.09
  389.05 2495.37  417.38 2514.94  432.67 2525.91  434.73 2527.97  443.31 2534.65
#Mann= 3 , 0 , 0
       0    .075       0  327.14     .05       0  365.91     .07       0
Bank Sta=327.14,365.91
Exp/Cntr=0.3,0.1

Type RM Length L Ch R = 1 ,119031  ,369.92,369.26,392.86
BEGIN DESCRIPTION:
118952.7
END DESCRIPTION:
XS GIS Cut Line= 6
  934262.0156782  805867.0059062  934257.4580968  805956.6325381
  934280.2439558  806073.6036347  934295.4355526  806131.3292447
   934328.855427  806176.9019869  934345.5658763  806208.8030088
#Sta/Elev= 30
       0  2516.2    1.71  2515.5    3.02 2514.62   18.13 2508.43   20.93 2506.85
   36.91 2499.92   49.67 2496.68   51.55 2495.93   59.02 2494.03   68.77 2493.94
   89.91 2488.58  101.13 2486.69  111.88 2486.25  156.95 2486.57  205.72 2485.74
  215.32 2484.96  220.62 2483.61  228.07 2482.21  230.97 2481.35   240.4 2480.39
  247.54 2479.66  261.18 2480.05  272.45 2479.92  275.932480.594  285.83 2482.51
  304.83 2488.09  321.58 2500.35   334.2 2507.78  343.65 2514.81  361.13 2527.38
#Mann= 3 , 0 , 0
       0    .075       0   240.4     .05       0  275.93    .075       0
Bank Sta=240.4,275.93
Exp/Cntr=0.3,0.1

Type RM Length L Ch R = 1 ,118661  ,283.25,351.72,385.87
BEGIN DESCRIPTION:
118583.5
END DESCRIPTION:
XS GIS Cut Line= 6
  933903.5081263  805944.4796703  933909.5845602  806002.2052803
  933906.5468554    806046.25917  933920.2185756  806093.3517888
  933941.4855822  806220.9558766   933956.677179  806316.6589424
#Sta/Elev= 30
       0 2510.75    8.69 2507.04   30.96  2490.3   33.13 2488.88   34.71 2488.59
   43.32 2487.66   61.43 2486.17   74.88 2484.19   88.46 2482.66   96.58 2482.47
  104.25 2481.98  112.28 2481.88  131.74 2481.32  147.48 2481.37  156.19 2481.16
  168.58 2480.58  185.37 2479.27  192.77 2479.06  245.88 2478.39  249.25 2478.55
  260.89 2474.48  264.23 2473.48  276.88 2473.22  287.81 2473.57  291.442474.012
  300.63 2475.13  308.85 2476.33  314.66 2478.84  325.87 2484.34  377.51 2512.69
#Mann= 3 , 0 , 0
       0     .07       0  260.89     .05       0  291.44    .075       0
#Block Obstruct= 2 ,-1
  151.94  214.772493.803   89.14  135.692493.948
Bank Sta=260.89,291.44
Exp/Cntr=0.3,0.1

Type RM Length L Ch R = 1 ,118310  ,247.09,214.17,190.32
BEGIN DESCRIPTION:
118231.8
END DESCRIPTION:
XS GIS Cut Line= 6
  933590.5743408   805997.648723  933634.6282305  806100.9470752
  933634.6282305  806137.4056786  933630.0706491  806189.0548547
  933567.7874576  806344.0023829  933572.3450391  806401.7279929
#Sta/Elev= 30
       0 2499.06    15.5 2492.69   36.65 2485.06    39.1 2484.45   47.45 2480.91
   58.23 2476.92   72.26 2476.68   80.59 2477.05   93.26 2476.73  117.88 2475.35
  127.65  2475.2  170.31 2475.62  193.11  2475.2  211.01 2474.28  256.13 2470.38
  262.56 2469.67  276.04 2468.81  286.83 2468.96  293.86 2470.57  303.99 2472.89
   314.5  2476.9  328.13 2479.09  337.54 2483.65  355.16 2490.83  360.64 2494.11
   371.8 2499.89  398.84 2505.35  414.77 2512.03  423.35 2516.26  425.63 2516.84
#Mann= 3 , 0 , 0
       0     .07       0  256.13     .05       0  293.86    .075       0
Bank Sta=256.13,293.86
Exp/Cntr=0.3,0.1

Type RM Length L Ch R = 1 ,118096  ,124.8,161.05,173.55
BEGIN DESCRIPTION:
118017.6
END DESCRIPTION:
XS GIS Cut Line= 6
  933421.9540681  806044.7403176   933402.205914  806094.8706413
  933391.5729228  806141.9622359  933390.0530462  806231.5888678
  933390.0530462  806286.2767729  933383.9766123  806324.2542288
#Sta/Elev= 30
       0 2532.63   13.98 2526.78   23.66 2521.68   38.65  2512.4   51.45 2505.68
   65.23 2498.19    67.7 2497.81   69.95 2496.69   92.66 2484.56  102.16 2482.45
  115.13 2479.03  131.21 2472.81  141.39 2470.75  146.37 2469.14  151.75 2468.82
  156.18 2468.36  160.52 2468.35  165.05  2467.9  173.28 2466.13   174.9 2465.78
  185.14 2464.53  193.89 2464.14  200.162466.513  233.35 2479.72  238.92  2480.3
  246.02 2481.75  252.69 2486.48  270.38 2500.46  282.37 2508.27  284.95  2509.8
#Mann= 3 , 0 , 0
       0     .09       0  173.28     .05       0  200.16    .075       0
Bank Sta=173.28,200.16
Exp/Cntr=0.5,0.3

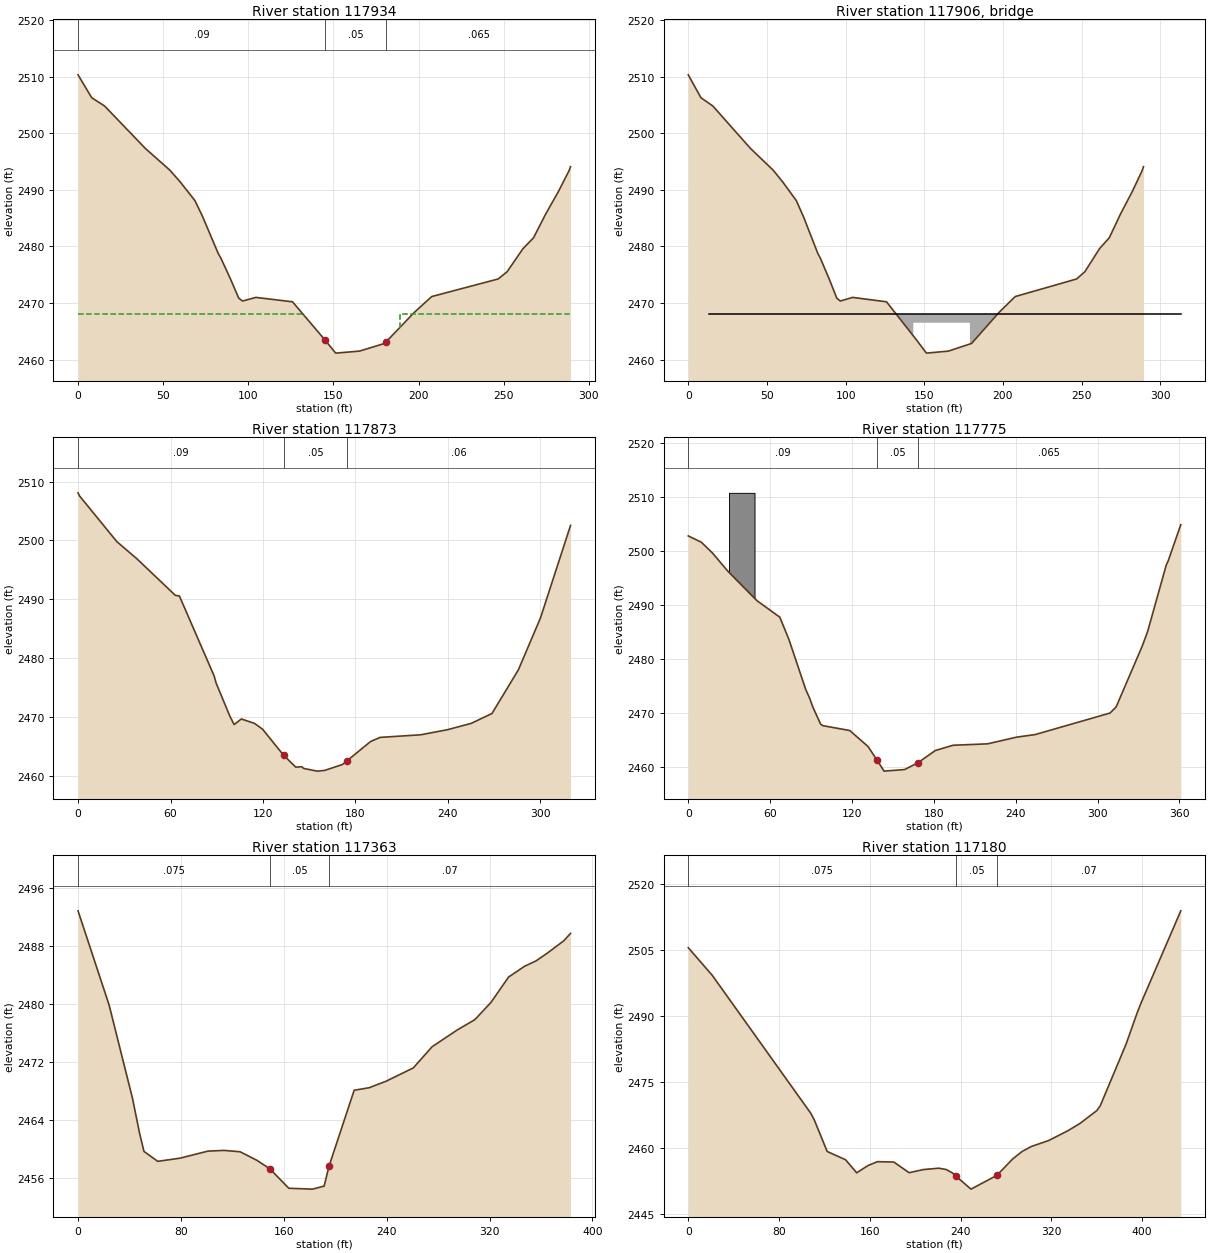
Type RM Length L Ch R = 1 ,117934  ,70.18,61.11,60.79
BEGIN DESCRIPTION:
117856.5
END DESCRIPTION:
XS GIS Cut Line= 6
  933329.2897313  806052.3356039  933294.3499803  806093.3517888
  933273.0829737  806122.2140817  933244.2196567  806166.2679715
  933227.5102316  806201.2077225  933207.7620774  806307.5437795
#Sta/Elev= 30
       0 2510.37    8.03 2506.32   15.62 2504.85   39.52 2497.35   53.88 2493.52
   59.96 2491.44   68.68 2488.11   73.25 2485.24   82.21 2478.85   83.96 2477.91
   89.56 2474.24   94.39 2470.86    96.6 2470.35   104.5 2470.99  125.99 2470.21
  144.91 2463.51  151.34 2461.13  165.37 2461.49  180.11 2462.85  181.13 2463.18
  197.39  2468.3  207.76 2471.14  246.79 2474.25  252.03 2475.53  261.38 2479.62
  267.56 2481.54  274.67 2485.73  282.22 2489.75  288.38 2493.38   289.3 2494.12
#Mann= 3 , 0 , 0
       0     .09       0  144.91     .05       0  181.13    .065       0
#XS Ineff= 2 , 0
       0     133    2468     189       0    2468
Permanent Ineff=
       F       F
Bank Sta=144.91,181.13
Exp/Cntr=0.5,0.3

Type RM Length L Ch R = 3 ,117906  ,,,
BEGIN DESCRIPTION:
117827  FBSTR_5038
END DESCRIPTION:
Bridge Culvert--1,0,-1,-1, 0
Deck Dist Width WeirC Skew NumUp NumDn MinLoCord MaxHiCord MaxSubmerge Is_Ogee
23,15,2.8,0, 6, 6, , , 0.95, 0, 1,1,,
      13     143     143     179     179     313
    2468    2468    2468    2468    2468    2468
                  2466.5  2466.5
       6     136     136     172     172     306
    2468    2468    2468    2468    2468    2468
                  2466.5  2466.5
BR Coef=-1 , 0 , 0 ,, 0 ,,,0.8,0,,0,
WSPro=,,,, 1 ,,,, 0 ,,,, 0 ,,,,-1 ,-1 ,-1 , 0 , 0 , 0 , 0 , 0
BC Design=,, 0 ,, 0 ,,,,,,

Type RM Length L Ch R = 1 ,117873  ,74.79,98.79,99.41
BEGIN DESCRIPTION:
117795.4
END DESCRIPTION:
XS GIS Cut Line= 6
  933257.8924011  806006.7628617  933195.6092096  806117.6565003
  933183.4563418  806157.1538327   933171.303474   806187.534978
  933153.0741723  806266.5286188   933145.478886  806302.9872222
#Sta/Elev= 30
       0 2508.08     .87 2507.59   25.17 2499.79    38.1  2496.9   63.11 2490.67
   65.77 2490.56   88.37 2476.93   89.56 2475.79   98.51 2470.14  101.29 2468.72
  105.96 2469.67  114.48 2468.92   119.7 2467.94  133.32 2463.53  141.23 2461.49
  145.13 2461.56  146.49 2461.26  155.14 2460.81  160.04 2460.93   171.6 2461.94
  174.58 2462.58  189.87 2465.85  195.95 2466.54  222.28 2466.98  239.76 2467.85
  255.09 2468.92  268.57  2470.6  285.71 2478.02  300.05 2486.84  319.55 2502.55
#Mann= 3 , 0 , 0
       0     .09       0  133.32     .05       0  174.58     .06       0
#XS Ineff= 2 , 0
       0     121    2465     187       0    2465
Permanent Ineff=
       F       F
Bank Sta=133.32,174.58
Exp/Cntr=0.5,0.3

Type RM Length L Ch R = 1 ,117775  ,383.92,411.18,471.39
BEGIN DESCRIPTION:
117696.6
END DESCRIPTION:
XS GIS Cut Line= 6
  933215.3573638  805985.4958552  933174.3411789  806028.0298683
   933136.363723  806056.8931854   933078.638113  806128.2905156
  933063.4475404  806170.8255529  933057.3711065  806287.7956254
#Sta/Elev= 30
       0  2502.8    9.57 2501.63    17.7 2499.64   29.08 2496.23   50.37 2490.78
   67.07 2487.73   73.65 2483.68   86.04 2474.35   89.17 2472.57   91.15 2471.14
   97.01 2467.88   98.62  2467.6  118.39 2466.69  131.79 2463.72  138.292461.228
  143.54 2459.16  158.57 2459.45  168.34 2460.71  181.07 2462.98  194.09 2463.96
  219.34 2464.22  240.79 2465.47  254.08 2465.93  309.19 2469.94  313.65 2471.08
  332.71 2482.33  336.63 2484.99  350.37  2497.4  351.83  2498.2  361.02 2504.89
#Mann= 3 , 0 , 0
       0     .09       0  138.29     .05       0  168.34    .065       0
#Block Obstruct= 1 ,-1
   29.82   48.562510.794
Bank Sta=138.29,168.34
Exp/Cntr=0.3,0.1

Type RM Length L Ch R = 1 ,117363  ,237.83,183.2,145.59
BEGIN DESCRIPTION:
117285.5
END DESCRIPTION:
XS GIS Cut Line= 6
  932903.9424306  805769.7839879  932788.4912107  805850.2954569
   932735.322158  805892.8304942   932703.421136  805938.4032364
  932694.3069972  805983.9759786  932663.9248277  806049.2978991
#Sta/Elev= 30
       0 2492.82   24.13 2479.85   42.39 2466.94    47.9 2462.11   51.28 2459.65
   61.98 2458.28   79.37 2458.72     101 2459.69  113.54 2459.79  126.05  2459.6
  138.93 2458.44  149.08 2457.26   163.9 2454.57  182.35 2454.45  191.39 2454.87
  195.11 2457.57  214.72 2468.08  226.34 2468.43  239.47 2469.32  260.71 2471.16
  275.33 2474.08  294.67 2476.37  308.54 2477.81  321.12 2480.19  334.82 2483.69
  347.28 2485.18   356.1 2485.91  364.74 2486.96  377.67 2488.68     383 2489.71
#Mann= 3 , 0 , 0
       0    .075       0  149.08     .05       0  195.11     .07       0
Bank Sta=149.08,195.11
Exp/Cntr=0.3,0.1

Type RM Length L Ch R = 1 ,117180  ,187.34,284.55,333.97
BEGIN DESCRIPTION:
117102.3
END DESCRIPTION:
XS GIS Cut Line= 6
  932785.4524816  805616.3553121  932698.8645787   805645.217605
  932639.6190921  805696.8667811  932610.7567992  805769.7839879
  932578.8557773  805885.2352079  932534.8018875  805933.8466791
#Sta/Elev= 30
       0 2505.62   21.11 2499.33  107.98 2467.94  111.07 2466.42   122.4 2459.25
   138.6 2457.38  148.43  2454.4  158.34 2456.05  166.76 2456.94  181.15 2456.85
   194.6 2454.43  207.47 2455.15  220.81 2455.45  227.25 2455.15  232.98 2454.34
  235.862453.643  249.14 2450.69  271.95 2453.82  285.99 2457.58   294.2 2459.26
  302.43  2460.4  317.63 2461.75  334.29 2463.94  345.23 2465.64  359.94 2468.54
  363.01 2469.63  385.72 2483.62   395.8 2490.95  399.05 2493.06  434.02    2514
#Mann= 3 , 0 , 0
       0    .075       0  235.86     .05       0  271.95     .07       0
Bank Sta=235.86,271.95
Exp/Cntr=0.3,0.1

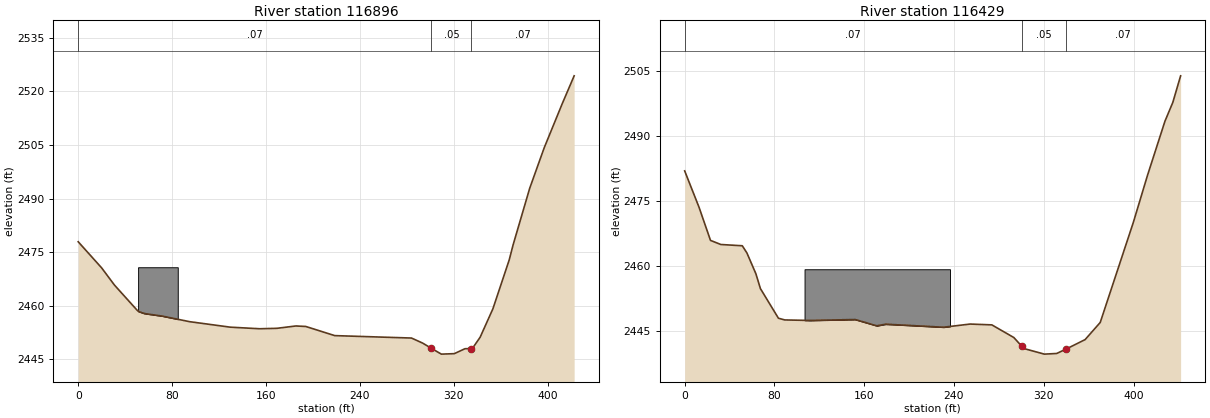
Type RM Length L Ch R = 1 ,116896  ,481.3,467.1,452.07
BEGIN DESCRIPTION:
116817.7
END DESCRIPTION:
XS GIS Cut Line= 6
  932666.9635568  805488.7512243  932584.9322112  805510.0182308
  932513.5338568  805535.8428189  932463.4045573  805569.2626933
  932396.5637844   805613.316583  932299.3418661  805686.2337899
#Sta/Elev= 30
       0 2477.92   19.97 2470.61   30.89  2465.8    50.2 2458.76   51.42  2458.4
   56.48 2457.83   71.65 2457.12   94.91 2455.56  129.67 2454.02  154.66 2453.58
  169.22  2453.7  185.43 2454.36  193.83 2454.22  218.54 2451.66  283.92 2450.98
  293.47 2449.56  300.97 2448.08  309.38 2446.48  320.37 2446.61  329.47 2447.99
  334.96 2448.04  335.78 2448.05   342.4  2451.2  353.24 2459.13  367.13 2472.78
  370.48 2477.04  384.66 2492.91  396.97  2504.2  412.31 2516.52   422.5 2524.35
#Mann= 3 , 0 , 0
       0     .07       0  300.97     .05       0  334.96     .07       0
#Block Obstruct= 1 ,-1
   51.03   84.812470.791
Bank Sta=300.97,334.96
Exp/Cntr=0.3,0.1

Type RM Length L Ch R = 1 ,116429  ,443.42,329.98,276.91
BEGIN DESCRIPTION:
116350.6
END DESCRIPTION:
XS GIS Cut Line= 6
  932379.8533351  805092.2662165   932302.379571  805118.0908046
  932191.4859324  805177.3362912  932138.3168798  805218.3514519
  932094.2640142  805260.8864892  932035.0185276  805348.9942687
#Sta/Elev= 30
       0 2481.84   12.78 2473.46   23.01  2465.8   32.24 2464.85   51.34 2464.56
   55.45 2462.91   63.47  2458.1   67.51 2454.67   83.55 2447.84   89.19 2447.44
  111.95 2447.32  151.87 2447.54  171.24 2446.08  179.15 2446.46  230.82 2445.76
  254.44 2446.49  273.76  2446.3   293.3 2443.39  300.25 2441.42  302.59 2440.82
  320.56 2439.55  331.54  2439.7  339.72 2440.69  356.91 2442.91  370.35 2446.86
  399.86 2469.96  412.53 2480.86  428.01 2493.29  435.02 2497.63  441.99 2503.78
#Mann= 3 , 0 , 0
       0     .07       0  300.25     .05       0  339.72     .07       0
#Block Obstruct= 1 ,-1
  106.82  236.44 2459.14
Bank Sta=300.25,339.72
Exp/Cntr=0.3,0.1