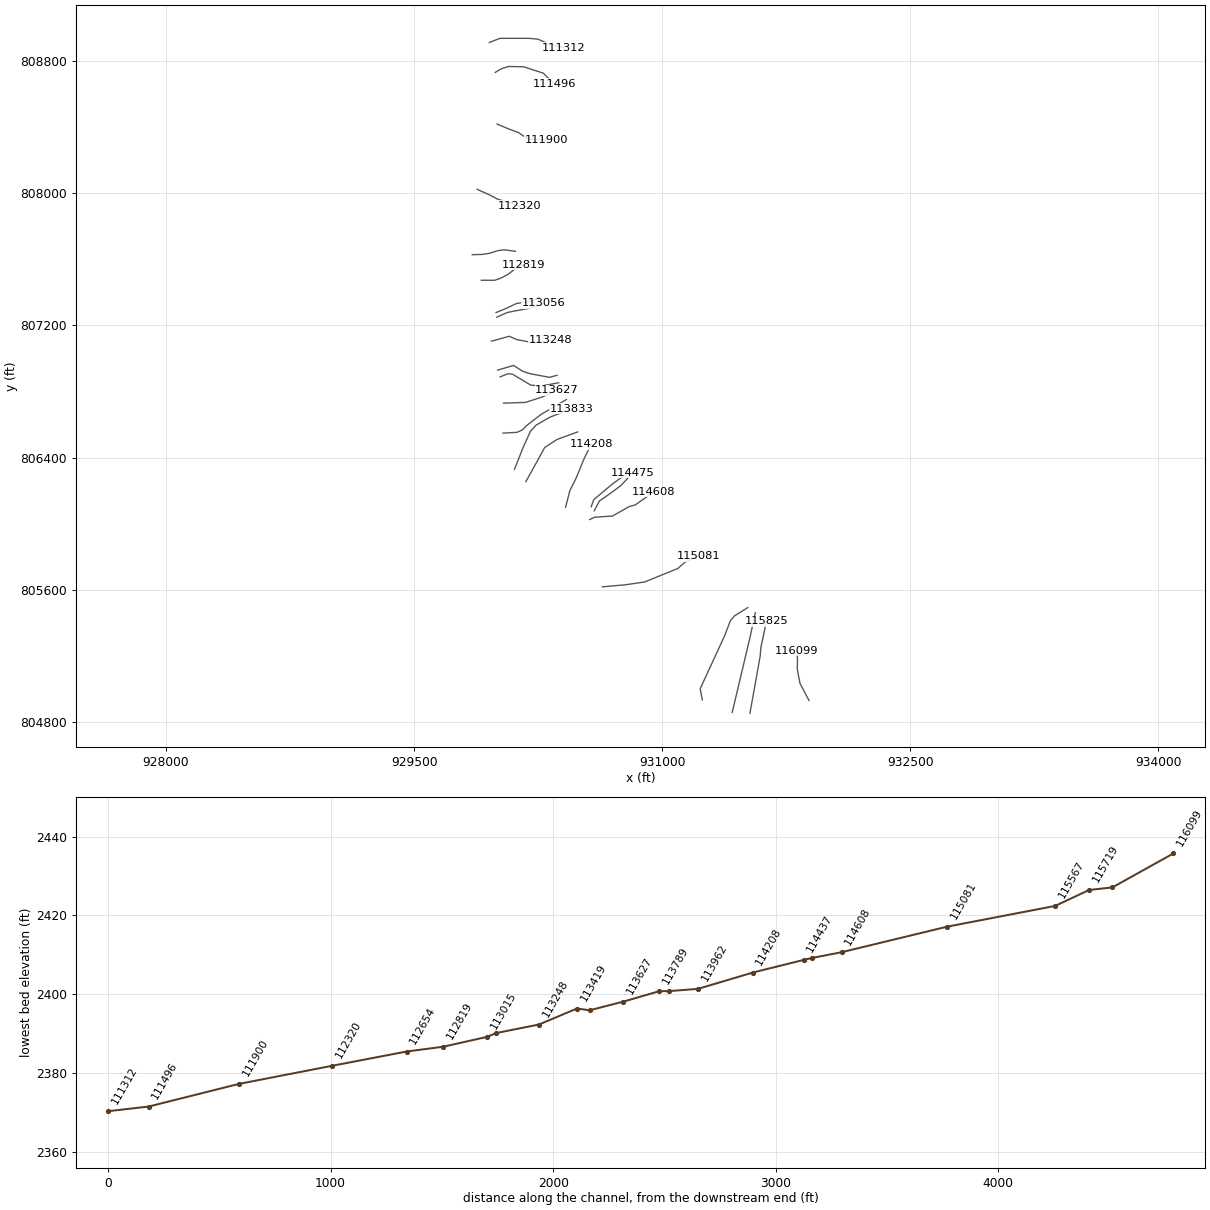
HEC-RAS study lds_big_laurel_crk.prj: lds_big_laurel_crk

--- lds_big_laurel_crk.g20 (geometry) --- (continued)

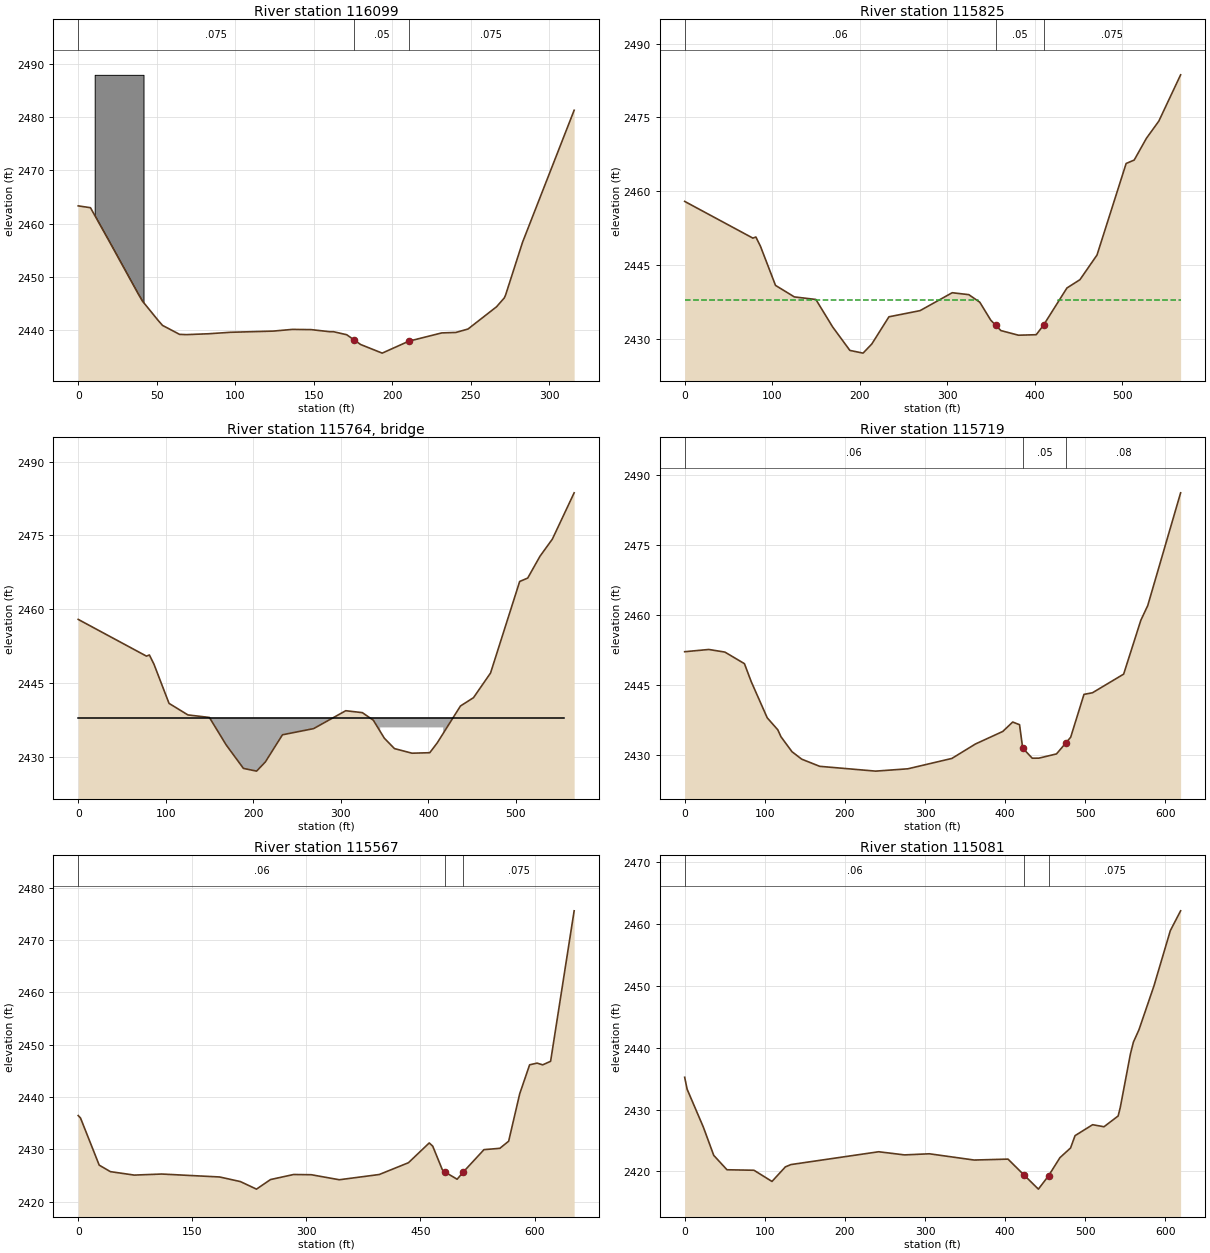
Type RM Length L Ch R = 1 ,116099  ,303.61,273.89,253.97
BEGIN DESCRIPTION:
116020.6
END DESCRIPTION:
XS GIS Cut Line= 6
  931887.6662857  804929.7234019  931832.9783805  805033.0217541
  931819.3066603  805102.9002319  931816.2689554  805125.6860909
  931817.7878079  805172.7787097   931814.750103  805230.5043197
#Sta/Elev= 29
       0 2463.34    7.81    2463      21 2456.04   38.08 2446.91   40.87  2445.5
   51.04 2441.82   53.73 2440.92   64.58 2439.24   68.86 2439.19   82.91 2439.35
   97.04 2439.63  124.21 2439.85  136.36 2440.17  148.49 2440.13   160.1 2439.74
  162.63 2439.74  171.09 2439.17  175.852438.187     180 2437.33  193.69 2435.72
  210.57 2437.95  231.58 2439.51  240.65  2439.6  248.36 2440.24  266.53 2444.41
  271.47 2446.07  272.28 2446.59  283.11 2456.51     316 2481.28
#Mann= 3 , 0 , 0
       0    .075       0  175.85     .05       0  210.57    .075       0
#Block Obstruct= 1 ,-1
    10.5    41.62487.924
Bank Sta=175.85,210.57
Exp/Cntr=0.5,0.3

Type RM Length L Ch R = 1 ,115825  ,98.38,105.67,97.52
XS GIS Cut Line= 4
  931530.1726676  804851.8327983  931592.1547514  805198.3728582
  931596.6631725  805252.4667415  931630.4712094  805409.1133771
#Sta/Elev= 30
       0 2457.94   77.94 2450.48   81.33 2450.71   86.55 2448.84  103.77 2440.88
  125.29 2438.54  149.87 2438.02  169.08 2432.43  188.75 2427.67  203.79 2427.12
  213.79 2428.98  233.35  2434.5  268.92 2435.75  305.64 2439.39  324.58    2439
  337.15 2437.46  349.71 2433.81  355.12 2432.82  361.26  2431.7  381.34 2430.76
  401.61 2430.86  410.08 2432.84  436.69 2440.35  451.57 2442.04  471.06 2447.05
  504.33 2465.64  513.54 2466.34  527.51 2470.76  541.68 2474.25  566.57 2483.65
#Mann= 3 , 0 , 0
       0     .06       0  355.12     .05       0  410.08    .075       0
#XS Ineff= 2 , 0
       0     335    2438     427       0    2438
Permanent Ineff=
       F       F
Bank Sta=355.12,410.08
Exp/Cntr=0.5,0.3

Type RM Length L Ch R = 3 ,115764  ,,,
Bridge Culvert--1,0,-1,-1, 0
Deck Dist Width WeirC Skew NumUp NumDn MinLoCord MaxHiCord MaxSubmerge Is_Ogee
44,12,2.6,0, 6, 6, , , 0.95, 0, 1,1,,
       0     345     345     417     417     555
    2438    2438    2438    2438    2438    2438
                    2436    2436
       0     410     410     482     482     620
    2438    2438    2438    2438    2438    2438
                    2436    2436
BR Coef=-1 , 0 , 0 ,, 0 ,,,0.8,-1,,0,
WSPro=,,,, 1 ,,,, 0 ,,,, 0 ,,,,-1 ,-1 ,-1 , 0 , 0 , 0 , 0 , 0
BC Design=,, 0 ,, 0 ,,,,,,

Type RM Length L Ch R = 1 ,115719  ,191,151.6,94.33
XS GIS Cut Line= 3
  931423.1114942  804857.4678125  931532.1974628  805318.6120992
  931562.8541114  805460.3907774
#Sta/Elev= 30
       0 2452.03   30.13 2452.51   50.19 2451.95   74.57 2449.47   83.09  2445.6
  103.04 2437.86   116.2  2435.3  120.17 2433.81  133.93  2430.6  146.09    2429
  168.51 2427.47  238.39 2426.44   278.6 2426.94  333.46 2429.16  362.83 2432.25
  396.94 2434.94  409.38 2436.96  417.89 2436.39  421.84 2431.38  433.77 2429.21
  442.04 2429.22  464.03 2430.13  476.11 2432.56  481.74 2433.71  498.33 2442.89
  508.89 2443.23  547.84 2447.23  569.28 2458.77  577.88 2461.91  618.93 2486.08
#Mann= 3 , 0 , 0
       0     .06       0  421.84     .05       0  476.11     .08       0
#XS Ineff= 2 , 0
       0     395    2433     497       0    2433
Permanent Ineff=
       F       F
Bank Sta=421.84,476.11
Exp/Cntr=0.5,0.3

Type RM Length L Ch R = 1 ,115567  ,651.69,486.48,462.07
BEGIN DESCRIPTION:
115489.5
END DESCRIPTION:
XS GIS Cut Line= 6
  931242.5329471  804933.5282143  931229.3302993   805000.420196
  931377.2499345   805321.649804  931412.1886613  805412.7963126
  931436.4943969  805441.6586055  931517.0068901  805491.7889291
#Sta/Elev= 30
       0 2436.47    3.03    2436   27.61    2427    42.3 2425.76   73.73  2425.1
  109.77  2425.3  185.96 2424.74  213.26 2423.86  234.38 2422.42  252.88 2424.25
  283.16 2425.21  306.46 2425.17  343.31 2424.21  395.83 2425.21  434.19 2427.46
  461.56 2431.24  466.15 2430.62  478.63 2426.17  481.95  2425.7  498.25 2424.31
  506.14 2425.66  533.51 2429.96  554.37 2430.21  565.96 2431.57  580.51 2440.63
  593.54 2446.16  603.35 2446.48  610.72 2446.15  621.12 2446.83  652.08 2475.56
#Mann= 3 , 0 , 0
       0     .06       0  481.95     .05       0  506.14    .075       0
Bank Sta=481.95,506.14
Exp/Cntr=0.3,0.1

Type RM Length L Ch R = 1 ,115081  ,442.88,472.96,479.55
BEGIN DESCRIPTION:
115003.0
END DESCRIPTION:
XS GIS Cut Line= 6
  930638.9688483  805617.8741645  930777.2059273  805630.0270323
  930892.6571472  805646.7364574  931094.6972943   805728.767803
  931138.7511841  805768.2651355  931217.7448248  805803.2038623
#Sta/Elev= 30
       0 2435.22    3.05  2433.3   23.37 2427.15   36.31  2422.6   52.79 2420.28
   86.49  2420.2  108.96 2418.39  125.73 2420.75  132.66 2421.12  242.18 2423.19
  274.32 2422.68  305.37 2422.86   361.4 2421.85  403.58    2422  423.67 2419.42
   441.5 2417.15  454.21 2419.31  468.36 2422.23  481.65  2423.8  487.25 2425.79
  509.17 2427.56  523.38 2427.23  541.06 2428.97  543.67 2430.32  556.38    2439
  560.13 2440.92  566.97 2442.88   585.7 2449.97  606.18 2458.92  619.03 2462.12
#Mann= 3 , 0 , 0
       0     .06       0  423.67     .05       0  454.21    .075       0
Bank Sta=423.67,454.21
Exp/Cntr=0.3,0.1

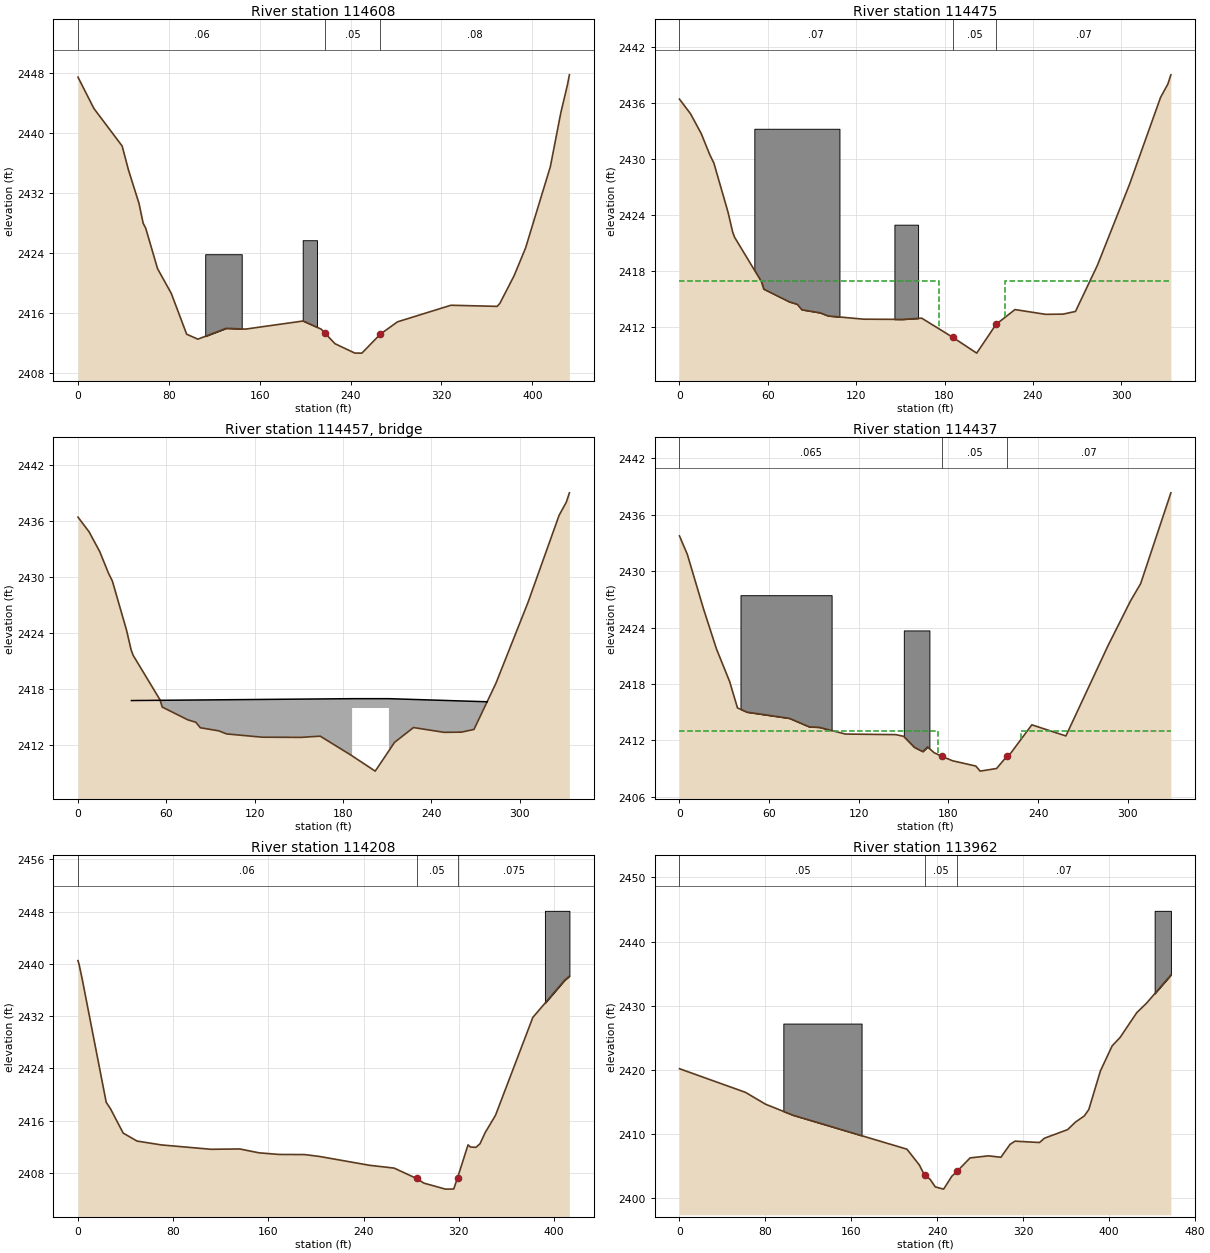
Type RM Length L Ch R = 1 ,114608  ,120.54,132.6,166.33
BEGIN DESCRIPTION:
114530.0
END DESCRIPTION:
XS GIS Cut Line= 6
    930561.49406  806024.9921635  930590.3573771  806038.6638837
  930699.7321631    806046.25917  930801.5116629    806103.98478
  930836.4514139   806113.099943  930948.8639048  806192.0925595
#Sta/Elev= 30
       0 2447.46      14 2443.29    38.9 2438.28   44.43  2435.1   53.75 2430.62
   57.39 2427.99   59.64 2427.33   70.06 2421.94    82.1 2418.66   95.68 2413.21
  105.55 2412.55  130.53    2414  147.38 2413.89  198.18 2414.97  214.06 2413.89
  217.292413.376  226.31 2411.94  243.64  2410.7  249.91 2410.69   266.2 2413.22
  281.27 2414.86  328.33 2417.07  369.01 2416.92  371.36 2417.31  383.99 2421.02
     394 2424.69  415.83 2435.53  425.04 2442.71  430.98  2446.5  432.61 2447.77
#Mann= 3 , 0 , 0
       0     .06       0  217.29     .05       0   266.2     .08       0
#Block Obstruct= 2 ,-1
  197.82  210.442425.734  112.01  144.142423.868
Bank Sta=217.29,266.2
Exp/Cntr=0.5,0.3

Type RM Length L Ch R = 1 ,114475  ,29.76,38.06,22.2
BEGIN DESCRIPTION:
114397.4
END DESCRIPTION:
XS GIS Cut Line= 5
  930588.8385246   806078.160192  930620.7395466  806137.4056786
  930686.0604429  806182.9784208  930751.3813392  806231.5888678
  930822.7786695  806309.0636561
#Sta/Elev= 30
       0 2436.41    7.53 2434.84   14.78 2432.72   20.62 2430.45   23.34 2429.58
   32.99 2424.31   36.11  2422.2   37.41 2421.64    55.7 2416.87   57.21 2416.09
   74.69 2414.72   79.98 2414.47   83.07 2413.88   95.58 2413.55  100.89 2413.22
  125.07 2412.87  151.56 2412.85  164.49 2412.98  185.61 2410.93  201.84 2409.24
  215.01 2412.32  227.84  2413.9  248.59 2413.39  260.44 2413.41  268.93  2413.7
  283.85 2418.65  305.61 2427.29  326.74 2436.61  331.62 2438.01  333.72 2439.01
#Mann= 3 , 0 , 0
       0     .07       0  185.61     .05       0  215.01     .07       0
#XS Ineff= 2 , 0
       0  176.16 2416.99  221.16       0 2416.99
Permanent Ineff=
       F       F
#Block Obstruct= 2 ,-1
   50.83  108.642433.241  145.96  162.032422.981
Bank Sta=185.61,215.01
Exp/Cntr=0.5,0.3

Type RM Length L Ch R = 3 ,114457  ,,,
Node Photo=H:\PROJ\06-0741\CE\GIS\DATA\FRENCH_BROAD_RIVER\SHAPEFILES\survey_data\photos\FBSTR_1251.JPG
BEGIN DESCRIPTION:
114381.5  FBSTR_1251
END DESCRIPTION:
Bridge Culvert--1,0,-1,-1, 0
Deck Dist Width WeirC Skew NumUp NumDn MinLoCord MaxHiCord MaxSubmerge Is_Ogee
9,14,2.6,0, 7, 7, , , 0.95, 0, 1,1,,
   36.33  186.16  186.16  198.66  211.16  211.16  277.86
 2416.79 2416.99 2416.99 2416.99 2416.99 2416.99 2416.66
                 2415.99 2415.99 2415.99
   36.07  188.75  188.75  201.25  213.75  213.75  271.17
 2416.93 2416.99 2416.99 2416.99 2416.99 2416.99 2416.75
                 2415.99 2415.99 2415.99
BR Coef=-1 , 0 , 0 ,, 0 ,,,0.8,0,,0,
WSPro=,,,, 1 ,,,, 0 ,,,, 0 ,,,,-1 ,-1 ,-1 , 0 , 0 , 0 , 0 , 0
BC Design=,, 0 ,, 0 ,,,,,,

Type RM Length L Ch R = 1 ,114437  ,162.02,228.82,276.88
BEGIN DESCRIPTION:
114359.4
END DESCRIPTION:
XS GIS Cut Line= 6
  930570.6092229  806102.4659276  930585.7997956  806145.0009649
  930692.1368768  806234.6275968  930745.3049053  806274.1239051
  930787.8399426  806302.9872222  930804.5503919  806324.2542288
#Sta/Elev= 30
       0 2433.74    5.25 2431.78    16.2 2425.93   24.78 2421.72   33.58 2418.26
   38.82 2415.46   45.17 2415.01   73.55 2414.35   86.93 2413.44    93.4  2413.4
  111.09 2412.68  144.81 2412.62  150.03 2412.44  157.12 2411.28   162.8 2410.82
  166.09 2411.31  170.44  2410.7  175.852410.296  182.78 2409.84  198.36 2409.28
  201.25 2408.74  212.26 2409.02  219.05  2410.3   220.6 2410.41  235.83 2413.66
  258.64 2412.48  286.69 2422.03  301.88 2426.83  308.67 2428.67  328.92 2438.32
#Mann= 3 , 0 , 0
       0    .065       0  175.85     .05       0  219.05     .07       0
#XS Ineff= 2 , 0
       0  173.35    2413  228.75       0    2413
Permanent Ineff=
       F       F
#Block Obstruct= 2 ,-1
   40.83  101.822427.439  150.14  167.282423.695
Bank Sta=175.85,219.05
Exp/Cntr=0.5,0.3

Type RM Length L Ch R = 1 ,114208  ,258.49,246.22,152.68
BEGIN DESCRIPTION:
114130.5
END DESCRIPTION:
XS GIS Cut Line= 5
  930415.6606705  806099.4282227  930441.4852585  806199.6878459
  930479.4627144  806275.6427576  930526.5553332  806391.0950017
  930570.6092229  806480.7216336
#Sta/Elev= 30
       0 2440.51    1.01 2439.87    3.54  2437.7   23.72 2418.83   27.46 2417.79
   37.99 2414.11   49.62 2412.89   70.03  2412.3  111.73 2411.63     136 2411.68
  152.09 2411.09  168.85 2410.84  190.47 2410.82  202.65 2410.54  245.02 2409.18
  265.71 2408.75  284.57 2407.16  290.71 2406.45  308.86 2405.53  315.79 2405.55
  319.062407.291  327.82 2412.31  329.83 2411.98  334.44 2411.93  337.89 2412.48
  342.21 2414.18  350.92 2416.84  382.27 2431.82  408.87 2437.49  413.01 2438.14
#Mann= 3 , 0 , 0
       0     .06       0  284.57     .05       0  319.06    .075       0
#Block Obstruct= 1 ,-1
  392.43  413.012448.141
Bank Sta=284.57,319.06
Exp/Cntr=0.3,0.1

Type RM Length L Ch R = 1 ,113962  ,112.46,129.57,144.03
BEGIN DESCRIPTION:
113884.3
END DESCRIPTION:
XS GIS Cut Line= 5
  930175.6440918   806254.375751  930254.6367083  806397.1704114
  930289.5764593  806460.9734795  930364.0114944  806509.5839265
  930488.5778773  806555.1566687
#Sta/Elev= 30
       0 2420.18   61.47 2416.49   80.05 2414.65  105.62 2412.93  211.74 2407.63
  223.24 2405.18  227.08 2403.93  228.97 2403.62  233.49 2402.89   238.1 2401.75
  245.89  2401.4  253.55 2403.41  258.482404.185  270.53 2406.27  287.68 2406.59
  299.21 2406.37  307.71 2408.38  312.33 2408.88  335.15 2408.67  339.76 2409.34
  361.31 2410.68  368.74 2411.87  376.89 2412.82  381.06 2413.82  391.84 2419.83
  402.81 2423.75  410.12 2425.04  425.69 2428.92  434.65 2430.37  457.47  2434.8
#Mann= 3 , 0 , 0
       0     .05       0  228.97     .05       0  258.48     .07       0
#Block Obstruct= 2 ,-1
   96.69   169.52427.218  442.33  457.472444.801
Bank Sta=228.97,258.48
Exp/Cntr=0.5,0.3

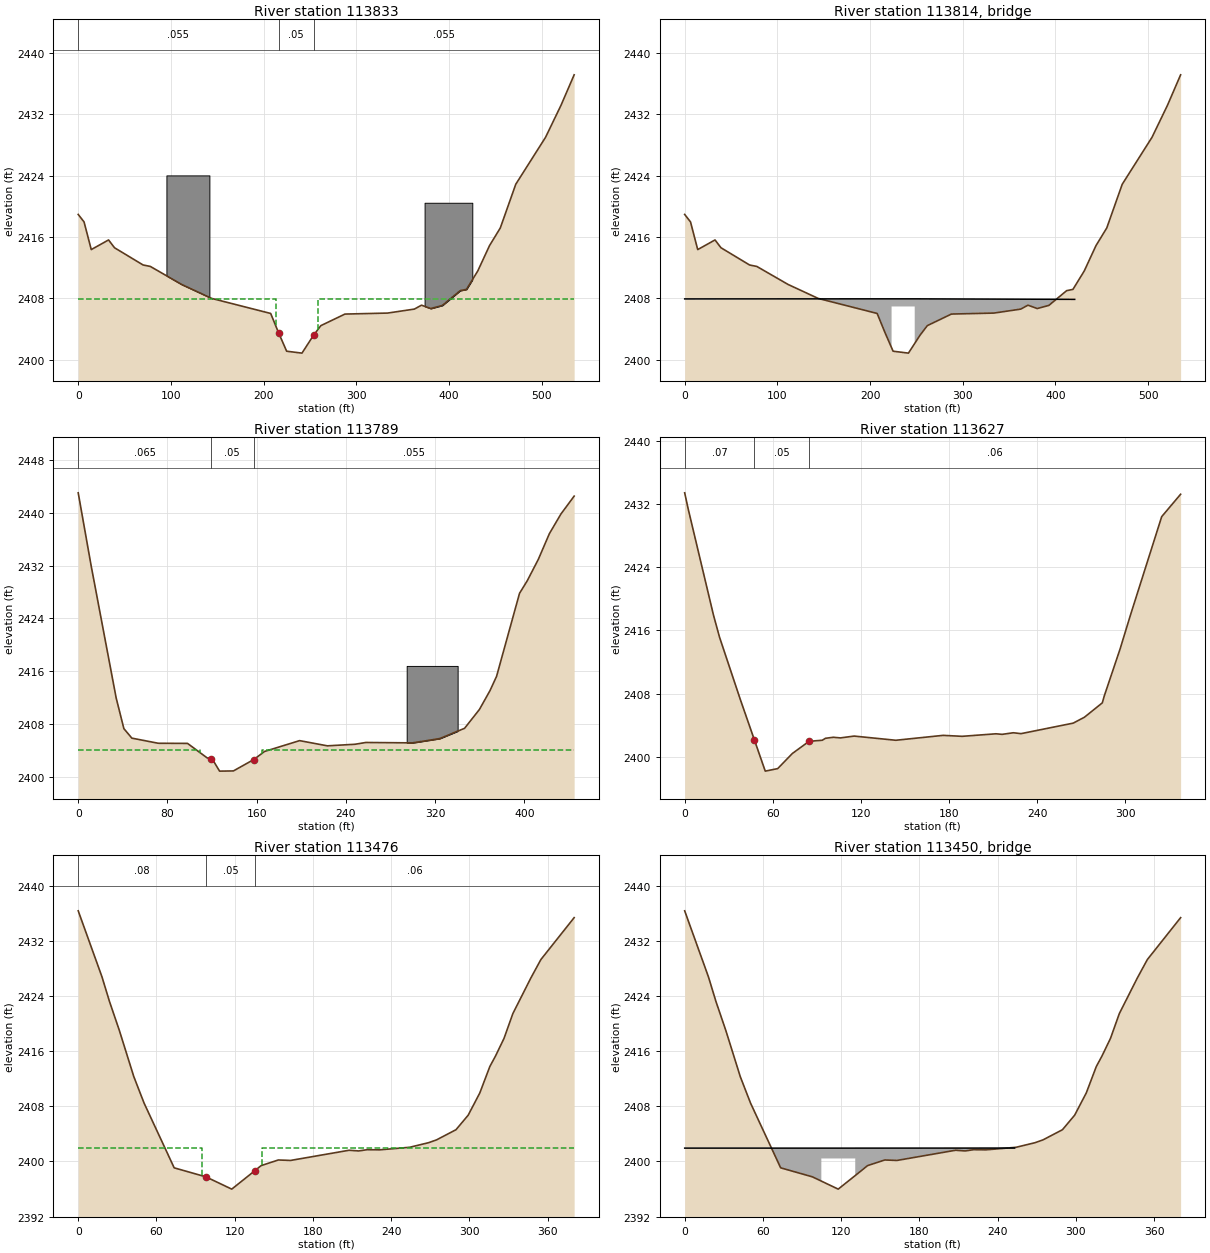
Type RM Length L Ch R = 1 ,113833  ,140.15,43.43,50.25
BEGIN DESCRIPTION:
113754.7
END DESCRIPTION:
XS GIS Cut Line= 6
  930106.6771303  806329.0524915  930159.4109083  806461.9945826
  930203.1606179  806558.8693053  930237.5360481  806596.3694953
  930318.7859478  806643.2449889  930450.0361007  806694.8071101
#Sta/Elev= 30
       0 2418.95    6.31 2417.97   14.07 2414.36   32.74 2415.62   39.16  2414.6
      70 2412.35   77.82 2412.16  111.51 2409.81  144.07 2407.98  207.63 2406.02
  216.162403.499  224.86 2401.09  241.38 2400.84  253.91 2403.18  261.77 2404.43
  287.75 2405.94  333.77 2406.07  362.61 2406.59  370.33  2407.1  380.35 2406.66
  392.89 2407.07  412.08    2409  418.83 2409.16  431.04 2411.57  443.71 2414.88
  455.32 2417.18  472.01 2422.89  504.18 2429.03  520.77 2433.19     535 2437.18
#Mann= 3 , 0 , 0
       0    .055       0  216.16     .05       0  253.91    .055       0
#XS Ineff= 2 , 0
       0  213.16 2407.93  258.16       0 2407.93
Permanent Ineff=
       F       F
#Block Obstruct= 2 ,-1
  373.64  425.132420.477   95.15  141.522424.049
Bank Sta=216.16,253.91
Exp/Cntr=0.5,0.3

Type RM Length L Ch R = 3 ,113814  ,,,
Node Photo=H:\PROJ\06-0741\CE\GIS\DATA\FRENCH_BROAD_RIVER\SHAPEFILES\survey_data\photos\FBSTR_1254.JPG
BEGIN DESCRIPTION:
113738.5  FBSTR_1254
END DESCRIPTION:
Bridge Culvert--1,0,-1,-1, 0
Deck Dist Width WeirC Skew NumUp NumDn MinLoCord MaxHiCord MaxSubmerge Is_Ogee
9,9,2.6,0, 7, 7, , , 0.95, 0, 1,1,,
       0  223.16  223.16  245.16  248.16  248.16  420.76
 2407.92 2407.93 2407.93 2407.93 2407.93 2407.93 2407.86
                 2406.93 2406.93 2406.93
   12.03   124.5   124.5     137   149.5   149.5  320.19
 2407.88 2407.93 2407.93 2407.93 2407.93 2407.93  2407.7
                 2406.93 2406.93 2406.93
BR Coef=-1 , 0 , 0 ,, 0 ,,,0.8,0,,0,
WSPro=,,,, 1 ,,,, 0 ,,,, 0 ,,,,-1 ,-1 ,-1 , 0 , 0 , 0 , 0 , 0
BC Design=,, 0 ,, 0 ,,,,,,

Type RM Length L Ch R = 1 ,113789  ,181.6,162.32,83.29
BEGIN DESCRIPTION:
113711.3
END DESCRIPTION:
XS GIS Cut Line= 6
  930037.5360589   806547.932134  930121.9107183  806552.6197857
  930153.1613887  806566.6827411  930187.5357948  806599.4942551
  930268.7856944  806661.9945718  930420.3483223   806751.056883
#Sta/Elev= 30
       0 2443.08   11.59 2432.01   34.01 2411.95   40.92 2407.28   48.09 2405.83
   71.78 2405.05   98.02 2405.03  115.58 2402.83   118.8 2402.69  120.74  2402.5
  126.75 2400.82  139.14 2400.85  157.31 2402.57   167.1 2403.81  198.49 2405.45
  223.38 2404.66  248.23  2404.9  257.84 2405.17  299.69 2405.11  324.09 2405.76
  346.37 2407.32  359.69 2410.18  369.15 2413.04  375.06 2415.21  395.65 2427.82
  402.61 2429.74  412.48 2432.97  422.42 2436.88  432.79 2439.87  444.62 2442.58
#Mann= 3 , 0 , 0
       0    .065       0   118.8     .05       0  157.31    .055       0
#XS Ineff= 2 , 0
       0   109.5    2404   164.5       0    2404
Permanent Ineff=
       F       F
#Block Obstruct= 1 ,-1
  294.48  340.162416.797
Bank Sta=118.8,157.31
Exp/Cntr=0.5,0.3

Type RM Length L Ch R = 1 ,113627  ,175.43,150.42,48.34
BEGIN DESCRIPTION:
113549.0
END DESCRIPTION:
XS GIS Cut Line= 5
  930040.6608187  806729.1825403  930093.7858318  806730.7444081
  930173.4738636  806733.8701921  930275.0362382  806766.6827303
  930364.0985493  806807.3076801
#Sta/Elev= 30
       0 2433.43    2.34 2431.43    19.6 2417.94   23.69 2415.16   38.03 2407.16
    47.52402.094   54.84 2398.17   63.31 2398.49   73.31 2400.41   84.68 2401.95
   93.62 2402.08   95.83 2402.33  101.19 2402.46  106.01 2402.38  115.32 2402.61
  143.69 2402.08  175.84  2402.7   188.9 2402.58  211.84  2402.9  216.03 2402.83
  223.67 2403.03  228.95 2402.92   264.4 2404.25  272.06    2405  284.23 2406.82
  285.59 2407.71  296.33 2413.65  303.36 2417.93  324.64 2430.41  337.52 2433.25
#Mann= 3 , 0 , 0
       0     .07       0    47.5     .05       0   84.68     .06       0
Bank Sta=47.5,84.68
Exp/Cntr=0.5,0.3

Type RM Length L Ch R = 1 ,113476  ,50.81,57.77,61.12
BEGIN DESCRIPTION:
113398.6
END DESCRIPTION:
XS GIS Cut Line= 6
  930020.3483438  806888.5575797  930067.2238374  806907.3071626
  930095.3487238  806904.1824028  930204.7235099  806838.5573264
  930265.6609346  806832.3067826  930373.4738529  806852.6192575
#Sta/Elev= 30
       0 2436.37   18.23 2426.79   23.94 2423.24   31.54 2419.02   42.64 2412.31
   50.49 2408.48   73.59 2399.08   97.95 2397.77  117.73 2395.99  135.42 2398.66
  140.25  2399.4  153.47 2400.22  162.78 2400.15  207.74 2401.63  215.02 2401.53
  221.56 2401.71  231.12 2401.69  254.13 2402.06  268.71 2402.73  274.81 2403.14
  289.68 2404.61  299.04 2406.72  307.96 2409.95  315.62 2413.77  319.98  2415.3
  326.53 2417.87  333.29 2421.46  347.05 2426.61  354.78  2429.3  380.29 2435.38
#Mann= 3 , 0 , 0
       0     .08       0   97.95     .05       0  135.42     .06       0
#XS Ineff= 2 , 0
       0    94.8 2401.94   140.8       0 2401.94
Permanent Ineff=
       F       F
Bank Sta=97.95,135.42
Exp/Cntr=0.5,0.3

Type RM Length L Ch R = 3 ,113450  ,,,
Node Photo=H:\PROJ\06-0741\CE\GIS\DATA\FRENCH_BROAD_RIVER\SHAPEFILES\survey_data\photos\FBSTR_1260A.JPG
BEGIN DESCRIPTION:
113365.6  FBSTR_1260A
END DESCRIPTION:
Bridge Culvert--1,0,-1,-1, 0
Deck Dist Width WeirC Skew NumUp NumDn MinLoCord MaxHiCord MaxSubmerge Is_Ogee
16,18,2.6,0, 7, 7, , , 0.95, 0, 1,1,,
       0   104.8   104.8   117.8   130.8   130.8  253.01
 2401.94 2401.94 2401.94 2401.94 2401.94 2401.94 2401.95
                 2400.44 2400.44 2400.44
       0   109.2   109.2   122.2   135.2   135.2  282.03
 2401.94 2401.94 2401.94 2401.94 2401.94 2401.94 2401.85
                 2400.44 2400.44 2400.44
BR Coef=-1 , 0 , 0 ,, 0 ,,,0.8,0,,0,
WSPro=,,,, 1 ,,,, 0 ,,,, 0 ,,,,-1 ,-1 ,-1 , 0 , 0 , 0 , 0 , 0
BC Design=,, 0 ,, 0 ,,,,,,

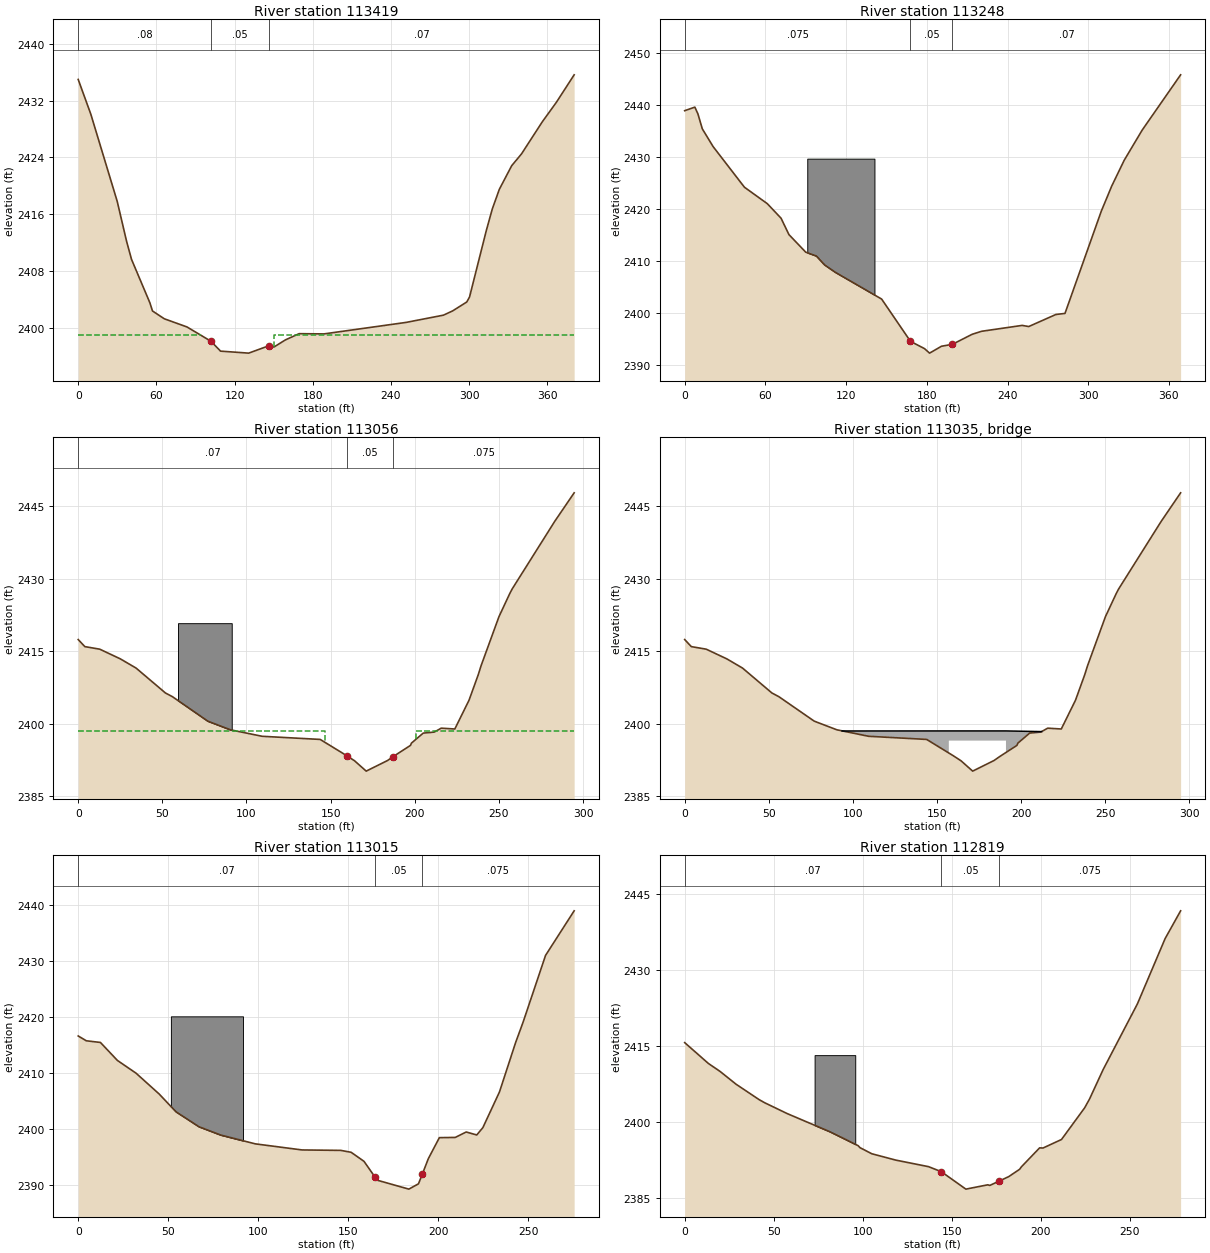
Type RM Length L Ch R = 1 ,113419  ,178.09,170.38,210.2
BEGIN DESCRIPTION:
113340.8
END DESCRIPTION:
XS GIS Cut Line= 6
  930004.7235207  806929.1825295  930101.5982434   806957.307416
  930157.8490405  806921.3701179  930201.5987501  806907.3071626
  930318.7859478  806885.4317957  930364.0985493  806897.9318591
#Sta/Elev= 30
       0 2434.99     9.7 2430.08   29.92 2417.82   37.17 2412.15   40.93 2409.63
   55.02 2403.51   57.02 2402.36   66.08 2401.26   83.48 2400.11  101.75 2398.11
  109.28  2396.7  130.86 2396.42  146.83 2397.49  150.26 2397.28  159.09 2398.29
  169.58 2399.16  188.66 2399.13  251.71 2400.75  280.35 2401.77   287.4 2402.37
  298.28 2403.63  300.38 2404.33  313.19 2413.65  317.84 2416.73  323.26 2419.51
  332.76 2422.84  340.21 2424.48   356.2 2429.01  367.09 2431.78  380.68 2435.64
#Mann= 3 , 0 , 0
       0     .08       0  101.75     .05       0  146.83     .07       0
#XS Ineff= 2 , 0
       0    94.2    2399   150.2       0    2399
Permanent Ineff=
       F       F
Bank Sta=101.75,146.83
Exp/Cntr=0.5,0.3

Type RM Length L Ch R = 1 ,113248  ,145.02,192.32,217.82
BEGIN DESCRIPTION:
113170.4
END DESCRIPTION:
XS GIS Cut Line= 6
  929967.2233307  807104.1823921  930075.0362489  807133.8701705
  930121.9107183  807113.5576956  930204.7235099  807097.9318483
  930292.2239533  807101.0576323  930325.0364915  807108.8700438
#Sta/Elev= 30
       0 2438.89    7.57 2439.57    9.84 2438.28    13.1 2435.41   21.19 2431.98
   44.41 2424.21   61.46 2421.04   71.67 2418.25   77.51 2415.11   90.01 2411.74
   97.84 2411.01  103.97  2409.3  111.91 2407.89  146.44 2402.74  167.87 2394.63
  178.31 2393.23  182.07 2392.37  190.91 2393.69  199.05 2394.06  213.68 2395.98
  220.71 2396.56   250.9 2397.69  255.77 2397.47  275.93 2399.78  282.73 2399.99
  309.72 2419.61  317.48 2424.43  326.76 2429.38  340.15 2435.18  368.69 2445.77
#Mann= 3 , 0 , 0
       0    .075       0  167.87     .05       0  199.05     .07       0
#Block Obstruct= 1 ,-1
   91.13  141.082429.687
Bank Sta=167.87,199.05
Exp/Cntr=0.5,0.3

Type RM Length L Ch R = 1 ,113056  ,25.95,41.23,40.86
BEGIN DESCRIPTION:
112978.1
END DESCRIPTION:
XS GIS Cut Line= 6
  930000.0358689  807249.4944762  930062.5361856  807277.6193626
  930107.8487872  807286.9946662  930209.4111617  807305.7442491
  930225.0359848  807310.4319009  930281.2857577  807332.3072678
#Sta/Elev= 30
       0 2417.44    3.95 2415.98    12.8 2415.45   25.06 2413.44   34.38 2411.54
   51.86 2406.38   56.03 2405.61   77.02 2400.55   90.47 2398.76  109.34 2397.42
  143.82 2396.77  159.452393.435  164.24 2392.35  171.16 2390.21  183.87 2392.41
   187.2 2393.22  197.49 2395.54  198.03    2396  205.06 2398.08  211.62 2398.29
  215.75  2399.1  223.83 2398.93  232.29  2404.9  237.71 2410.12  239.44 2412.03
  250.08 2422.19   256.4  2426.9  257.89  2427.9  283.16 2441.88  294.75 2447.81
#Mann= 3 , 0 , 0
       0     .07       0  159.45     .05       0   187.2    .075       0
#XS Ineff= 2 , 0
       0  146.95 2398.53  200.95       0 2398.53
Permanent Ineff=
       F       F
#Block Obstruct= 1 ,-1
   59.31   91.242420.832
Bank Sta=159.45,187.2
Exp/Cntr=0.5,0.3

Type RM Length L Ch R = 3 ,113035  ,,,
Node Photo=H:\PROJ\06-0741\CE\GIS\DATA\FRENCH_BROAD_RIVER\SHAPEFILES\survey_data\photos\FBSTR_1260.JPG
BEGIN DESCRIPTION:
112956  FBSTR_1260
END DESCRIPTION:
Bridge Culvert--1,0,-1,-1, 0
Deck Dist Width WeirC Skew NumUp NumDn MinLoCord MaxHiCord MaxSubmerge Is_Ogee
14,12,2.6,0, 7, 7, , , 0.95, 0, 1,1,,
   93.61  156.95  156.95  168.95  190.95  190.95  212.15
 2398.52 2398.53 2398.53 2398.53 2398.53 2398.53 2398.39
                 2396.53 2396.53 2396.53
    85.5  159.24  159.24  176.24  193.24  193.24  200.62
 2398.53 2398.53 2398.53 2398.53 2398.53 2398.53 2398.45
                 2396.53 2396.53 2396.53
BR Coef=-1 , 0 , 0 ,, 0 ,,,0.8,0,,0,
WSPro=,,,, 1 ,,,, 0 ,,,, 0 ,,,,-1 ,-1 ,-1 , 0 , 0 , 0 , 0 , 0
BC Design=,, 0 ,, 0 ,,,,,,

Type RM Length L Ch R = 1 ,113015  ,188.06,195.51,221.81
BEGIN DESCRIPTION:
112936.9
END DESCRIPTION:
XS GIS Cut Line= 6
  929995.3482171  807277.6193626   930053.160882  807301.0576215
  930118.7859585  807332.3072678  930181.2862752  807341.6825713
  930207.8482697  807347.9320909  930254.7237633   807365.119806
#Sta/Elev= 30
       0 2416.64    4.49 2415.78   12.34 2415.48   21.79 2412.26   32.14 2409.98
   44.96 2406.26   54.32 2403.07   67.07  2400.4   79.11 2398.92   98.35 2397.34
  124.31 2396.25  145.89 2396.17  151.61 2395.83  158.76 2394.21  164.782391.438
  166.08 2390.84  183.67 2389.24  189.01 2390.19  191.08 2391.86  194.52 2394.71
  200.62 2398.45  209.45 2398.49  215.53 2399.46  221.38 2398.93  224.78 2400.24
     234 2406.62  242.95 2415.44  247.19 2419.17  259.61 2431.06  275.49 2439.03
#Mann= 3 , 0 , 0
       0     .07       0  164.78     .05       0  191.08    .075       0
#XS Ineff= 2 , 0
       0  149.24    2394  203.24       0    2394
Permanent Ineff=
       F       F
#Block Obstruct= 1 ,-1
   51.48   91.522420.153
Bank Sta=164.78,191.08
Exp/Cntr=0.5,0.3

Type RM Length L Ch R = 1 ,112819  ,167.92,165.01,124.48
BEGIN DESCRIPTION:
112741.3
END DESCRIPTION:
XS GIS Cut Line= 6
   929906.285906  807472.9327243  929987.5358056  807472.9327243
  930023.4731036  807485.4317634  930065.6609454  807507.3071303
  930118.7859585  807547.9320801  930159.4109083  807566.6826872
#Sta/Elev= 30
       0 2415.63   13.33 2411.52   19.86 2409.96   28.91 2407.42   41.79  2404.4
   44.88 2403.79   57.54 2401.65   81.71 2398.04   97.41 2395.32   98.46 2394.93
  105.07 2393.73  118.53 2392.48  136.91 2391.19  144.09  2390.2   157.9 2386.76
  170.21 2387.61  171.36 2387.49   176.7 2388.36  181.95 2389.22  188.09 2390.67
  189.07 2391.15  199.31 2394.89  201.23 2394.86   211.6 2396.54   224.6 2402.78
  227.35 2404.52  234.96  2410.3  254.22 2423.26  269.79 2436.13  278.49  2441.6
#Mann= 3 , 0 , 0
       0     .07       0  144.09     .05       0   176.7    .075       0
#Block Obstruct= 1 ,-1
   72.95   95.782413.162
Bank Sta=144.09,176.7
Exp/Cntr=0.3,0.1

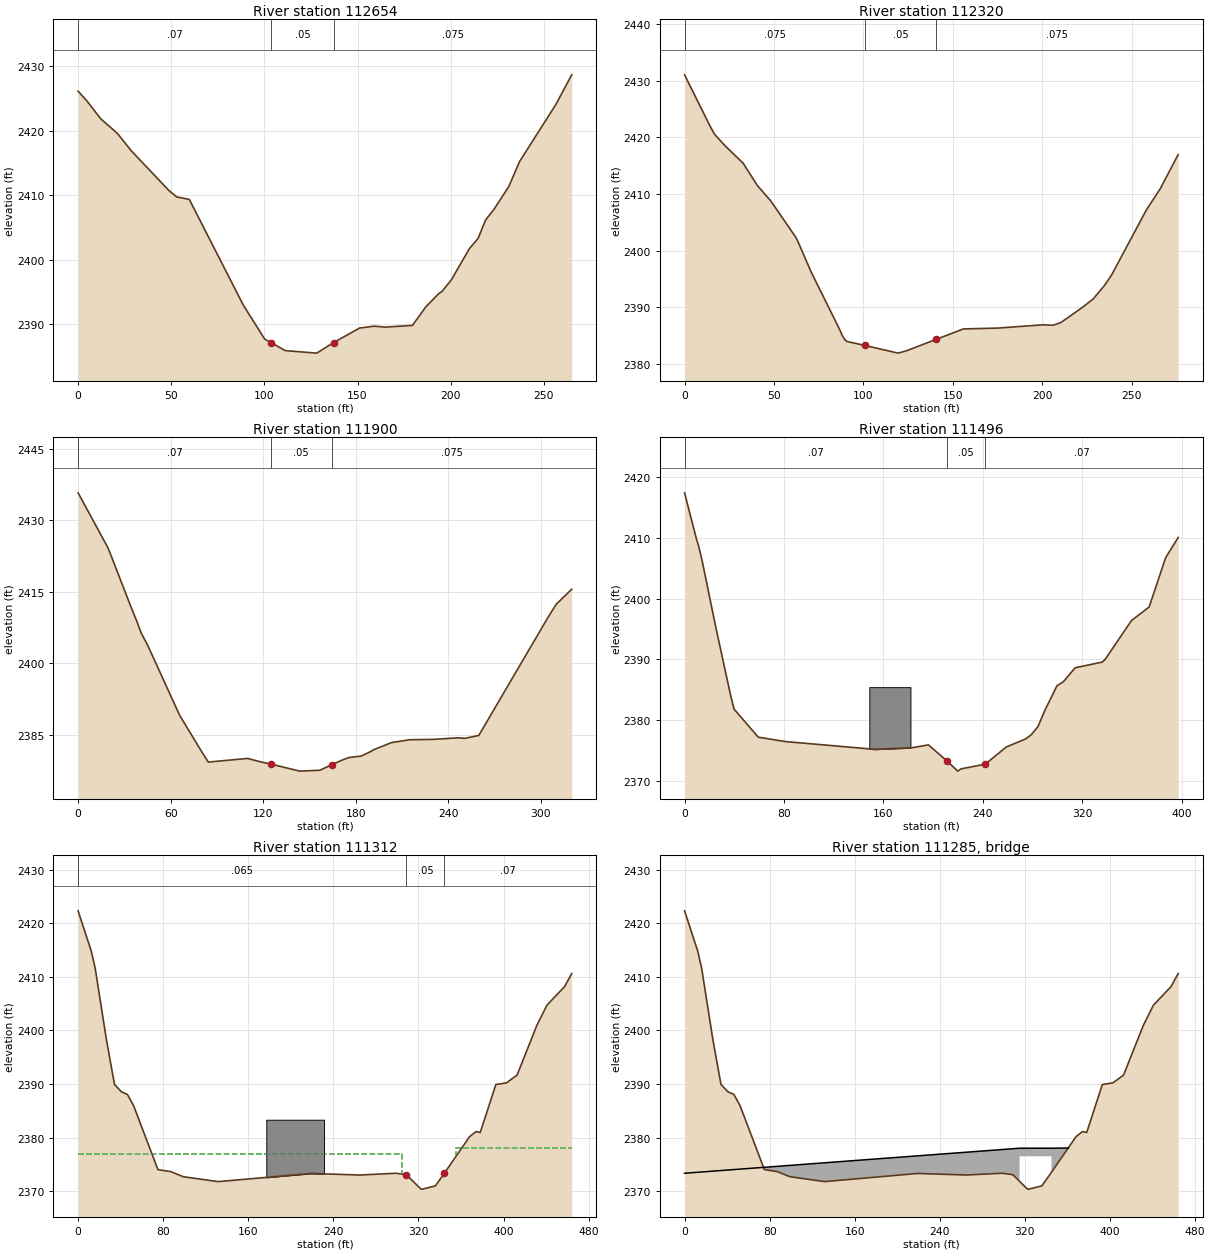
Type RM Length L Ch R = 1 ,112654  ,368.15,334.24,284.16
BEGIN DESCRIPTION:
112576.3
END DESCRIPTION:
XS GIS Cut Line= 6
   929851.599025  807627.6201119  929910.9735577  807629.1819797
  929959.4109191  807636.9943913  930007.8482805  807652.6202386
  930046.9113625  807657.3068662  930112.5364389  807647.9325868
#Sta/Elev= 30
       0 2426.14    4.84 2424.59   12.08 2421.88   21.21 2419.56   28.67 2416.86
   48.85 2410.72   52.93 2409.75   59.71 2409.36   88.64 2393.01   100.2  2387.7
  103.722387.167  111.16 2385.93  128.11 2385.54  137.162387.178  151.17 2389.43
  158.98 2389.72     165 2389.57  179.51 2389.84  186.68 2392.71  193.77 2394.81
   195.3 2395.08  200.37 2396.89  210.09 2401.74  214.76 2403.33  218.77 2406.18
  223.29 2407.83  231.23 2411.37  236.99 2415.22  256.63 2424.14  264.99 2428.67
#Mann= 3 , 0 , 0
       0     .07       0  103.72     .05       0  137.16    .075       0
Bank Sta=103.72,137.16
Exp/Cntr=0.3,0.1

Type RM Length L Ch R = 1 ,112320  ,414.79,419.69,427.76
BEGIN DESCRIPTION:
112242.1
END DESCRIPTION:
XS GIS Cut Line= 5
  929881.2857793  808022.9324386  929954.7232673  807990.1199004
  930004.7235207  807963.5568817  930070.3485972  807944.8072988
  930137.5365656  807922.9319319
#Sta/Elev= 30
       0 2431.04   14.21 2422.02    16.7 2420.59   22.28 2418.63   32.76 2415.44
   40.78 2411.48   48.28 2408.76   62.09 2402.42   62.98 2401.92   70.79 2396.23
   86.91 2385.97      88 2385.13   89.36 2384.42    90.6    2384  100.812383.285
  119.44 2381.93  123.96 2382.33  140.77 2384.37  155.88  2386.2  175.21 2386.35
  200.54 2386.93  206.12 2386.85  210.46 2387.34  222.24 2389.96  228.37 2391.46
  234.86 2393.91  238.84 2395.77  258.17 2407.19  265.96 2410.95  275.96 2416.96
#Mann= 3 , 0 , 0
       0    .075       0  100.81     .05       0  140.77    .075       0
Bank Sta=100.81,140.77
Exp/Cntr=0.3,0.1

Type RM Length L Ch R = 1 ,111900  ,375.81,404.69,382.23
BEGIN DESCRIPTION:
111822.4
END DESCRIPTION:
XS GIS Cut Line= 6
  930001.5987609  808418.2447653  930071.9114891  808388.5569869
  930131.2860219  808366.6826441   930148.473737  808354.1825808
  930192.2234466  808327.6195622  930300.0363648  808321.3700426
#Sta/Elev= 30
       0  2435.8   19.27 2424.31   21.46 2422.55   33.12  2412.8   38.69  2408.3
   40.79 2406.45   45.51  2403.5   65.81 2389.08   80.69 2381.12   84.46 2379.23
  109.95    2380  118.29 2379.28     125 2378.81  143.75 2377.33  156.75 2377.52
  164.31 2378.64  170.25 2379.52   175.4 2380.17  183.63  2380.5  190.08  2381.5
  191.73 2381.84  203.24 2383.33  215.17 2383.93  230.35    2384  246.55 2384.33
  250.84 2384.22  259.82 2384.83  304.42 2409.49  310.02 2412.39  320.05 2415.54
#Mann= 3 , 0 , 0
       0     .07       0     125     .05       0  164.31    .075       0
Bank Sta=125,164.31
Exp/Cntr=0.3,0.1

Type RM Length L Ch R = 1 ,111496  ,170.87,183.57,196.06
BEGIN DESCRIPTION:
111417.7
END DESCRIPTION:
XS GIS Cut Line= 6
  929990.6615895  808730.7443004  930026.5988876  808752.6196673
  930070.3485972  808766.6826226  930160.9738003  808765.1197306
  930281.2857577  808726.0576728  930346.9108342  808661.9944641
#Sta/Elev= 30
       0 2417.43    9.81 2409.63   11.26 2408.73   14.26 2406.13   24.94 2395.47
   37.32 2383.82   39.82 2381.81   59.32 2377.19   80.99 2376.47  152.71 2375.19
  182.42 2375.44  196.13 2375.92  211.312373.228  219.73  2371.6  222.36 2371.97
  241.89 2372.75   258.7 2375.57  274.59 2376.93  278.88 2377.61  284.24 2378.93
  289.87 2381.65   299.6 2385.68  304.52 2386.29  314.13 2388.62  335.95 2389.56
  338.36 2390.03  359.49 2396.41  373.64 2398.62  386.99 2406.78     397 2410.07
#Mann= 3 , 0 , 0
       0     .07       0  211.31     .05       0  241.89     .07       0
#Block Obstruct= 1 ,-1
  148.58  181.682385.428
Bank Sta=211.31,241.89
Exp/Cntr=0.5,0.3

Type RM Length L Ch R = 1 ,111312  ,33.99,45.29,61.4
BEGIN DESCRIPTION:
111234.2
END DESCRIPTION:
XS GIS Cut Line= 6
  929954.7232673  808911.9947067   930018.786476  808936.9948334
  930192.2234466  808936.9948334  930248.4732195  808932.3071816
  930325.0364915  808897.9317514  930404.7234991  808880.7450605
#Sta/Elev= 30
       0 2422.32   12.35 2414.83   16.03 2411.66   26.57 2398.36   34.24 2389.94
    40.7 2388.58   46.43 2388.06   52.16 2385.99   75.05 2374.05   87.03 2373.68
   98.86 2372.73  131.69 2371.81  219.12 2373.33  264.99 2373.04  298.65 2373.37
  308.69  2373.1  322.37 2370.42  323.86 2370.41  335.96 2371.02  344.41 2373.39
  368.03 2380.18  374.07 2381.14  378.15 2380.99  392.79 2389.92  402.73 2390.23
  412.75 2391.68  431.29 2400.93  440.85 2404.73  457.37 2408.18   464.1 2410.61
#Mann= 3 , 0 , 0
       0    .065       0  308.69     .05       0  344.41     .07       0
#XS Ineff= 2 , 0
       0     305    2377     355       0 2378.04
Permanent Ineff=
       F       F
#Block Obstruct= 1 ,-1
  176.95  231.272383.358
Bank Sta=308.69,344.41
Exp/Cntr=0.5,0.3

Type RM Length L Ch R = 3 ,111285  ,,,
Node Photo=H:\PROJ\06-0741\CE\GIS\DATA\FRENCH_BROAD_RIVER\SHAPEFILES\survey_data\photos\FBSTR_1273.JPG
BEGIN DESCRIPTION:
111210.2  FBSTR_1273
END DESCRIPTION:
Bridge Culvert--1,0,-1,-1, 0
Deck Dist Width WeirC Skew NumUp NumDn MinLoCord MaxHiCord MaxSubmerge Is_Ogee
17,10,2.6,0, 7, 7, , , 0.95, 0, 1,1,,
       0     315     315  326.49     345     345  360.89
 2373.37 2378.04 2378.04 2378.04 2378.04 2378.04 2378.08
                 2376.54 2376.54 2376.54
       0     335     335  359.79     365     365  383.55
 2373.42 2378.04 2378.04 2378.04 2378.04 2378.04 2378.11
                 2376.54 2376.54 2376.54
BR Coef=-1 , 0 , 0 ,, 0 ,,,0.8,0,,0,
WSPro=,,,, 1 ,,,, 0 ,,,, 0 ,,,,-1 ,-1 ,-1 , 0 , 0 , 0 , 0 , 0
BC Design=,, 0 ,, 0 ,,,,,,