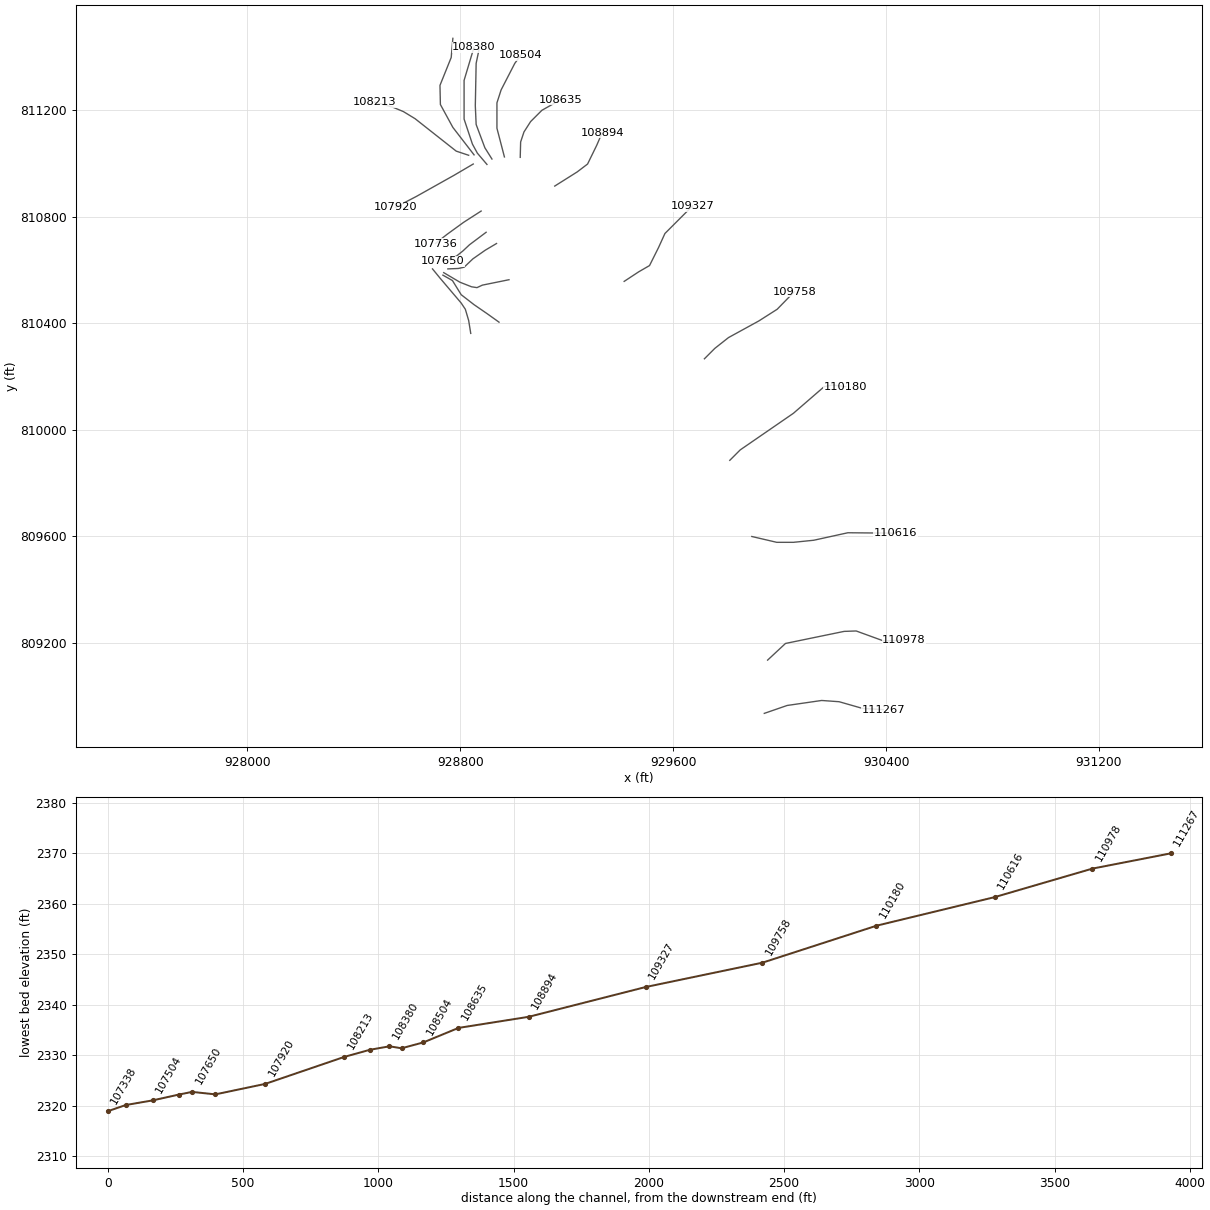
HEC-RAS study lds_big_laurel_crk.prj: lds_big_laurel_crk

--- lds_big_laurel_crk.g20 (geometry) --- (continued)

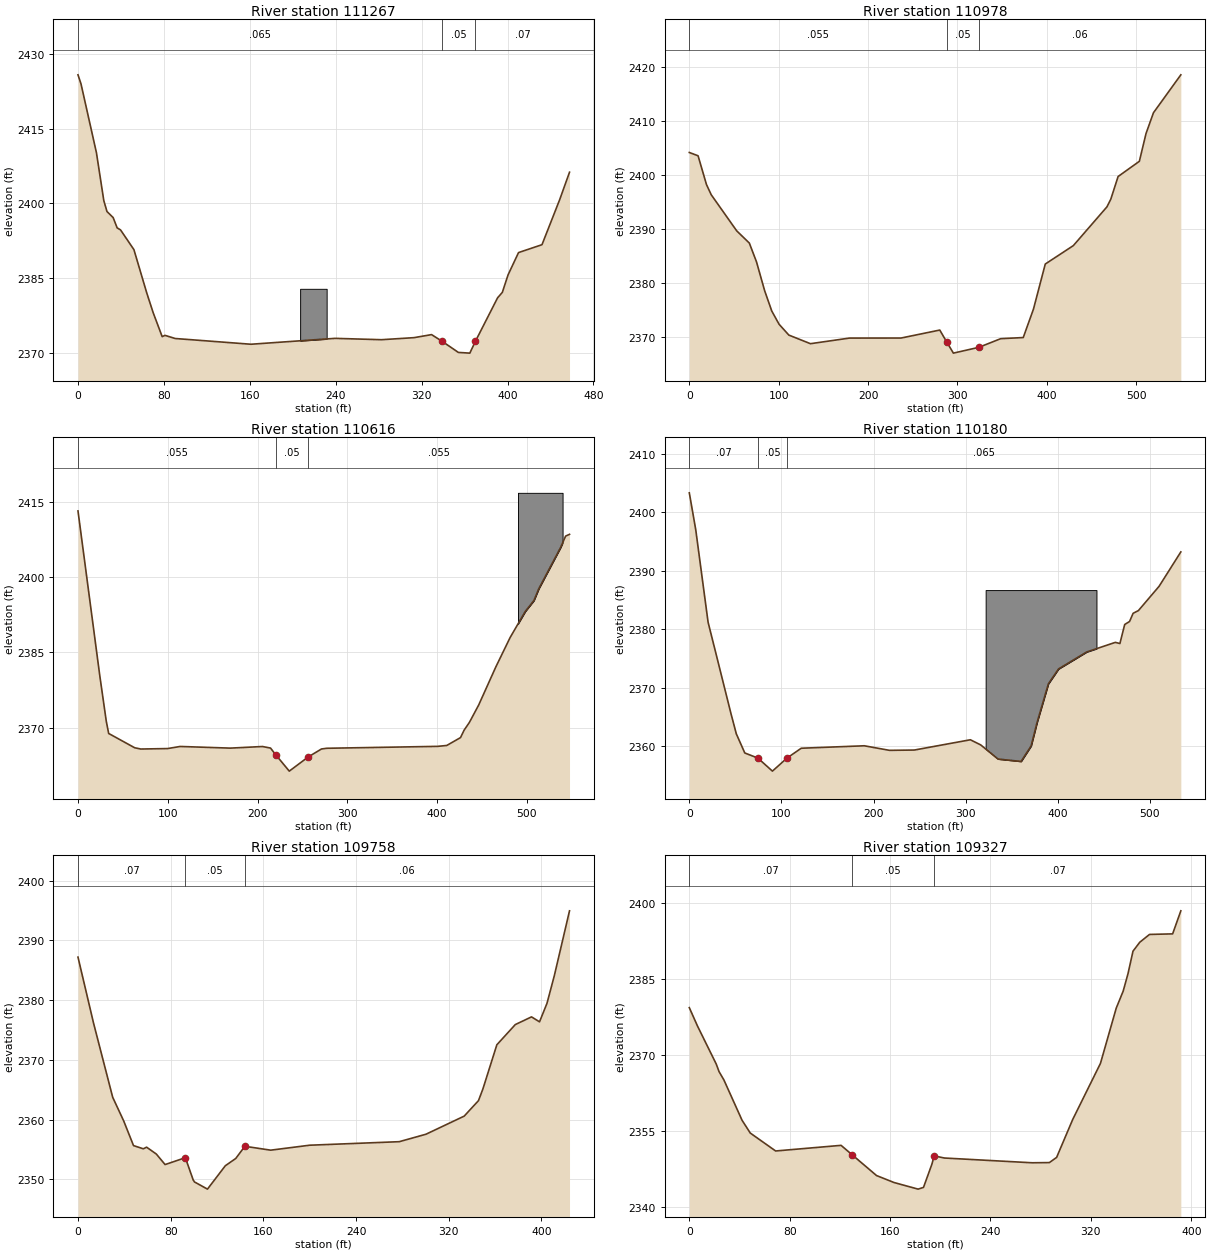
Type RM Length L Ch R = 1 ,111267  ,229.77,288.87,264.08
BEGIN DESCRIPTION:
111188.9
END DESCRIPTION:
XS GIS Cut Line= 6
   929942.223204  808935.4319414  930028.1607554  808965.1197199
  930157.8490405  808983.8693028  930223.4730928  808979.1826752
  930310.9735362  808954.1825485   930389.098676  808949.4948967
#Sta/Elev= 30
       0 2425.78    2.83 2423.95   17.16 2410.19   24.04 2400.57   27.01 2398.38
   32.73 2397.18   36.44 2395.12   39.63  2394.7   52.08 2390.75   64.06 2382.05
   70.01 2378.11   78.37 2373.32   81.06 2373.57   90.49 2372.94  161.08 2371.79
  239.33 2372.97  282.56  2372.7  312.86 2373.11  329.23 2373.72  339.26 2372.35
  354.19 2370.15  364.85 2370.01  370.04 2372.37  390.72  2381.1  395.11 2382.18
  400.44 2385.68  410.21 2390.16  432.05 2391.74  448.46 2400.73  457.68 2406.26
#Mann= 3 , 0 , 0
       0    .065       0  339.26     .05       0  370.04     .07       0
#XS Ineff= 2 , 0
       0     320    2373     380       0    2373
Permanent Ineff=
       F       F
#Block Obstruct= 1 ,-1
  206.84  231.542382.901
Bank Sta=339.26,370.04
Exp/Cntr=0.5,0.3

Type RM Length L Ch R = 1 ,110978  ,393.27,361.45,399.11
BEGIN DESCRIPTION:
110900.0
END DESCRIPTION:
XS GIS Cut Line= 6
  929954.7232673  809135.4319306  930021.9112358  809197.9322473
  930242.2236999  809243.2448489  930287.5363015  809244.8077409
   930390.661568  809207.3075509  930467.2238158  809210.4323107
#Sta/Elev= 30
       0 2404.23     9.8 2403.62   19.22 2398.27   24.51 2396.39   53.02 2389.69
   67.16 2387.42   75.15 2383.94   84.32 2378.56   92.22 2374.82  100.41 2372.36
  111.32 2370.35  135.51 2368.75  179.12 2369.79  236.88  2369.8  280.19 2371.28
  288.04 2369.04   295.4    2367  323.96 2368.08  348.32 2369.68  373.55 2369.89
  384.97 2375.16  398.19 2383.53  429.59 2386.95  467.17 2394.14  471.49 2395.56
  479.66 2399.77  503.43 2402.59  510.88 2407.74  519.21  2411.6  549.84 2418.64
#Mann= 3 , 0 , 0
       0    .055       0  288.04     .05       0  323.96     .06       0
Bank Sta=288.04,323.96
Exp/Cntr=0.3,0.1

Type RM Length L Ch R = 1 ,110616  ,357.29,436.71,553.88
BEGIN DESCRIPTION:
110538.5
END DESCRIPTION:
XS GIS Cut Line= 6
  929895.3487346  809599.4951178  929989.0986975  809577.6197509
  930051.5990142  809577.6197509  930128.1612621  809585.4321625
  930256.2856311  809613.5570489  930435.9731454  809611.9951811
#Sta/Elev= 30
       0 2413.15   24.27 2380.37   31.51 2371.29   34.17 2368.85   63.17    2366
   69.95 2365.75   99.83 2365.84  113.77 2366.26  169.64 2365.93  205.47 2366.25
   214.5 2365.94  220.032364.655  235.38 2361.35  256.52 2364.18  271.27 2365.76
  277.24  2365.9  400.62 2366.28  410.83 2366.46  426.15 2368.03  430.14 2369.51
  435.92 2371.02  446.36 2374.51  465.42 2382.08  481.39 2387.95  498.22 2393.13
  507.86  2395.3  513.28 2397.64  537.72 2405.91   543.2 2408.14  547.55 2408.49
#Mann= 3 , 0 , 0
       0    .055       0  220.03     .05       0  256.52    .055       0
#Block Obstruct= 1 ,-1
  490.12  539.812416.757
Bank Sta=220.03,256.52
Exp/Cntr=0.3,0.1

Type RM Length L Ch R = 1 ,110180  ,410.03,421.48,385.34
BEGIN DESCRIPTION:
110101.8
END DESCRIPTION:
XS GIS Cut Line= 6
   929812.535943  809885.4326584   929851.599025  809924.4947162
  930051.5990142  810061.9943888  930167.2233199  810161.9948955
  930198.4739903   810168.244415  930248.4732195  810161.9948955
#Sta/Elev= 30
       0 2403.35    6.99 2397.03   20.37 2381.21   45.47 2365.39   51.02 2362.08
   60.23  2358.8   74.47 2357.92   90.22 2355.69  105.93 2357.91   121.5 2359.61
  189.95 2360.03  217.25 2359.25  244.27  2359.3  305.09 2361.06  316.33 2360.18
  335.09 2357.76  360.15 2357.35  371.05    2360  377.42 2363.97  389.79 2370.64
  400.75 2373.18  431.42  2376.1  462.49 2377.74  467.43 2377.54  472.63  2380.8
  477.92 2381.32  481.78 2382.72   487.5 2383.18  509.96 2387.34  533.57 2393.23
#Mann= 3 , 0 , 0
       0     .07       0   74.47     .05       0  105.93    .065       0
#Block Obstruct= 1 ,-1
  321.67  441.992386.693
Bank Sta=74.47,105.93
Exp/Cntr=0.3,0.1

Type RM Length L Ch R = 1 ,109758  ,405.41,431.41,502.46
BEGIN DESCRIPTION:
109680.3
END DESCRIPTION:
XS GIS Cut Line= 6
  929717.2230881  810266.6820298  929756.2861701  810305.7451118
  929807.8482912  810346.3700616  929921.9107291  810408.8693541
  929990.6615895  810452.6200878   930054.723774  810518.2451643
#Sta/Elev= 30
       0  2387.2   13.36 2376.21   29.95 2363.75   39.51 2359.76   47.92 2355.66
   56.38 2355.12   59.23 2355.39   67.63 2354.24   75.19 2352.48   92.68 2353.63
   99.46  2349.9  100.59 2349.57  111.78 2348.37  127.16 2352.28  136.18  2353.5
  144.04 2355.54  166.35 2354.89  199.99 2355.72  277.33 2356.31  300.41 2357.56
  333.39 2360.59  345.71 2363.18  349.52 2365.13  361.57 2372.53   377.5 2375.91
   391.5  2377.2  398.41 2376.37  404.85 2379.47  411.15 2384.07   424.3 2394.95
#Mann= 3 , 0 , 0
       0     .07       0   92.68     .05       0  144.04     .06       0
Bank Sta=92.68,144.04
Exp/Cntr=0.3,0.1

Type RM Length L Ch R = 1 ,109327  ,454.41,432.4,417.75
BEGIN DESCRIPTION:
109248.9
END DESCRIPTION:
XS GIS Cut Line= 6
  929415.6607243  810557.3072222  929470.3486295  810593.2445202
  929510.9735793  810616.6817549  929545.3490095  810685.4326153
  929568.7862442  810736.9947365  929671.9115107   810840.120003
#Sta/Elev= 30
       0 2379.37    6.58 2375.71   21.42 2368.26   23.71 2366.74   27.55 2365.11
   42.04 2357.14   48.58 2354.62   68.78 2351.08  120.95 2352.19  129.892350.299
  149.19 2346.23  163.17 2344.85  182.33 2343.55  186.62 2343.89  193.31 2348.47
  195.17 2350.11  203.27 2349.69  273.23 2348.75  286.92 2348.79   292.7 2349.81
  305.53  2357.3  327.64 2368.37  340.22 2379.28  345.74 2382.63  349.55 2386.04
  353.56 2390.51  358.93 2392.27  366.72 2393.82  385.16 2393.93  391.69 2398.48
#Mann= 3 , 0 , 0
       0     .07       0  129.89     .05       0  195.17     .07       0
Bank Sta=129.89,195.17
Exp/Cntr=0.3,0.1

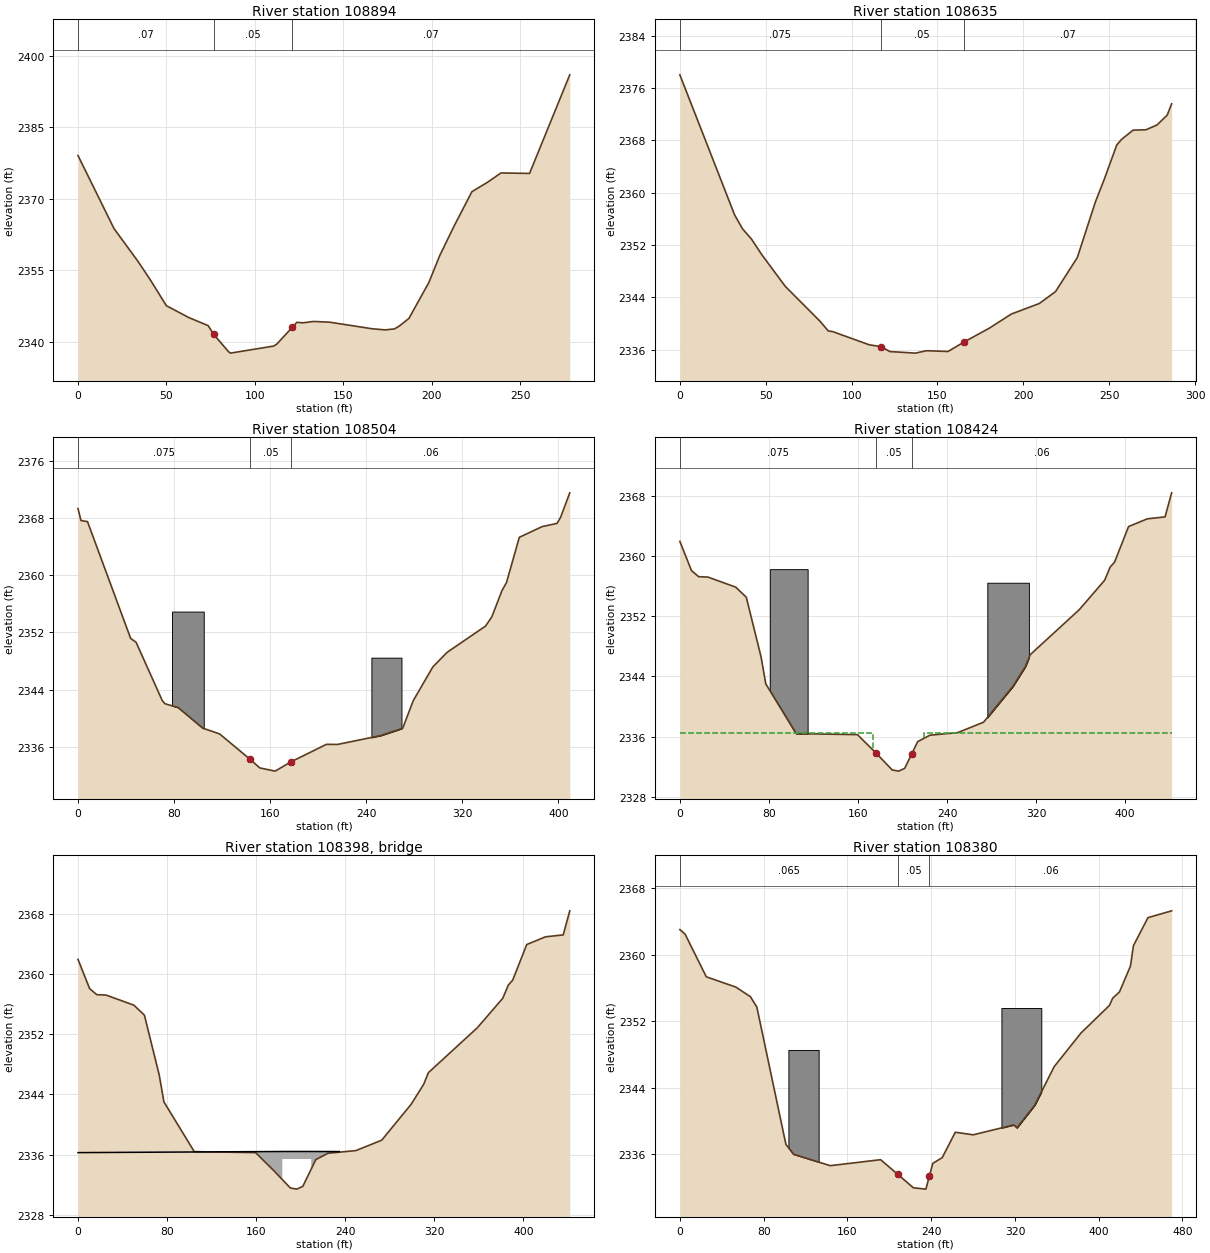
Type RM Length L Ch R = 1 ,108894  ,224.99,259.67,240.56
BEGIN DESCRIPTION:
108816.5
END DESCRIPTION:
XS GIS Cut Line= 5
  929154.7233104  810915.1193588   929239.098994   810968.244372
  929278.1610518  810997.9321504   929312.536482  811068.2448787
  929332.8489569  811115.1193481
#Sta/Elev= 30
       0 2379.09   20.33  2363.8   33.93 2356.89   41.05 2352.94   49.96  2347.6
   62.73  2345.1   73.61 2343.42   76.78 2341.57   85.05 2337.99    86.2 2337.65
  110.67 2339.13  112.44 2339.54  121.162343.057  123.77 2344.11   127.3 2344.01
  133.13 2344.29  142.15 2344.15  166.17 2342.77  173.73 2342.52  178.99 2342.73
  181.58  2343.3  187.13 2344.91  198.43 2352.46  204.55 2358.08  212.92 2364.46
  222.78 2371.51  231.81 2373.53  239.21 2375.44  255.38 2375.34  278.12 2396.02
#Mann= 3 , 0 , 0
       0     .07       0   76.78     .05       0  121.16     .07       0
Bank Sta=76.78,121.16
Exp/Cntr=0.3,0.1

Type RM Length L Ch R = 1 ,108635  ,83.09,130.31,188.25
BEGIN DESCRIPTION:
108556.9
END DESCRIPTION:
XS GIS Cut Line= 6
  929025.0360494  811022.9322771  929026.5989414   811080.744942
  929039.0990047   811118.245132  929064.0981072  811157.3071898
   929106.285949  811199.4950316  929178.1615693  811240.1199814
#Sta/Elev= 30
       0 2378.03   31.86 2356.61   36.48 2354.47   41.66 2352.91   47.61 2350.55
   61.33 2345.68   81.61 2340.33   86.39 2338.85   89.13 2338.73  110.32 2336.72
  116.94 2336.45  122.29 2335.69  137.08 2335.45  143.63 2335.82   156.1  2335.7
  165.26 2337.12  180.19 2339.27  192.99 2341.43  209.27 2343.04  218.69 2344.85
   231.4 2350.06     242 2358.62  246.94 2361.93  254.41 2367.31  257.26 2368.17
  263.91 2369.57  271.34 2369.62  277.84 2370.36  283.79 2371.88  286.33  2373.6
#Mann= 3 , 0 , 0
       0    .075       0  116.94     .05       0  165.26     .07       0
Bank Sta=116.94,165.26
Exp/Cntr=0.3,0.1

Type RM Length L Ch R = 1 ,108504  ,64.36,80.24,119.24
BEGIN DESCRIPTION:
108426.6
END DESCRIPTION:
XS GIS Cut Line= 6
  928965.6615167  811024.4951691  928937.5356061  811132.3070632
  928937.5356061  811227.6199181  928953.1614534  811276.0572795
  929004.7235745   811376.056762  929028.1608092  811407.3074324
#Sta/Elev= 30
       0 2369.33    2.48 2367.66    7.91 2367.51   43.85 2351.15   48.36 2350.62
   70.11 2342.47   72.37 2342.01   83.38 2341.47  103.78  2338.6   117.9 2337.78
  142.972334.275  151.37 2333.02  164.12 2332.57  177.59 2333.89  206.88 2336.32
  216.25 2336.31  252.08 2337.55  270.38 2338.57  279.11 2342.42  295.49 2347.17
  307.49 2349.22  339.35 2352.88  344.61 2354.18  352.98 2357.83  356.83 2358.99
  367.47 2365.31   386.5 2366.81  398.89 2367.26  401.83  2368.1  409.48 2371.54
#Mann= 3 , 0 , 0
       0    .075       0  142.97     .05       0  177.59     .06       0
#Block Obstruct= 2 ,-1
  244.31  269.362348.461    78.3  104.712354.915
Bank Sta=142.97,177.59
Exp/Cntr=0.5,0.3

Type RM Length L Ch R = 1 ,108424  ,39.46,44.7,38.46
BEGIN DESCRIPTION:
108346.3
END DESCRIPTION:
XS GIS Cut Line= 6
  928918.7860231  811016.6827575  928892.2240286  811058.8695751
  928859.4114904  811146.3700185  928856.2857064  811216.6827467
  928859.4114904   811376.056762  928873.4734216  811443.2447305
#Sta/Elev= 30
       0 2361.94   10.47 2358.05   16.92 2357.25   25.18  2357.2   50.19 2355.86
   59.65 2354.53   72.95 2346.59   77.18 2343.01  104.45  2336.4  159.51 2336.27
  175.77 2333.89  190.78 2331.57  196.54 2331.42  201.96 2331.79  208.22  2333.7
  213.67 2335.34  224.62 2336.19  249.67 2336.54  272.82 2337.92  299.26 2342.69
  310.52 2345.34  314.75 2346.89  358.68 2352.85   381.6 2356.78  386.59 2358.54
  390.49 2359.18  403.08 2363.91     420 2364.94  435.87 2365.19  441.75 2368.39
#Mann= 3 , 0 , 0
       0    .075       0  175.77     .05       0  208.22     .06       0
#XS Ineff= 2 , 0
       0  173.54 2336.42  219.54       0 2336.42
Permanent Ineff=
       F       F
#Block Obstruct= 2 ,-1
  276.18  313.522356.449    80.8  114.77 2358.25
Bank Sta=175.77,208.22
Exp/Cntr=0.5,0.3

Type RM Length L Ch R = 3 ,108398  ,,,
Node Photo=H:\PROJ\06-0741\CE\GIS\DATA\FRENCH_BROAD_RIVER\SHAPEFILES\survey_data\photos\FBSTR_1283.JPG
BEGIN DESCRIPTION:
108322  FBSTR_1283
END DESCRIPTION:
Bridge Culvert--1,0,-1,-1, 0
Deck Dist Width WeirC Skew NumUp NumDn MinLoCord MaxHiCord MaxSubmerge Is_Ogee
17,15,2.6,0, 7, 7, , , 0.95, 0, 1,1,,
       0  183.54  183.54  196.54  209.54  209.54  234.66
 2336.27 2336.42 2336.42 2336.42 2336.42 2336.42 2336.41
                 2335.42 2335.42 2335.42
       0     213     213  230.99     239     239  262.18
 2335.35 2336.42 2336.42 2336.42 2336.42 2336.42 2336.33
                 2335.42 2335.42 2335.42
BR Coef=-1 , 0 , 0 ,, 0 ,,,0.8,0,,0,
WSPro=,,,, 1 ,,,, 0 ,,,, 0 ,,,,-1 ,-1 ,-1 , 0 , 0 , 0 , 0 , 0
BC Design=,, 0 ,, 0 ,,,,,,

Type RM Length L Ch R = 1 ,108380  ,23.25,72.79,79.21
BEGIN DESCRIPTION:
108301.6
END DESCRIPTION:
XS GIS Cut Line= 6
  928900.0364402  810996.3692584   928864.098118  811038.5571002
  928845.3485351  811072.9325304  928814.0988888  811166.6824934
  928814.0988888  811311.9945775  928851.5990788  811436.9952109
#Sta/Elev= 30
       0 2363.01    4.94 2362.48   25.23 2357.34   53.46  2356.1   67.35 2354.95
   73.53  2353.7  101.27 2337.19  108.48 2336.01  143.59 2334.63  191.69 2335.35
  207.91 2333.61  222.99 2331.97  234.96 2331.81  238.292333.374  241.56 2334.91
  250.59  2335.6  263.04 2338.65  280.11 2338.34  318.92 2339.53  321.92 2339.18
  338.93 2341.91  357.45 2346.53     383 2350.57   410.2 2353.89  413.37 2354.77
  419.89 2355.53   430.3 2358.62  433.16 2361.07  447.03 2364.45  469.64 2365.27
#Mann= 3 , 0 , 0
       0    .065       0  207.91     .05       0  238.29     .06       0
#XS Ineff= 2 , 0
       0     203    2333     249       0    2333
Permanent Ineff=
       F       F
#Block Obstruct= 2 ,-1
  307.09  345.182353.587  103.64  132.542348.545
Bank Sta=207.91,238.29
Exp/Cntr=0.5,0.3

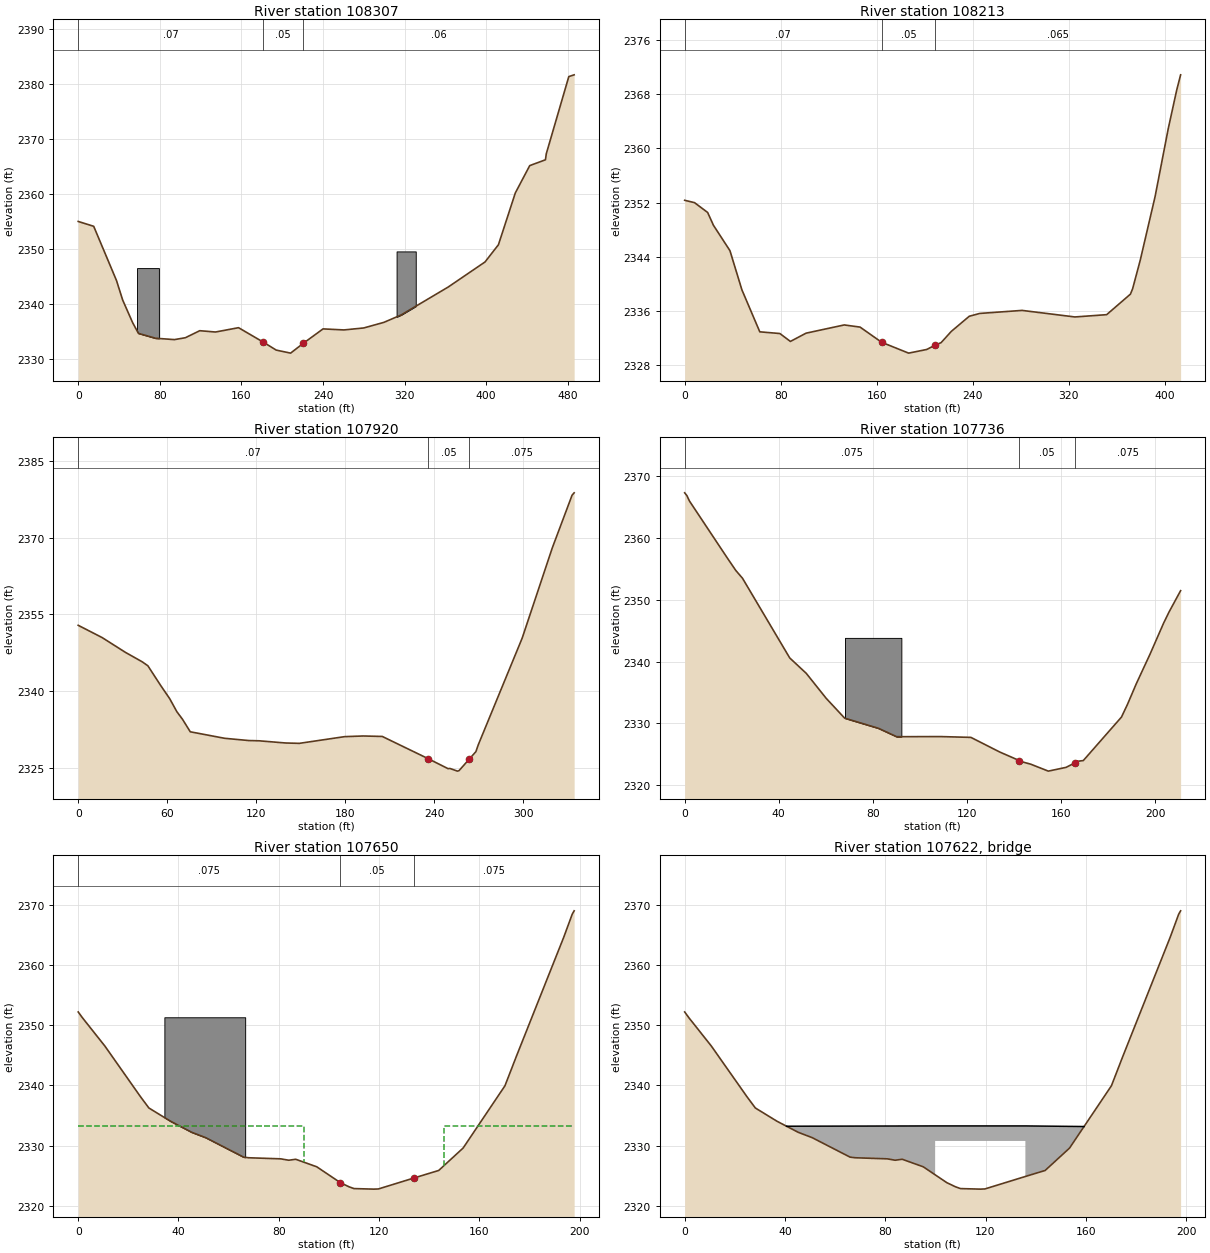
Type RM Length L Ch R = 1 ,108307  ,44.99,93.48,267.17
BEGIN DESCRIPTION:
108228.8
END DESCRIPTION:
XS GIS Cut Line= 6
  928851.5990788  811032.3075806   928771.911047   811135.431823
  928725.0365777  811221.3693743  928723.4736857  811293.2449946
  928765.6615275  811397.9321289   928771.911047  811469.8077491
#Sta/Elev= 30
       0 2355.07   15.18 2354.19   37.52 2344.33   43.58 2340.78    53.2 2336.72
   59.02 2334.71   75.73 2333.82   94.35 2333.57  105.03 2333.91  119.16 2335.19
  134.59 2334.95  157.17 2335.74  181.07 2333.15  194.15 2331.66  208.24 2331.11
  220.522332.875  240.04 2335.52   260.5 2335.33  279.99 2335.69  299.71 2336.71
  316.56 2338.05  362.84 2343.15  398.84  2347.7  411.97 2350.83  428.54 2360.26
  442.66 2365.23  458.07 2366.29  458.89 2367.38  480.97 2381.43  486.21 2381.75
#Mann= 3 , 0 , 0
       0     .07       0  181.07     .05       0  220.52     .06       0
#Block Obstruct= 2 ,-1
  312.12  330.912349.619   57.67   79.122346.581
Bank Sta=181.07,220.52
Exp/Cntr=0.3,0.1

Type RM Length L Ch R = 1 ,108213  ,92.8,293.09,390.05
BEGIN DESCRIPTION:
108135.3
END DESCRIPTION:
XS GIS Cut Line= 6
  928831.2855798  811030.7446887  928784.4111104  811046.3695118
  928629.7237227  811168.2443612  928585.9740131  811194.8073799
  928548.4738231   811210.432203  928476.5982029  811230.7446779
#Sta/Elev= 30
       0 2352.33    8.21 2351.98   19.12 2350.53   23.97 2348.63    37.7 2344.88
   47.65 2339.09   62.56 2332.87   79.28 2332.62   88.05 2331.45  101.06 2332.67
  132.91 2333.89  146.08 2333.57   164.1 2331.32  186.54 2329.72  201.58 2330.26
  208.75 2330.91  213.58 2331.27  221.97 2332.92  236.99 2335.17  245.66 2335.59
  281.03 2336.04  324.99 2335.07  351.44 2335.41  371.22 2338.44  373.04 2339.22
  379.39 2343.44  391.79 2352.88  402.74 2362.92  409.72 2368.58  413.05 2370.89
#Mann= 3 , 0 , 0
       0     .07       0   164.1     .05       0  208.75    .065       0
Bank Sta=164.1,208.75
Exp/Cntr=0.3,0.1

Type RM Length L Ch R = 1 ,107920  ,177.12,184.02,191.04
BEGIN DESCRIPTION:
107842.3
END DESCRIPTION:
XS GIS Cut Line= 4
  928848.4732949  810997.9321504  928776.5986988  810955.7443086
  928634.4113745   810876.057301  928556.2862347  810835.4323512
#Sta/Elev= 30
       0 2352.87   16.13 2350.47   31.89 2347.57   43.17 2345.73   46.99 2344.95
   55.59 2341.11   61.68 2338.53   66.51 2335.98   70.29 2334.51   75.57 2332.05
    98.7 2330.78  114.95 2330.34  121.93 2330.29  139.86 2329.86  149.08 2329.79
  179.57  2331.1  192.06 2331.23  205.01 2331.14  235.85 2326.81  249.32 2324.85
  250.63 2324.88   255.7 2324.36  256.78 2324.46  263.492326.651  268.15 2328.17
  269.75 2329.51  299.36 2350.37  319.56 2367.93     333 2378.31  334.39 2378.77
#Mann= 3 , 0 , 0
       0     .07       0  235.85     .05       0  263.49    .075       0
Bank Sta=235.85,263.49
Exp/Cntr=0.3,0.1

Type RM Length L Ch R = 1 ,107736  ,81.03,85.99,80.04
BEGIN DESCRIPTION:
107658.2
END DESCRIPTION:
XS GIS Cut Line= 4
  928878.1610733  810821.3693959  928812.5359968  810779.1825783
  928750.0356802  810733.8699767  928706.2859706  810699.4945465
#Sta/Elev= 30
       0 2367.32     .94 2366.87    2.02    2366   17.96 2356.87   21.75 2354.75
   24.58  2353.5   44.67  2340.6   51.72  2338.1   60.16 2334.07   68.02 2330.86
   82.37 2329.22   90.11 2327.86  108.67 2327.88  121.69 2327.75  133.96 2325.38
  141.37 2324.15  142.03 2323.94  147.08 2323.42  154.61 2322.29  162.16  2322.9
  166.05 2323.65  167.25 2323.89  169.48    2324  185.71 2331.04  188.28 2333.11
  191.96 2336.39   197.9 2341.26   203.6 2346.22  205.92 2348.03  210.85 2351.49
#Mann= 3 , 0 , 0
       0    .075       0  142.03     .05       0  166.05    .075       0
#Block Obstruct= 1 ,-1
   68.16   92.122343.849
Bank Sta=142.03,166.05
Exp/Cntr=0.5,0.3

Type RM Length L Ch R = 1 ,107650  ,51.85,48.97,42.83
BEGIN DESCRIPTION:
107572.2
END DESCRIPTION:
XS GIS Cut Line= 5
  928896.9106562  810741.6823883  928834.4113637  810694.8068947
  928809.4112371    810671.36966  928785.9740024  810652.6200771
   928734.410857  810632.3076022
#Sta/Elev= 27
       0 2352.21    1.68 2351.25   10.65 2346.54   24.83 2338.14   28.19 2336.26
   36.85 2334.05   45.28 2332.22   50.86 2331.33   65.94  2328.1   67.96 2327.99
   80.81 2327.81   83.98 2327.58   86.77 2327.74   95.16 2326.49  104.55 2323.86
  108.01 2323.17  110.01 2322.87  117.91 2322.78  119.76 2322.81  134.01 2324.64
   143.8 2325.88  153.53  2329.6  170.23 2339.95  174.85 2344.91  193.73 2364.68
  197.06 2368.45  197.83 2369.01
#Mann= 3 , 0 , 0
       0    .075       0  104.55     .05       0  134.01    .075       0
#XS Ineff= 2 , 0
       0   89.91 2333.28  145.91       0 2333.28
Permanent Ineff=
       F       F
#Block Obstruct= 1 ,-1
   34.37    66.62351.329
Bank Sta=104.55,134.01
Exp/Cntr=0.5,0.3

Type RM Length L Ch R = 3 ,107622  ,,,
Node Photo=H:\PROJ\06-0741\CE\GIS\DATA\FRENCH_BROAD_RIVER\SHAPEFILES\survey_data\photos\FBSTR_1773A.JPG
BEGIN DESCRIPTION:
107543  FBSTR_1773A
END DESCRIPTION:
Bridge Culvert--1,0,-1,-1, 0
Deck Dist Width WeirC Skew NumUp NumDn MinLoCord MaxHiCord MaxSubmerge Is_Ogee
25,10,2.6,0, 7, 7, , , 0.95, 0, 1,1,,
   40.64   99.91   99.91  117.91  135.91  135.91   159.3
 2333.23 2333.28 2333.28 2333.28 2333.28 2333.28 2333.18
                 2330.78 2330.78 2330.78
   47.68  102.86  102.86  120.86  138.86  138.86     174
 2333.19 2333.28 2333.28 2333.28 2333.28 2333.282332.457
                 2330.78 2330.78 2330.78
BR Coef=-1 , 0 , 0 ,, 0 ,,,0.8,0,,0,
WSPro=,,,, 1 ,,,, 0 ,,,, 0 ,,,,-1 ,-1 ,-1 , 0 , 0 , 0 , 0 , 0
BC Design=,, 0 ,, 0 ,,,,,,

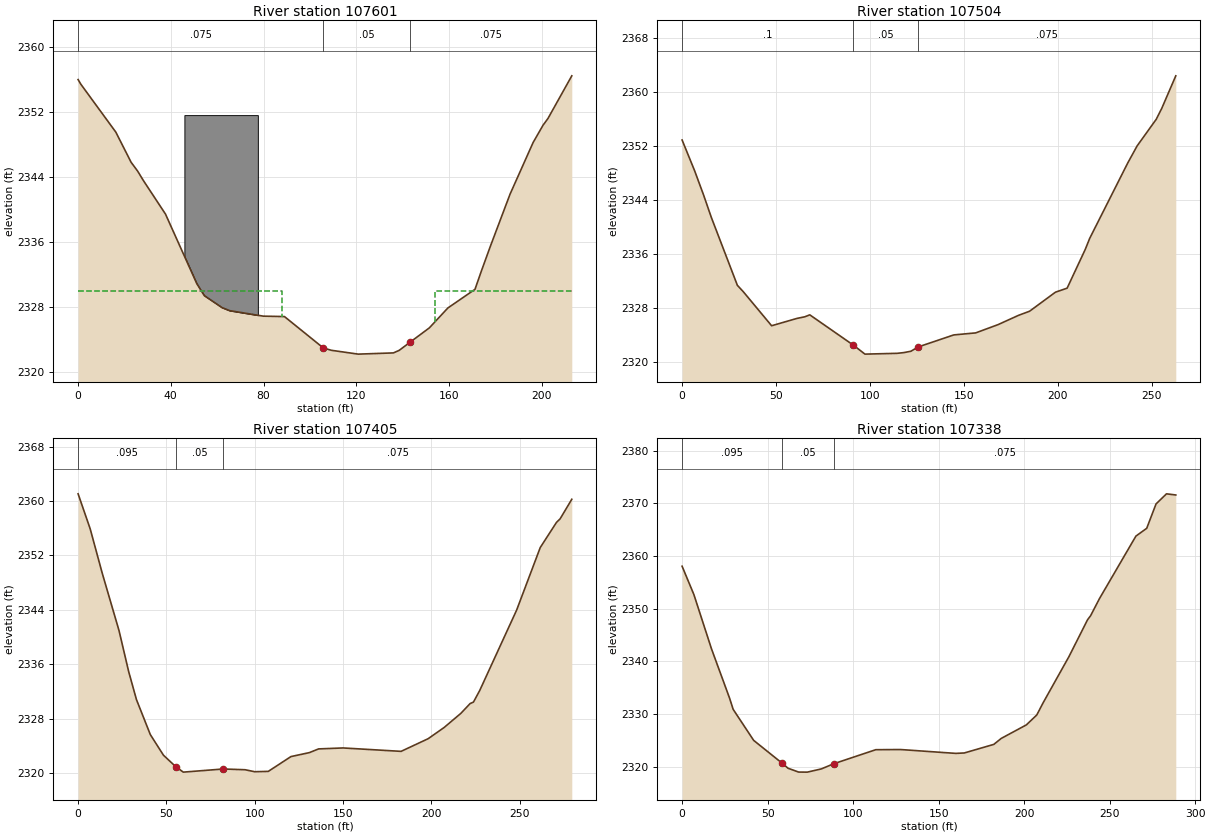
Type RM Length L Ch R = 1 ,107601  ,130.45,96.67,44.6
BEGIN DESCRIPTION:
107523.3
END DESCRIPTION:
XS GIS Cut Line= 6
  928935.9737382  810699.4945465  928893.7858965  810674.4944198
  928846.9114271  810641.6818816  928814.0988888  810610.4322353
  928792.2235219  810605.7445835  928753.1614641  810604.1827157
#Sta/Elev= 29
       0 2356.02    1.15 2355.46   16.27 2349.56   22.87 2345.85   25.67 2344.77
   28.31 2343.54   37.72 2339.47   51.21 2330.92   54.45 2329.45   62.06 2327.98
   65.39  2327.6   79.93 2326.92   89.04 2326.87  105.86    2323  109.32 2322.72
  120.86 2322.25  136.05  2322.4  138.54 2322.71  143.41 2323.75  151.57 2325.48
  159.57 2327.93  171.26 2330.22  173.94 2332.41  177.94 2335.55  186.38 2341.92
  196.33 2348.27  200.63 2350.41  202.74 2351.23  213.03 2356.48
#Mann= 3 , 0 , 0
       0    .075       0  105.86     .05       0  143.41    .075       0
#XS Ineff= 2 , 0
       0   87.86    2330  153.86       0    2330
Permanent Ineff=
       F       F
#Block Obstruct= 1 ,-1
   45.87   77.562351.645
Bank Sta=105.86,143.41
Exp/Cntr=0.5,0.3

Type RM Length L Ch R = 1 ,107504  ,142.86,99.5,11.92
BEGIN DESCRIPTION:
107426.6
END DESCRIPTION:
XS GIS Cut Line= 6
  928982.8482076  810563.5567417  928882.8487251  810543.2442668
  928862.5362502  810533.8699875  928842.2237753  810536.9947472
  928798.4740657  810554.1824624  928737.5356168  810590.1197604
#Sta/Elev= 30
       0 2352.87    6.69 2348.29   11.41 2344.73   15.54  2341.4   29.42 2331.31
   32.57 2330.36   47.64 2325.31   61.13  2326.4   65.32 2326.64   67.95 2326.93
   91.11 2322.44   97.32  2321.1   114.5 2321.22   118.1 2321.33  121.79 2321.53
  125.69 2322.17  144.59 2323.95  156.25 2324.25  168.09 2325.47  179.09 2326.86
   184.9 2327.46   198.7 2330.29  204.92 2330.89  214.58 2336.65  216.95 2338.29
  237.19 2349.47  242.18    2352  252.31 2355.93  255.22 2357.53  262.74 2362.39
#Mann= 3 , 0 , 0
       0      .1       0   91.11     .05       0  125.69    .075       0
Bank Sta=91.11,125.69
Exp/Cntr=0.3,0.1

Type RM Length L Ch R = 1 ,107405  ,92.34,66.91,34.5
BEGIN DESCRIPTION:
107327.1
END DESCRIPTION:
XS GIS Cut Line= 6
  928945.3490418  810404.1827265   928901.598308  810435.4323727
  928851.5990788  810469.8067788  928803.1606933  810507.3069688
  928770.3481551  810560.4319819   928734.410857  810580.7444568
#Sta/Elev= 30
       0 2361.05    6.85  2355.9   13.62 2349.43   23.17 2340.96   28.62 2334.95
   33.02 2330.84   40.88 2325.69    48.3 2322.67   55.27 2320.98   59.54 2320.18
   82.15 2320.64   94.56 2320.53    99.9 2320.24  107.65 2320.29  120.45 2322.46
  130.95 2323.05  136.11 2323.59  149.98 2323.73   182.8 2323.23  198.13 2325.09
  207.14 2326.73  216.59  2328.8  221.89 2330.25  223.77 2330.47  227.35 2332.19
  248.21 2343.98  261.57 2353.16  270.74 2356.85  272.82 2357.38  279.42 2360.25
#Mann= 3 , 0 , 0
       0    .095       0   55.27     .05       0   82.15    .075       0
Bank Sta=55.27,82.15
Exp/Cntr=0.3,0.1

Type RM Length L Ch R = 1 ,107338  ,182.59,159.16,35.4
BEGIN DESCRIPTION:
107260.2
END DESCRIPTION:
XS GIS Cut Line= 6
  928839.0990155  810361.9948847  928831.2855798  810410.4322461
  928818.7865406  810452.6200878  928803.1606933  810476.0573225
  928723.4736857  810569.8072855  928695.3487992  810604.1827157
#Sta/Elev= 30
       0 2358.06     6.9 2352.67    17.2 2342.36   27.71 2333.05   29.87 2330.87
   41.86 2324.98   58.52 2320.64   61.94 2319.69   68.16 2318.96   73.24 2318.95
   81.41 2319.56   88.85 2320.56  113.27 2323.21   127.8 2323.24  160.03 2322.51
  165.05 2322.59   182.3 2324.22  186.62 2325.35  201.31 2327.92  207.41  2329.8
  211.18 2332.15  226.25  2340.9  237.11 2347.89  238.89 2348.66  244.13 2351.94
  265.39 2363.78  271.71 2365.26  277.16 2369.89  283.28 2371.81  288.71 2371.59
#Mann= 3 , 0 , 0
       0    .095       0   58.52     .05       0   88.85    .075       0
Bank Sta=58.52,88.85
Exp/Cntr=0.3,0.1