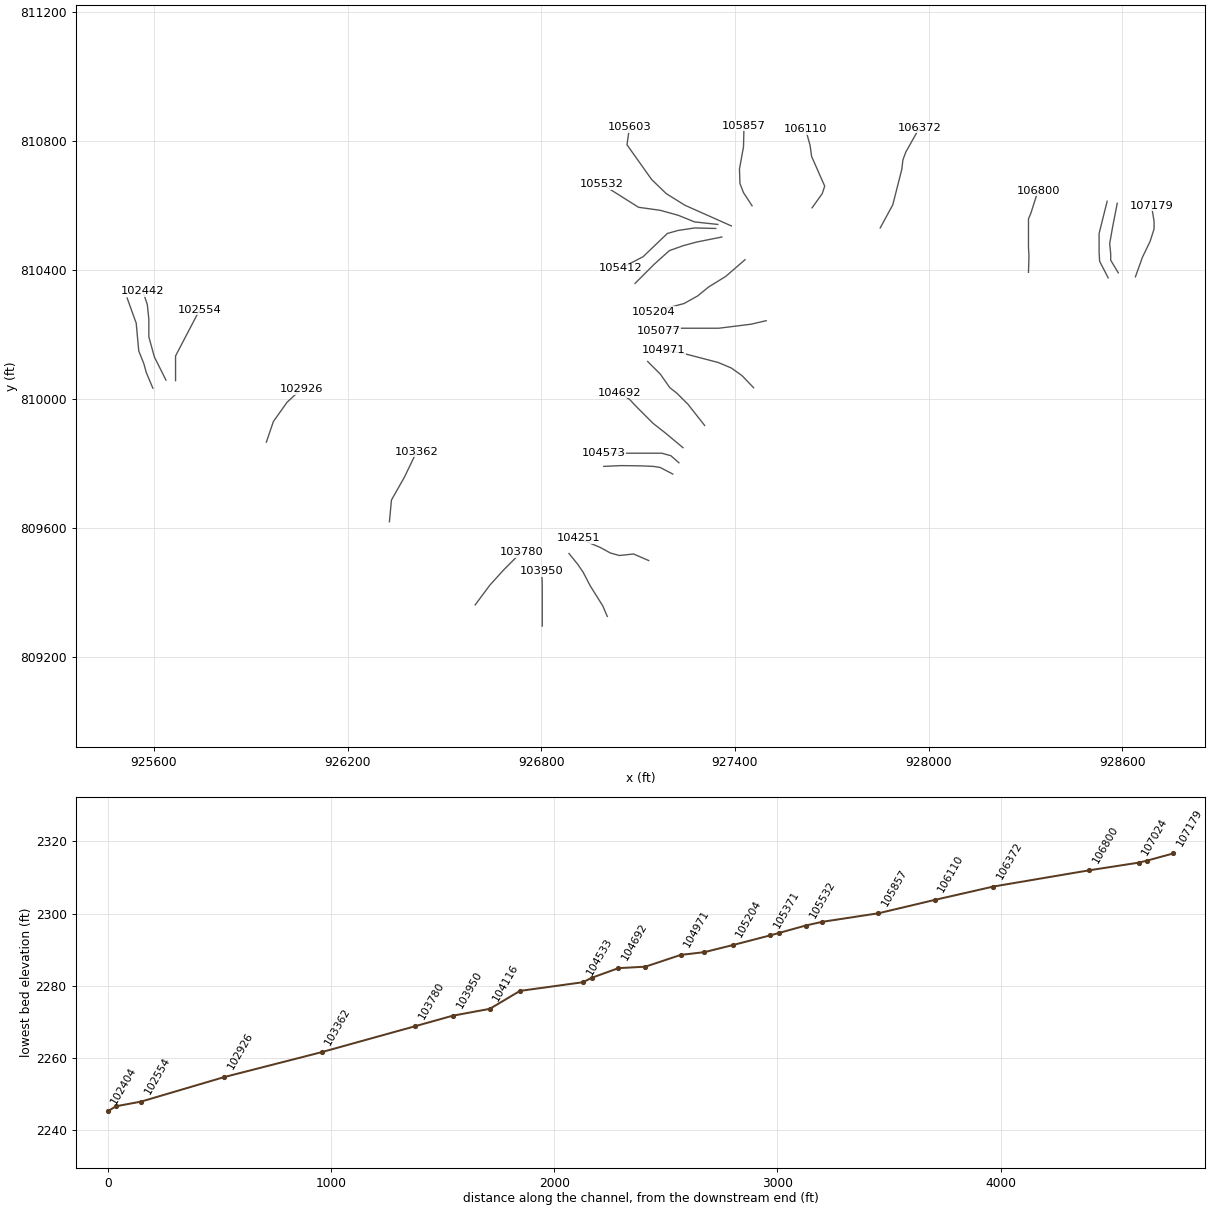
HEC-RAS study lds_big_laurel_crk.prj: lds_big_laurel_crk

--- lds_big_laurel_crk.g20 (geometry) --- (continued)

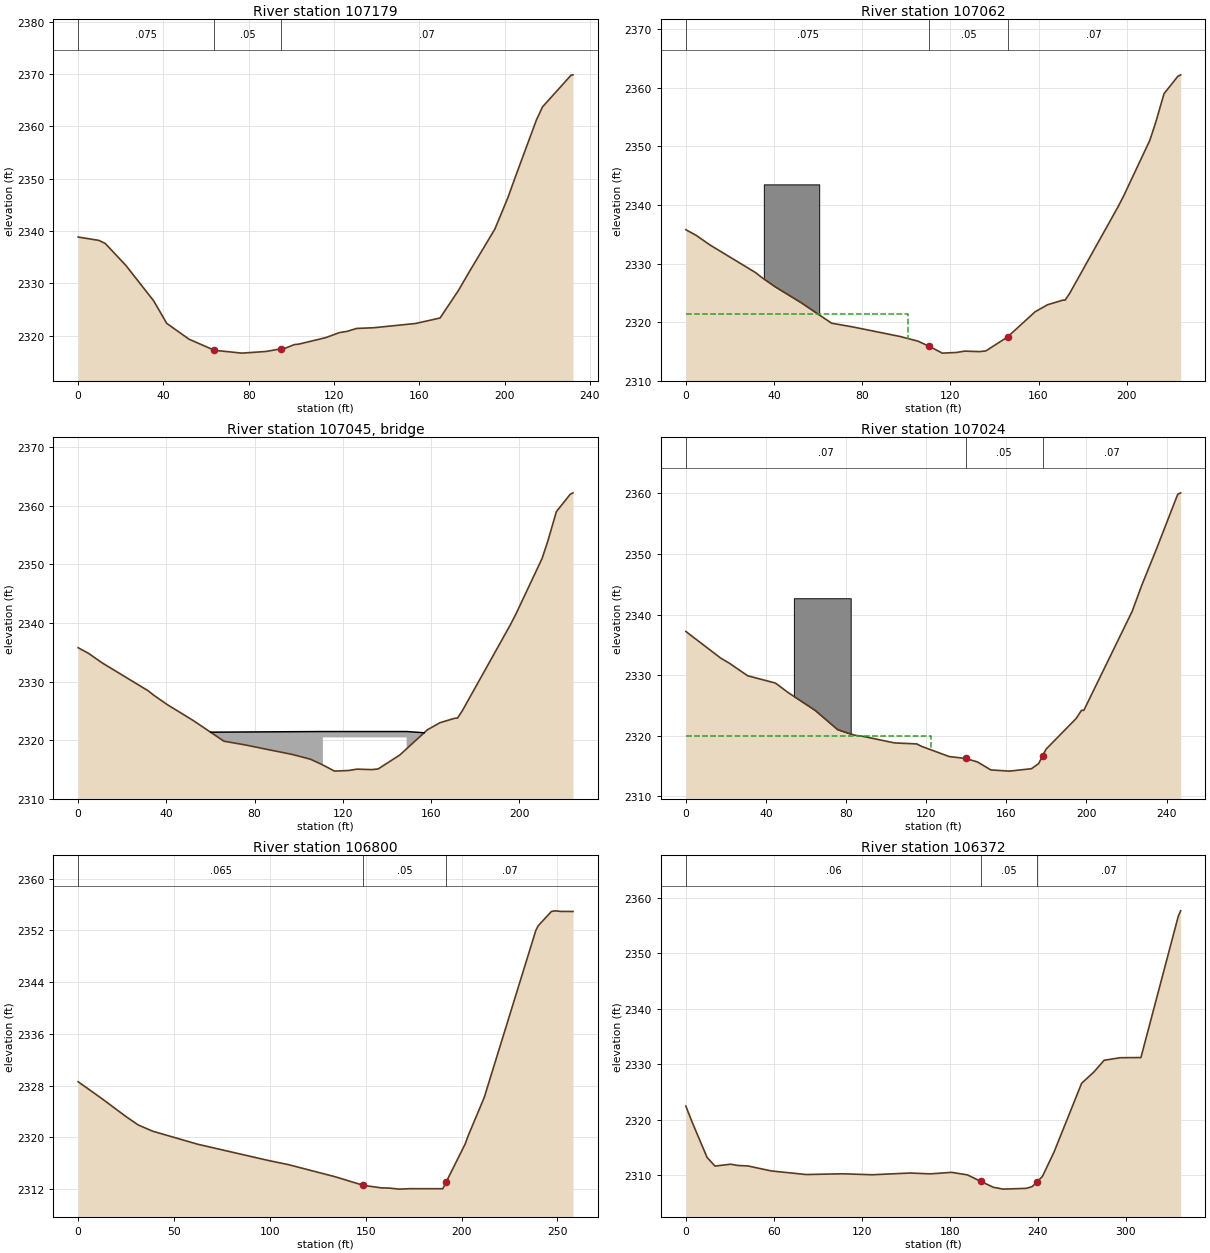
Type RM Length L Ch R = 1 ,107179  ,92.89,116.81,119.35
BEGIN DESCRIPTION:
107101.0
END DESCRIPTION:
XS GIS Cut Line= 6
  928640.6608941  810377.6197078   928662.536261  810438.5571325
  928685.9734957  810486.9944939   928698.473559  810526.0575759
   928698.473559  810549.4948106  928690.6611474   810597.932172
#Sta/Elev= 30
       0 2338.87    9.71 2338.23   12.72 2337.64   22.44 2333.42   35.41 2326.69
   41.55 2322.38   52.01 2319.36   63.84 2317.25   76.72  2316.7   87.98 2317.01
   95.17 2317.52   96.79 2317.58  101.29 2318.32  103.59 2318.43  116.12 2319.66
  122.55 2320.62  126.29 2320.87  130.54 2321.41  138.69 2321.55  158.37 2322.37
  169.73 2323.41  178.34 2328.66  183.01 2331.94  195.39 2340.36  201.49 2346.33
  205.16 2350.49  214.95 2361.26  217.79 2363.73  231.14 2369.77  232.07 2369.85
#Mann= 3 , 0 , 0
       0    .075       0   63.84     .05       0   95.17     .07       0
Bank Sta=63.84,95.17
Exp/Cntr=0.5,0.3

Type RM Length L Ch R = 1 ,107062  ,36.67,38.41,33.64
BEGIN DESCRIPTION:
106984.2
END DESCRIPTION:
XS GIS Cut Line= 6
  928587.5358809  810390.1197712  928564.0986462   810429.181829
  928564.0986462  810449.4943039  928560.9738865  810480.7449743
  928570.3481658  810533.8699875  928584.4111211  810605.7445835
#Sta/Elev= 30
       0 2335.77     4.7 2334.81   10.91 2333.18   31.72 2328.44   34.36 2327.65
   40.55 2326.04    52.2 2323.36   66.13 2319.83   75.57 2319.21   97.27 2317.56
  105.38 2316.76  110.52 2315.87  116.33 2314.73  122.74 2314.84  126.44 2315.07
  133.16 2314.99  136.07  2315.1  145.91 2317.48   158.4 2321.77  164.08 2322.98
   170.9 2323.75  172.06 2323.77  174.21 2324.99  196.07 2339.69  198.68  2341.6
  210.42 2350.97  213.07 2353.98  216.92 2358.97  223.17 2361.92  224.46 2362.18
#Mann= 3 , 0 , 0
       0    .075       0  110.52     .05       0  145.91     .07       0
#XS Ineff= 2 , 0
       0     101 2321.48     159       0 2321.48
Permanent Ineff=
       F       F
#Block Obstruct= 1 ,-1
   35.37    60.52343.504
Bank Sta=110.52,145.91
Exp/Cntr=0.5,0.3

Type RM Length L Ch R = 3 ,107045  ,,,
Node Photo=H:\PROJ\06-0741\CE\GIS\DATA\FRENCH_BROAD_RIVER\SHAPEFILES\survey_data\photos\FBSTR_1773.JPG
BEGIN DESCRIPTION:
106966  FBSTR_1773
END DESCRIPTION:
Bridge Culvert--1,0,-1,-1, 0
Deck Dist Width WeirC Skew NumUp NumDn MinLoCord MaxHiCord MaxSubmerge Is_Ogee
12,10,2.6,0, 7, 7, , , 0.95, 0, 1,1,,
   60.11     111     111     130     149     149  156.93
 2321.37 2321.48 2321.48 2321.48 2321.48 2321.48 2321.27
                 2320.48 2320.48 2320.48
    74.2  137.51  137.51  156.51  175.51  175.51  190.57
 2321.45 2321.48 2321.48 2321.48 2321.48 2321.48 2321.39
                 2320.48 2320.48 2320.48
BR Coef=-1 , 0 , 0 ,, 0 ,,,0.8,0,,0,
WSPro=,,,, 1 ,,,, 0 ,,,, 0 ,,,,-1 ,-1 ,-1 , 0 , 0 , 0 , 0 , 0
BC Design=,, 0 ,, 0 ,,,,,,

Type RM Length L Ch R = 1 ,107024  ,221.62,223.23,218.89
BEGIN DESCRIPTION:
106945.8
END DESCRIPTION:
XS GIS Cut Line= 6
  928556.2862347   810374.494948   928529.723216  810426.0570692
  928528.1613482  810455.7448476  928528.1613482  810477.6202145
  928528.1613482  810511.9946206  928553.1614749  810611.9951273
#Sta/Elev= 30
       0 2337.21   17.42 2332.81   21.68 2331.98    30.9 2329.89   44.76 2328.69
   51.22 2327.09   64.53 2324.19   75.71 2321.02   84.12 2320.09   88.38  2319.9
  104.15 2318.81  115.32 2318.64  117.56 2318.26  131.44 2316.56  139.68 2316.24
  145.58 2315.67  152.28 2314.35  161.51 2314.15  172.57 2314.55  176.14 2315.39
  178.112316.652  179.87 2317.78  194.93 2322.86  197.53 2324.19  198.72 2324.19
  222.87 2340.55  227.53 2344.75  234.77 2350.66  245.62 2359.88  247.06  2360.1
#Mann= 3 , 0 , 0
       0     .07       0  139.68     .05       0  178.11     .07       0
#XS Ineff= 2 , 0
       0  122.51    2320  190.51       0    2320
Permanent Ineff=
       F       F
#Block Obstruct= 1 ,-1
   53.93    82.32342.694
Bank Sta=139.68,178.11
Exp/Cntr=0.5,0.3

Type RM Length L Ch R = 1 ,106800  ,444.54,428.38,426.01
BEGIN DESCRIPTION:
106722.6
END DESCRIPTION:
XS GIS Cut Line= 6
  928309.4107519  810391.6826631  928310.9736439  810443.2447843
  928309.4107519   810468.244911  928309.4107519  810557.3072222
  928317.2231635  810576.0568051  928339.0985303  810644.8076655
#Sta/Elev= 25
       0 2328.61   12.21 2326.04   25.11 2323.19   31.35 2321.93   38.93 2320.96
   62.36 2318.95   99.35 2316.43  109.64  2315.8  134.12 2313.92  148.86 2312.59
  158.37  2312.2  162.33 2312.17  167.58 2312.01  172.85 2312.08  190.24 2312.07
  191.922313.065  201.84 2318.94   203.6 2320.35  211.83 2326.16  238.78 2352.01
  240.05 2352.73  246.89 2354.93  248.83 2355.03  251.84 2354.94  258.16 2354.93
#Mann= 3 , 0 , 0
       0    .065       0  148.86     .05       0  191.92     .07       0
Bank Sta=148.86,191.92
Exp/Cntr=0.3,0.1

Type RM Length L Ch R = 1 ,106372  ,214.62,262.41,310.23
BEGIN DESCRIPTION:
106294.2
END DESCRIPTION:
XS GIS Cut Line= 6
  927850.0362407  810529.1823357  927889.0982985  810601.0569317
   927917.223185  810711.9946098   927920.348969  810740.1194963
  927929.7232483  810765.1196229  927971.9110901   810840.120003
#Sta/Elev= 30
       0 2322.48    4.34 2319.56   14.49 2313.23   19.88 2311.67   30.53 2312.01
   35.38 2311.78   42.21  2311.7    58.4 2310.79   81.99 2310.15  107.05 2310.28
  126.97 2310.11  152.91 2310.42  166.52 2310.27  181.24 2310.54  192.04 2310.08
  201.06 2308.91  209.64 2307.85  216.34 2307.52  232.06 2307.66  236.12 2307.98
  239.182308.784  243.05  2309.8  250.94 2314.17  269.79 2326.59  278.17 2328.62
  285.13 2330.73  296.03 2331.19   310.2 2331.22  335.71 2356.71   337.3 2357.65
#Mann= 3 , 0 , 0
       0     .06       0  201.06     .05       0  239.18     .07       0
Bank Sta=201.06,239.18
Exp/Cntr=0.3,0.1

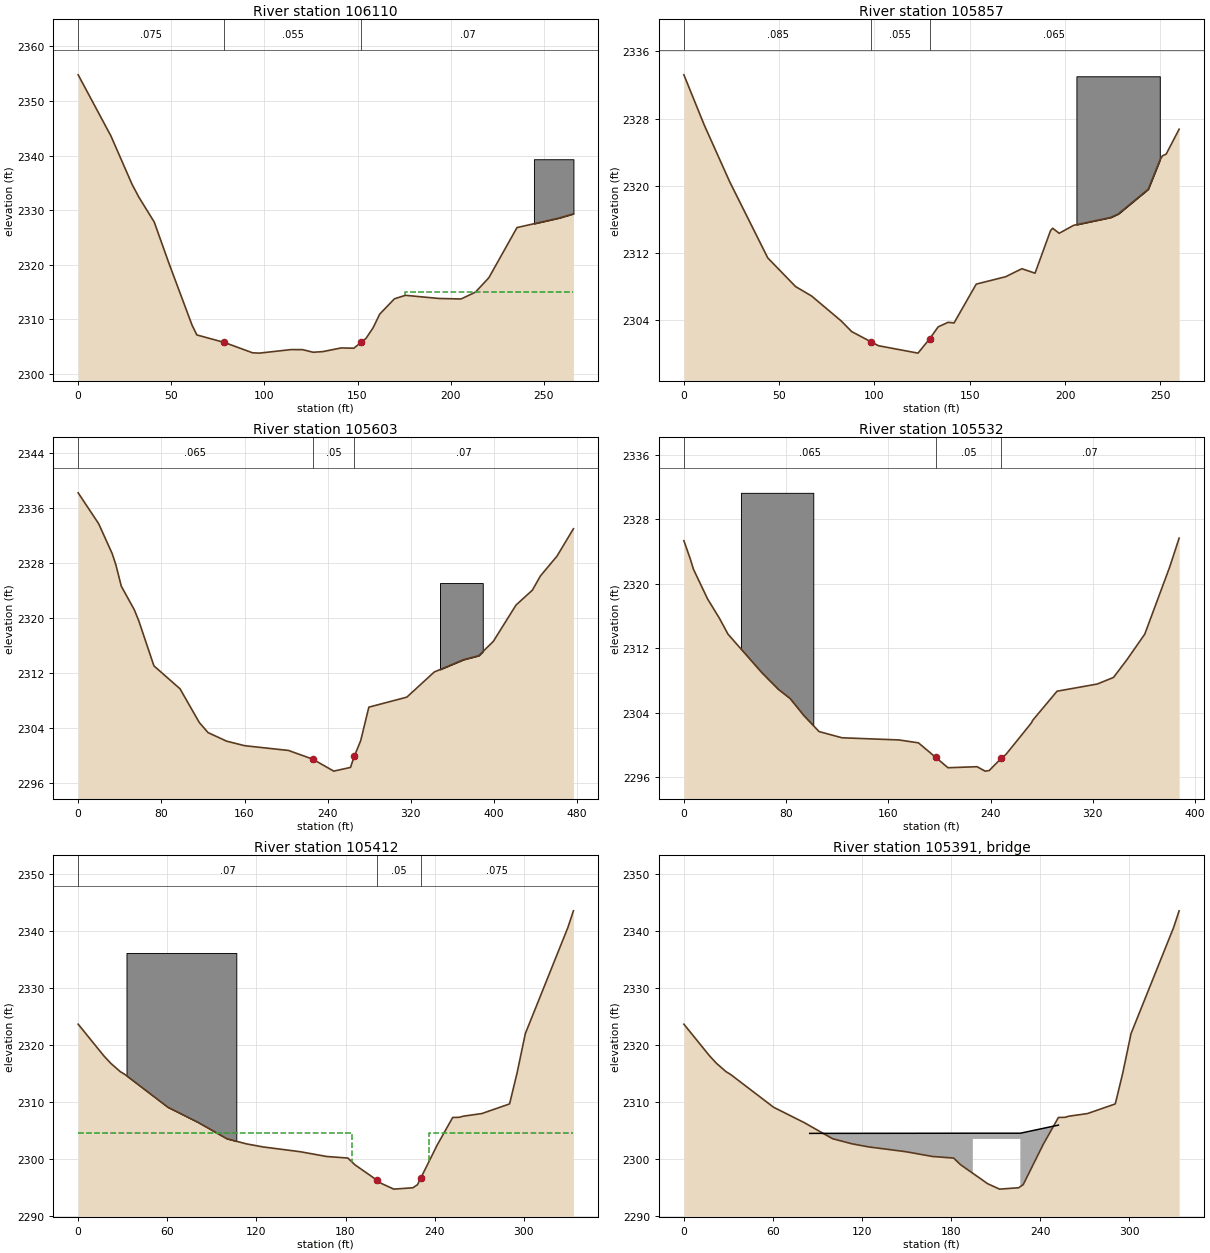
Type RM Length L Ch R = 1 ,106110  ,239.77,252.43,207.01
BEGIN DESCRIPTION:
106031.8
END DESCRIPTION:
XS GIS Cut Line= 6
  927639.0990801  810591.6826524  927670.3487264   810635.432362
  927678.1611379  810658.8695967  927637.5361881  810751.0576918
  927632.8485364  810785.4320978   927618.785581  810835.4323512
#Sta/Elev= 30
       0  2354.8    17.6 2343.59   28.94 2334.74   32.56 2332.41   40.84 2327.84
   48.71 2320.31   61.15 2308.95   63.73 2307.15   78.482305.779   93.65 2303.88
   97.29 2303.82  114.34 2304.47  120.49 2304.46  126.18 2303.98  131.38  2304.1
  141.21 2304.77  148.05 2304.72  152.03 2305.82   154.6 2306.54  158.37 2308.46
  161.94 2310.97  169.82 2313.77  175.76 2314.41  193.76 2313.83   205.6 2313.74
  213.33 2314.99  220.53 2317.63  235.65 2326.82  257.96 2328.54  265.95 2329.34
#Mann= 3 , 0 , 0
       0    .075       0   78.48    .055       0  152.03     .07       0
#XS Ineff= 2 , 0
       0                  175.76       0    2315
Permanent Ineff=
       F       F
#Block Obstruct= 1 ,-1
  244.74  265.952339.337
Bank Sta=78.48,152.03
Exp/Cntr=0.3,0.1

Type RM Length L Ch R = 1 ,105857  ,151.6,254.49,356.69
BEGIN DESCRIPTION:
105779.3
END DESCRIPTION:
XS GIS Cut Line= 6
   927453.161022   810597.932172  927426.5990275  810638.5571218
   927415.660832  810666.6820082  927414.0989642  810711.9946098
  927426.5990275  810780.7444461  927428.1608954  810846.3695226
#Sta/Elev= 30
       0 2333.19   10.68 2327.23   24.07 2320.47   44.03 2311.43   58.61 2308.03
   67.12 2306.89   82.57 2303.94   88.04 2302.68   98.21 2301.46  102.09    2301
  122.84 2300.12  128.922301.808  133.43 2303.24  138.61 2303.78  141.77 2303.71
   153.4 2308.32  168.85  2309.2  177.35 2310.15  184.26 2309.62  192.38 2314.67
  193.52 2314.96  196.92 2314.36  204.55 2315.31  223.97 2316.24  227.96 2316.66
  243.67  2319.6  249.71 2323.01  251.07 2323.56  253.06 2323.77  259.87 2326.73
#Mann= 3 , 0 , 0
       0    .085       0   98.21    .055       0  128.92    .065       0
#Block Obstruct= 1 ,-1
  205.97  249.722333.017
Bank Sta=98.21,128.92
Exp/Cntr=0.3,0.1

Type RM Length L Ch R = 1 ,105603  ,33.93,70.95,134.45
BEGIN DESCRIPTION:
105524.9
END DESCRIPTION:
XS GIS Cut Line= 6
  927389.0988375  810535.4318553  927245.3486212  810599.4950639
  927187.5359563   810635.432362  927142.2233547  810679.1820716
  927065.6611069  810786.9949898  927073.4735185  810841.6818708
#Sta/Elev= 30
       0 2338.23   19.69 2333.74   32.67  2329.4   36.34 2327.71   41.46 2324.64
   53.92 2321.23   58.27 2319.61   72.87 2313.04   97.93 2309.71  116.46 2304.81
   124.9 2303.33   142.8 2302.08  160.18 2301.42  202.26 2300.73  225.48 2299.47
  245.82 2297.72  261.92 2298.26  265.54 2299.87   271.7 2302.14  279.58 2307.03
  316.12 2308.49  342.49 2312.15  370.56 2313.94  385.25 2314.52  399.27  2316.6
   421.1 2321.89  436.86 2324.06  444.55 2326.12  460.61 2329.03  476.35    2333
#Mann= 3 , 0 , 0
       0    .065       0  225.48     .05       0  265.54     .07       0
#Block Obstruct= 1 ,-1
     348  389.152325.092
Bank Sta=225.48,265.54
Exp/Cntr=0.3,0.1

Type RM Length L Ch R = 1 ,105532  ,20.97,120.19,257.46
BEGIN DESCRIPTION:
105453.9
END DESCRIPTION:
XS GIS Cut Line= 6
  927346.9109957   810540.119507  927275.0363997  810547.9319186
  927225.0361463  810568.2443935  927168.7863734  810583.8702408
  927101.5984049  810593.2445202  926987.5359671  810665.1201404
#Sta/Elev= 30
       0 2325.33    4.99 2323.08    7.54 2321.77   18.52 2318.11   27.79 2315.71
   34.54 2313.73   60.83 2308.98   73.81  2306.9   83.06 2305.75   93.81 2303.64
  105.78 2301.64  123.73 2300.87  168.32  2300.6  183.54 2300.24  197.052298.439
  206.67 2297.15  229.36 2297.28  235.71 2296.73  238.89  2296.8  248.382298.329
   252.1 2298.82  271.89 2302.71  272.89 2303.03  291.99 2306.65  323.43 2307.54
  336.17 2308.36  346.71 2310.57  360.65 2313.74  380.09 2322.05  387.52 2325.65
#Mann= 3 , 0 , 0
       0    .065       0  197.05     .05       0  248.38     .07       0
#Block Obstruct= 1 ,-1
   44.64  101.242331.275
Bank Sta=197.05,248.38
Exp/Cntr=0.5,0.3

Type RM Length L Ch R = 1 ,105412  ,44.73,40.59,52.59
BEGIN DESCRIPTION:
105333.7
END DESCRIPTION:
XS GIS Cut Line= 6
  927340.6614762  810527.6194437  927275.0363997  810529.1823357
  927223.4732543  810521.3699241  927190.6607161  810511.9946206
  927115.6613603  810440.1200245   927046.911524  810404.1827265
#Sta/Elev= 30
       0 2323.61   17.23 2318.07   21.89 2316.76   28.33 2315.29   31.51 2314.78
   60.38 2309.04   80.95 2306.35  100.17 2303.51  113.31 2302.61  124.57 2302.07
  149.35 2301.24  167.29  2300.4  181.61 2300.12   186.4 2298.93  200.98 2296.28
   204.3 2295.65  212.56 2294.67   225.4 2294.91  228.47 2295.45  230.69 2296.61
  241.68 2302.38  252.17 2307.24  256.61 2307.27  259.35 2307.47  271.79 2307.93
  290.47 2309.62  295.47 2314.99  301.09 2321.96  329.71 2340.55  333.47  2343.5
#Mann= 3 , 0 , 0
       0     .07       0  200.98     .05       0  230.69    .075       0
#XS Ineff= 2 , 0
       0  184.55 2304.48  236.55       0 2304.48
Permanent Ineff=
       F       F
#Block Obstruct= 1 ,-1
   32.53  106.47 2336.11
Bank Sta=200.98,230.69
Exp/Cntr=0.5,0.3

Type RM Length L Ch R = 3 ,105391  ,,,
Node Photo=H:\PROJ\06-0741\CE\GIS\DATA\FRENCH_BROAD_RIVER\SHAPEFILES\survey_data\photos\FBSTR_1278B.JPG
BEGIN DESCRIPTION:
105314  FBSTR_1278B
END DESCRIPTION:
Bridge Culvert--1,0,-1,-1, 0
Deck Dist Width WeirC Skew NumUp NumDn MinLoCord MaxHiCord MaxSubmerge Is_Ogee
15,12,2.6,0, 7, 7, , , 0.95, 0, 1,1,,
   84.72  194.55  194.55  210.55  226.55  226.55  252.17
 2304.45 2304.48 2304.48 2304.48 2304.48 2304.48  2305.9
                 2303.48 2303.48 2303.48
  111.56  177.56  177.56  193.56  209.56  209.56  237.96
  2304.4 2304.48 2304.48 2304.48 2304.48 2304.48 2305.86
                 2303.48 2303.48 2303.48
BR Coef=-1 , 0 , 0 ,, 0 ,,,0.8,0,,0,
WSPro=,,,, 1 ,,,, 0 ,,,, 0 ,,,,-1 ,-1 ,-1 , 0 , 0 , 0 , 0 , 0
BC Design=,, 0 ,, 0 ,,,,,,

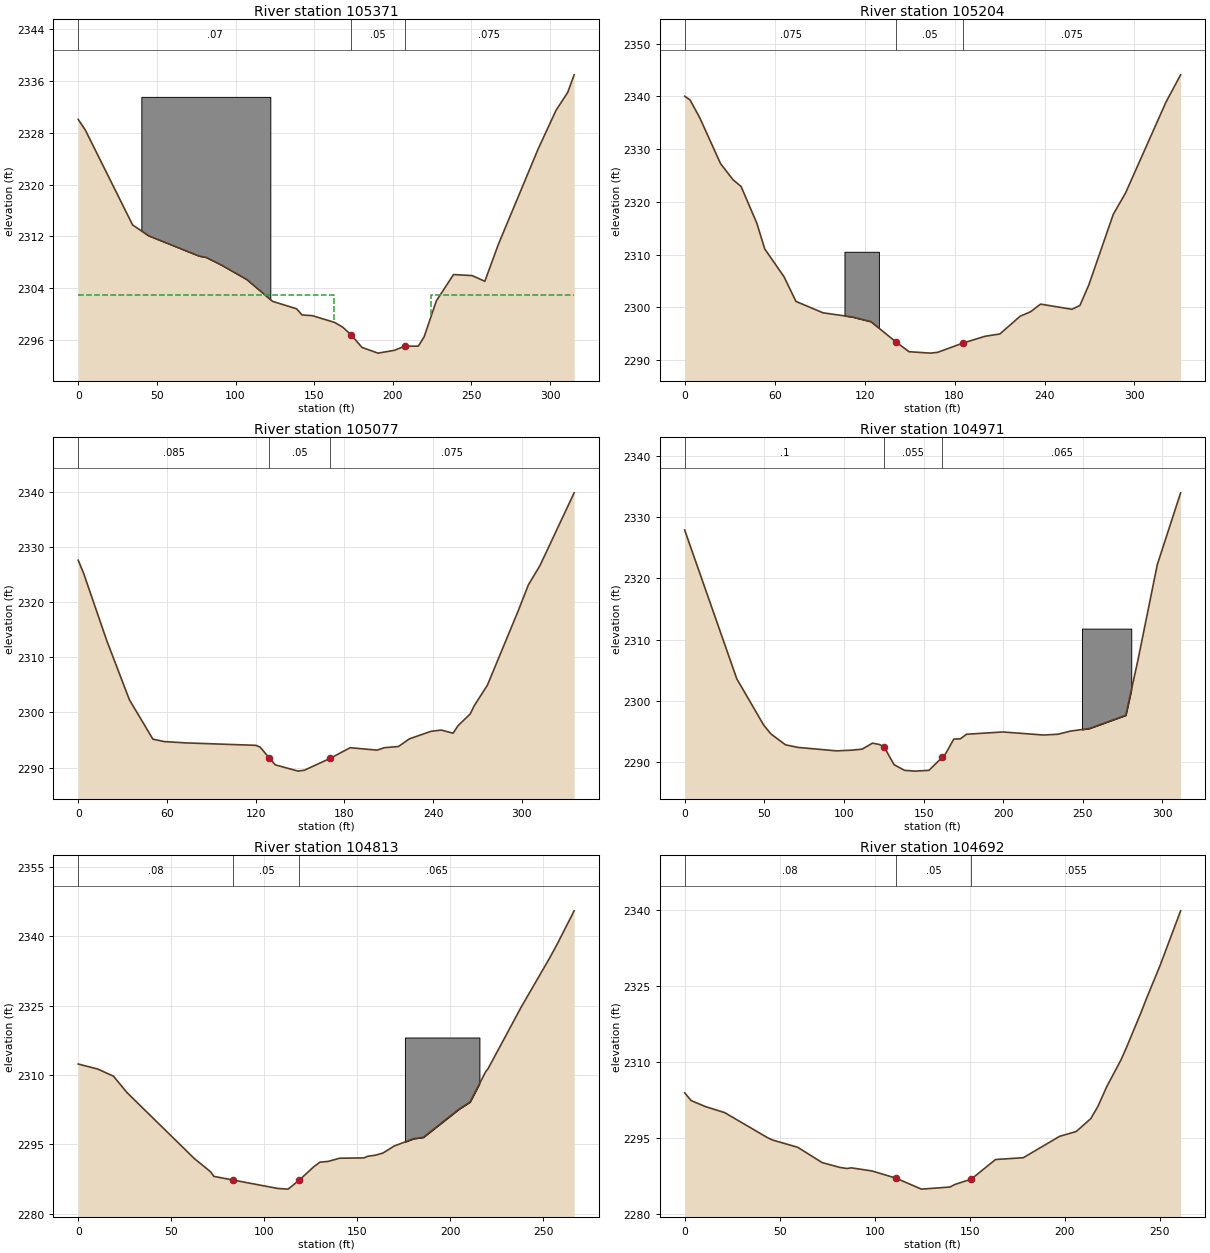
Type RM Length L Ch R = 1 ,105371  ,141.55,166.9,140.81
BEGIN DESCRIPTION:
105293.1
END DESCRIPTION:
XS GIS Cut Line= 6
  927359.4110591  810501.0574492  927281.2859193  810485.4326261
  927240.6609695  810474.4944306  927196.9112599  810458.8696074
  927150.0357663  810416.6817656  927090.6612336  810357.3072329
#Sta/Elev= 30
       0 2330.08     4.5 2328.45   34.57 2313.78   44.79  2312.1   76.71 2308.98
   81.25 2308.77   91.03 2307.58  107.04 2305.36  123.54 2301.97  138.83 2300.82
  142.27 2299.87  148.81 2299.76  162.93 2298.72   168.2 2297.97  173.53 2296.78
   180.4 2294.85  190.57 2293.97  200.92  2294.4  207.51 2295.04  216.22 2295.05
  219.88 2296.48  227.68 2302.05  238.59 2306.11   250.4 2305.95  258.49 2305.07
  267.08 2310.77  292.36 2325.51  303.77  2331.5  311.15 2334.24  315.26 2336.97
#Mann= 3 , 0 , 0
       0     .07       0  173.53     .05       0  207.51    .075       0
#XS Ineff= 2 , 0
       0  162.56    2303  224.56       0    2303
Permanent Ineff=
       F       F
#Block Obstruct= 1 ,-1
   40.13  122.112333.565
Bank Sta=173.53,207.51
Exp/Cntr=0.5,0.3

Type RM Length L Ch R = 1 ,105204  ,173.76,126.77,71.4
BEGIN DESCRIPTION:
105126.2
END DESCRIPTION:
XS GIS Cut Line= 6
  927431.2856551   810430.744721  927371.9111224  810379.1825998
  927318.7861093  810346.3700616  927284.4106791  810318.2451751
  927242.2238614  810294.8069162  927148.4738985  810269.8067896
#Sta/Elev= 30
       0 2340.05    3.59 2339.35   10.08 2335.95   23.94 2327.26   32.29 2324.19
   37.66 2322.91   48.15 2315.93    53.4 2311.07   66.21 2305.82   74.23 2301.11
   92.26 2298.95   111.8 2298.16  124.25 2297.27  141.08 2293.39  149.65 2291.57
  163.95  2291.3  168.72 2291.45  185.49  2293.2  200.27 2294.49  210.27 2294.94
  223.77 2298.31  230.71 2299.15  237.36  2300.6   258.3 2299.62  263.62 2300.35
  269.58 2304.26  285.84 2317.62  294.06  2321.7  320.98 2338.91  330.78 2344.11
#Mann= 3 , 0 , 0
       0    .075       0  141.08     .05       0  185.49    .075       0
#Block Obstruct= 1 ,-1
  106.58  129.532310.533
Bank Sta=141.08,185.49
Exp/Cntr=0.3,0.1

Type RM Length L Ch R = 1 ,105077  ,178.79,106.37,74.38
BEGIN DESCRIPTION:
104999.5
END DESCRIPTION:
XS GIS Cut Line= 6
  927496.9107316  810241.6819031  927450.0362622  810230.7447317
  927350.0357555  810218.2446684  927289.0983308  810218.2446684
   927212.536083  810218.2446684  927164.0987216  810210.4322568
#Sta/Elev= 30
       0 2327.62    3.56 2325.33   19.24 2313.09   34.66 2302.28   50.54 2295.15
   58.23 2294.71    73.1 2294.47  120.18 2294.03  123.03 2293.71  129.082291.799
  133.28 2290.49  148.79 2289.35  153.06 2289.52  170.57 2291.69  183.95  2293.6
  202.12 2293.16  207.08  2293.6  216.63 2293.82  224.08 2295.21  238.59 2296.57
  245.61  2296.8  253.57 2296.23   256.9 2297.58  265.21 2299.74  267.96 2301.25
  276.77 2304.93  297.73 2318.49   304.5 2323.14  312.34 2326.64  335.48 2339.85
#Mann= 3 , 0 , 0
       0    .085       0  129.08     .05       0  170.57    .075       0
Bank Sta=129.08,170.57
Exp/Cntr=0.3,0.1

Type RM Length L Ch R = 1 ,104971  ,189.23,158.16,76.89
BEGIN DESCRIPTION:
104893.1
END DESCRIPTION:
XS GIS Cut Line= 6
  927457.8486738  810033.8695023  927421.9113758  810071.3696923
  927389.0988375   810094.806927  927348.4738877  810111.9946421
  927240.6609695  810140.1195286  927178.1606528  810151.0577241
#Sta/Elev= 30
       0 2327.86   32.72 2303.62   49.62 2296.08   54.14 2294.64   63.29 2292.87
   71.22 2292.44   95.42 2291.88  105.11    2292  111.42 2292.16  117.91 2293.14
  122.41 2292.91  125.39 2292.46  131.48 2289.63     138 2288.71  144.61 2288.58
  153.38 2288.71  161.81 2290.85  163.89 2291.44  168.96  2293.8  173.04 2293.84
  176.98 2294.59  199.79 2294.96  225.45 2294.46  234.37 2294.59  242.23  2295.1
  254.03 2295.52  276.96 2297.68  284.51 2306.57  296.74 2322.22  311.38 2333.92
#Mann= 3 , 0 , 0
       0      .1       0  125.39    .055       0  161.81    .065       0
#Block Obstruct= 1 ,-1
  249.43   280.42311.799
Bank Sta=125.39,161.81
Exp/Cntr=0.3,0.1

Type RM Length L Ch R = 1 ,104813  ,106.68,120.58,123.52
BEGIN DESCRIPTION:
104734.9
END DESCRIPTION:
XS GIS Cut Line= 6
  927306.2860459  809916.6823047  927254.7239248  809982.3073811
  927220.3484946  810016.6817872  927198.4731277  810033.8695023
  927168.7863734  810076.0573441  927129.7232914  810115.1194019
#Sta/Elev= 30
       0 2312.37   10.58 2311.27   18.96 2309.74   26.17 2306.22   62.54  2291.9
   71.09 2289.11   72.96 2288.08   83.46 2287.27  107.27 2285.47   112.9 2285.32
  118.88 2287.27  126.75 2290.18     130 2291.15  134.38 2291.31  140.56    2292
  153.63 2292.07  155.77 2292.43  159.89 2292.66  163.93 2293.13  169.91 2294.63
  180.32 2296.22  185.58 2296.51  204.73  2302.6  210.71 2304.15   219.2 2310.76
  220.25 2311.23  238.18 2324.63   253.4 2335.19  257.64 2338.32  266.72 2345.49
#Mann= 3 , 0 , 0
       0     .08       0   83.46     .05       0  118.88    .065       0
#Block Obstruct= 1 ,-1
   175.7  215.772318.102
Bank Sta=83.46,118.88
Exp/Cntr=0.3,0.1

Type RM Length L Ch R = 1 ,104692  ,54.47,119.61,180.43
BEGIN DESCRIPTION:
104614.3
END DESCRIPTION:
XS GIS Cut Line= 6
  927239.0980775  809847.9324684  927182.8483045  809894.8069378
  927146.9110065  809922.9318242  927092.2231014  809977.6197294
  927075.0364105  809996.3693123  927042.2238722  810018.2446792
#Sta/Elev= 30
       0 2303.94    3.41 2302.41   10.88 2301.23   21.08 2300.03    43.3 2295.15
   46.17 2294.63   59.53 2293.18   72.38 2290.16   81.69 2289.21   85.39    2289
   87.79 2289.12   98.71  2288.5  111.15  2287.1   124.6 2284.92  139.59 2285.33
  142.37 2285.86  150.79 2286.88  163.66 2290.77  178.28 2291.13  197.37 2295.35
  206.13  2296.3  213.79 2298.85  217.57 2301.29  222.25 2305.22   229.6 2310.39
  232.56 2312.89  240.12  2319.7  243.15 2322.62  250.21 2329.05  261.07 2339.89
#Mann= 3 , 0 , 0
       0     .08       0  111.15     .05       0  150.79    .055       0
Bank Sta=111.15,150.79
Exp/Cntr=0.3,0.1

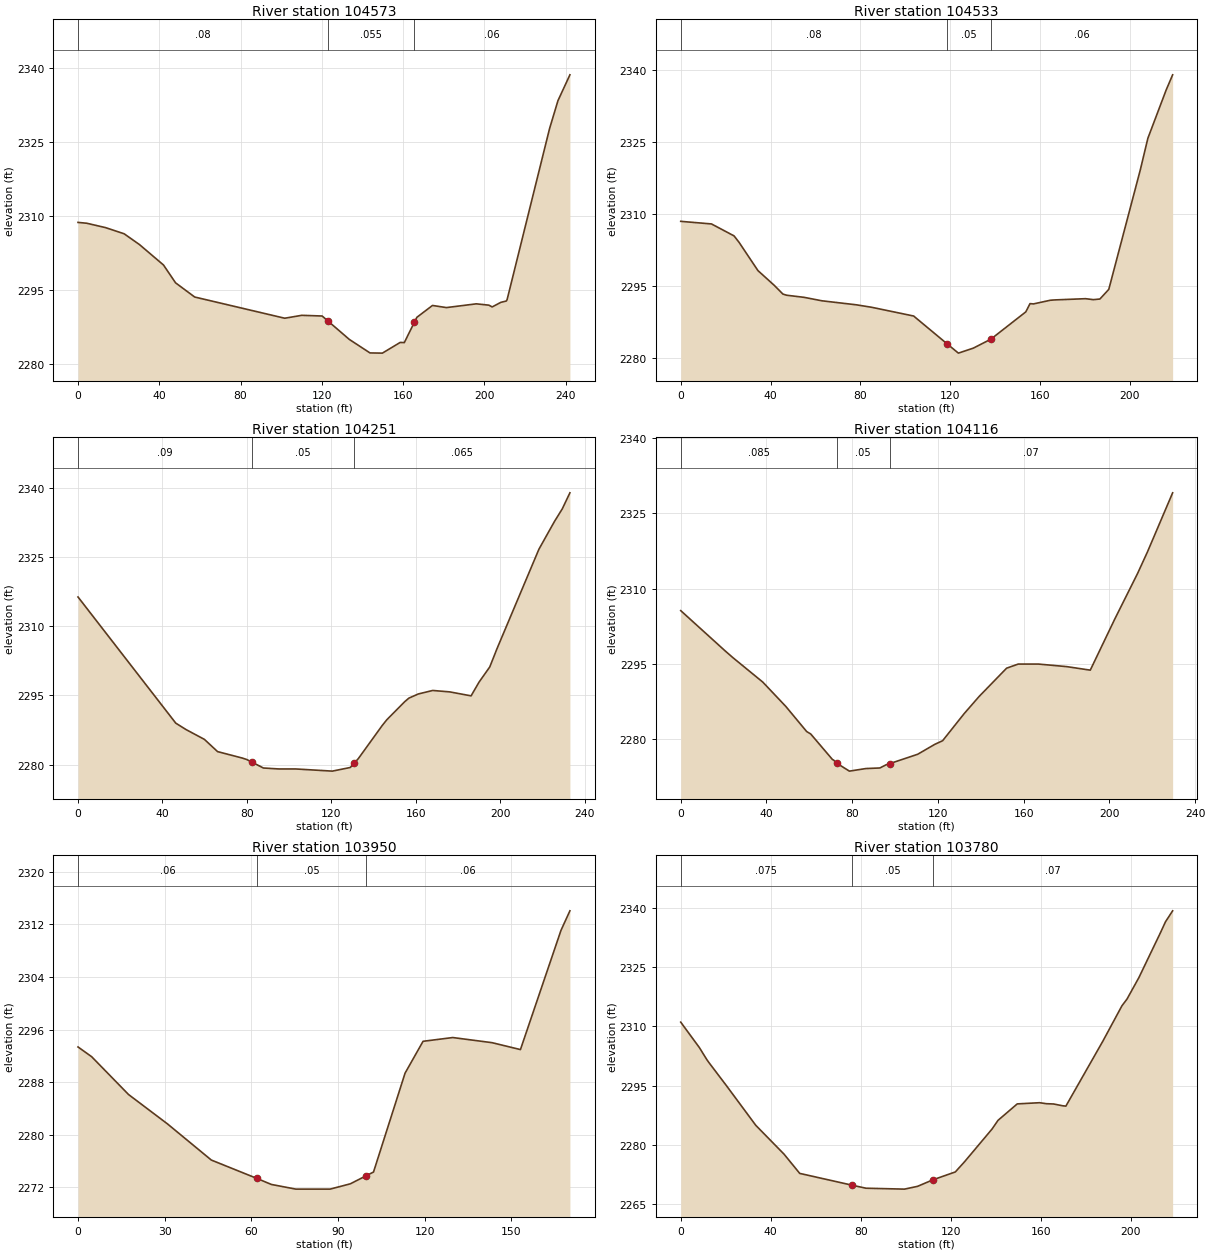
Type RM Length L Ch R = 1 ,104573  ,44.82,39.32,40.67
BEGIN DESCRIPTION:
104494.7
END DESCRIPTION:
XS GIS Cut Line= 4
  927226.5990383  809801.0569748  927201.5989116  809822.9323417
  927173.4740252  809830.7447533  926993.7865108  809830.7447533
#Sta/Elev= 30
       0 2308.76    4.31 2308.59   13.56  2307.7   22.67 2306.46   30.26 2304.26
   42.07 2300.12   48.02  2296.5   57.44 2293.62  101.75 2289.32  110.13 2289.91
  120.15 2289.77  123.182288.695  133.54 2285.02   143.7 2282.28  149.82 2282.24
  158.56 2284.41   160.6 2284.38  165.592288.536  166.79 2289.51  174.46 2291.91
  181.33 2291.48  196.02 2292.24  202.23 2291.97  203.85 2291.61   208.1 2292.54
  210.81 2292.81   211.2 2293.11  232.11 2327.83  236.22 2333.46   242.1  2338.7
#Mann= 3 , 0 , 0
       0     .08       0  123.18    .055       0  165.59     .06       0
Bank Sta=123.18,165.59
Exp/Cntr=0.3,0.1

Type RM Length L Ch R = 1 ,104533  ,281.23,282.45,248.21
BEGIN DESCRIPTION:
104455.4
END DESCRIPTION:
XS GIS Cut Line= 6
  927207.5719038  809766.0998128  927168.2671164   809786.571035
  927147.7969184  809789.8463486  927109.3104473  809791.4840054
  927047.8967809  809792.3033459  926993.8530823  809789.8463486
#Sta/Elev= 30
       0 2308.47    13.7 2307.93   23.75 2305.44   25.98  2304.1    34.4 2298.21
   41.68 2295.13   45.52 2293.32   47.19 2293.08   54.95 2292.64    62.9 2291.92
   78.29 2291.08   85.04 2290.57  103.74 2288.75  118.772282.908  123.68 2281.02
  130.33 2282.06  138.13 2283.92   153.7 2289.61  155.59 2291.33  157.11 2291.27
  164.58 2292.03  166.48  2292.1  180.31 2292.36  183.79 2292.16  186.71 2292.29
  190.67  2294.3  204.71 2319.19  208.08 2325.77  216.22 2335.82  219.11 2338.99
#Mann= 3 , 0 , 0
       0     .08       0  118.77     .05       0  138.13     .06       0
Bank Sta=118.77,138.13
Exp/Cntr=0.3,0.1

Type RM Length L Ch R = 1 ,104251  ,191.75,135.05,71.03
BEGIN DESCRIPTION:
104173.0
END DESCRIPTION:
XS GIS Cut Line= 6
  927132.8490754  809497.9327433  927085.9735818  809518.2452182
  927042.2238722  809513.5575664  927014.0989857   809521.369978
  926982.8483153  809538.5576931   926915.661371  809566.6825795
#Sta/Elev= 30
       0 2316.35   46.28 2289.01   51.09 2287.63   59.84 2285.49   66.08 2282.84
    77.8 2281.44   79.88 2281.13   82.26 2280.58   87.76 2279.29   95.09 2279.08
  103.09 2279.08   120.4 2278.61  128.91  2279.4  130.862280.383   132.7 2281.31
  144.03  2288.5  146.22 2289.75   154.7 2293.67  156.66 2294.43  161.12 2295.33
  167.93 2296.09  176.03 2295.78   186.1 2294.92  189.86 2297.89  194.95 2301.19
  198.42  2305.2  218.22  2326.7  225.61 2332.74  229.27 2335.44  232.89 2338.92
#Mann= 3 , 0 , 0
       0     .09       0   82.26     .05       0  130.86    .065       0
Bank Sta=82.26,130.86
Exp/Cntr=0.3,0.1

Type RM Length L Ch R = 1 ,104116  ,189.9,165.67,115.92
BEGIN DESCRIPTION:
104037.9
END DESCRIPTION:
XS GIS Cut Line= 6
  927004.7236822  809324.4947485  926990.6607269  809357.3072868
  926951.5986691  809419.8076035  926929.7233022  809461.9944211
  926912.5355871  809486.9945477  926885.9735926   809519.807086
#Sta/Elev= 30
       0 2305.62   20.74 2297.59    24.4 2296.23   38.28 2291.38   49.03 2286.53
   58.75 2281.53   60.65 2281.04   70.81 2275.94   71.33 2275.85   72.56 2275.28
   72.93 2275.18   78.69 2273.64   86.33 2274.15   92.93 2274.27   95.66 2274.87
    97.4 2275.12  110.55    2277  118.59 2278.99  122.19  2279.7  132.18 2285.07
  139.24 2288.53  152.03 2294.15  157.44 2294.97  166.87 2294.97  179.93 2294.47
  191.07 2293.76   202.5 2303.94  213.12 2313.01   217.8 2317.37  229.49 2329.09
#Mann= 3 , 0 , 0
       0    .085       0   72.93     .05       0    97.4     .07       0
Bank Sta=72.93,97.4
Exp/Cntr=0.3,0.1

Type RM Length L Ch R = 1 ,103950  ,201.12,169.95,104.27
BEGIN DESCRIPTION:
103872.2
END DESCRIPTION:
XS GIS Cut Line= 4
   926803.160801  809294.8069701   926803.160801   809354.182527
   926803.160801  809419.8076035  926801.5989332   809465.120205
#Sta/Elev= 19
       0 2293.37    4.74 2291.88   17.49 2286.14   30.95 2281.68   46.17 2276.17
   61.94 2273.38   66.97 2272.46   75.44 2271.75   87.29 2271.75   94.31 2272.56
   99.742273.772  102.33 2274.35  113.26 2289.39  119.49 2294.23  129.79  2294.8
  143.38 2294.02  153.21 2292.97  167.25  2311.1  170.34 2314.07
#Mann= 3 , 0 , 0
       0     .06       0   61.94     .05       0   99.74     .06       0
Bank Sta=61.94,99.74
Exp/Cntr=0.3,0.1

Type RM Length L Ch R = 1 ,103780  ,407.33,418.1,432.33
BEGIN DESCRIPTION:
103702.3
END DESCRIPTION:
XS GIS Cut Line= 4
  926595.3484002  809360.4320466  926640.6610018  809421.3694713
  926684.4107114  809469.8068326  926739.0986165  809524.4947378
#Sta/Elev= 30
       0 2311.05    8.28 2304.62   11.59 2301.58   12.31 2300.99   20.26 2295.02
   33.35 2284.95   45.91 2277.65   52.87 2272.79   75.94 2269.83   82.31 2269.04
    99.4 2268.81  105.19 2269.51  112.17 2271.19  122.01 2273.16  126.17 2275.78
  138.33 2284.02  140.97 2286.21  149.51 2290.37  159.46 2290.67  162.47 2290.42
  165.64 2290.35  169.63  2289.9  171.12 2289.81  187.58 2306.27  196.02 2315.18
  198.25 2316.86  203.56 2322.32  213.11 2333.64  215.39 2336.45  218.55 2339.21
#Mann= 3 , 0 , 0
       0    .075       0   75.94     .05       0  112.17     .07       0
Bank Sta=75.94,112.17
Exp/Cntr=0.3,0.1

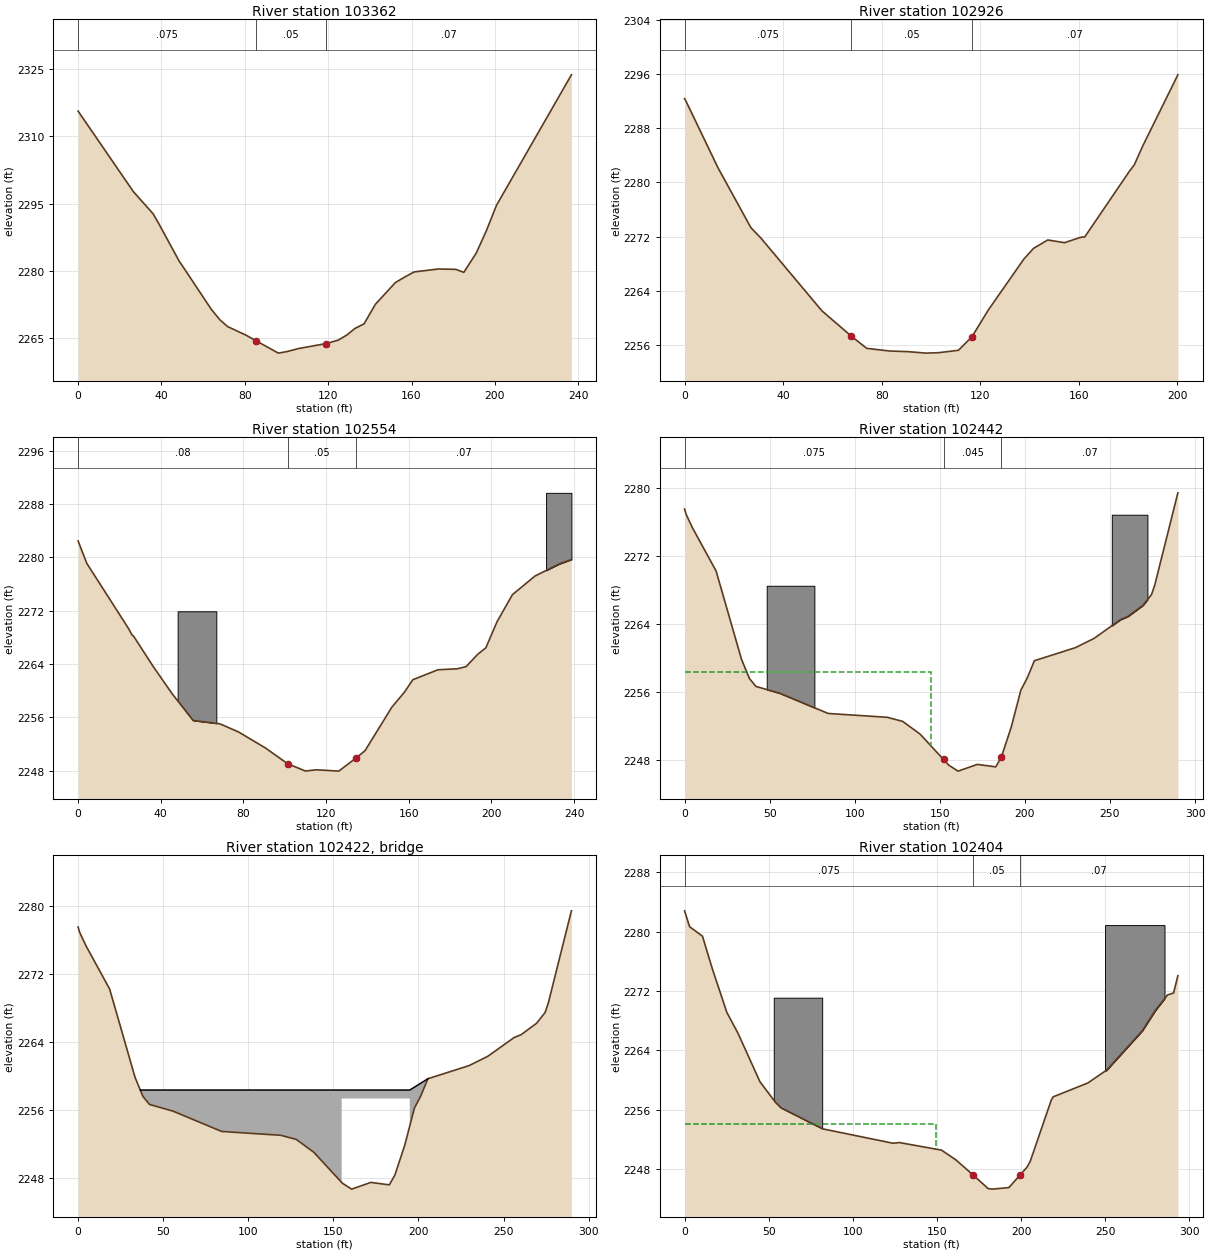
Type RM Length L Ch R = 1 ,103362  ,437.41,436.27,423.2
BEGIN DESCRIPTION:
103284.2
END DESCRIPTION:
XS GIS Cut Line= 4
  926329.7233345  809618.2447007  926335.9738782  809685.4326692
   926376.598828  809757.3072652   926414.099018   809835.432405
#Sta/Elev= 30
       0 2315.64   26.55 2297.66      36 2292.73   38.53 2290.69   48.73 2281.98
    49.5  2281.5   63.89 2271.43   68.01 2269.09   71.73 2267.57   80.85 2265.58
   85.22 2264.44    96.1 2261.64  100.49 2262.01  105.76 2262.66  118.98 2263.77
  124.81 2264.54  129.04  2265.7  132.85 2267.15  137.19 2268.16  142.65 2272.53
   152.2 2277.37  157.01 2278.69  161.26 2279.76  172.91 2280.41  181.25 2280.33
  185.08 2279.66  191.06 2283.98  195.95 2289.01  200.76 2294.62   236.7 2323.73
#Mann= 3 , 0 , 0
       0    .075       0   85.22     .05       0  118.98     .07       0
Bank Sta=85.22,118.98
Exp/Cntr=0.3,0.1

Type RM Length L Ch R = 1 ,102926  ,361.32,371.68,385.55
BEGIN DESCRIPTION:
102847.9
END DESCRIPTION:
XS GIS Cut Line= 4
  925948.4739631  809865.1201835  925970.3483058   809929.182368
  926012.5361476  809988.5569007  926056.2858572  810029.1818505
#Sta/Elev= 26
       0 2292.42     .89 2291.81    13.6 2282.16   26.94 2273.31      31 2271.77
   55.76    2261   67.69 2257.25   73.93 2255.45   83.27 2255.05   90.67 2254.96
   98.01 2254.74  103.28 2254.81  111.15 2255.16  116.63 2257.15  123.27 2261.11
  137.65 2268.63  141.64 2270.25  147.41 2271.49  154.26 2271.09  160.03  2271.8
  161.42 2271.93   162.4 2271.92  180.61 2281.69   182.5 2282.58     186 2285.43
  200.23 2295.94
#Mann= 3 , 0 , 0
       0    .075       0   67.69     .05       0  116.63     .07       0
Bank Sta=67.69,116.63
Exp/Cntr=0.3,0.1

Type RM Length L Ch R = 1 ,102554  ,49.83,112.67,149.5
BEGIN DESCRIPTION:
102476.2
END DESCRIPTION:
XS GIS Cut Line= 5
  925667.2240743  810055.7448692  925667.2240743  810108.8698823
  925667.2240743   810132.307117  925704.7232401  810204.1827372
  925742.2234301  810276.0573333
#Sta/Elev= 30
       0 2282.46    4.25 2279.08   24.52 2269.28   26.02  2268.4   26.88 2268.18
   36.39 2263.62   45.71 2259.48   55.68 2255.55   68.64 2255.05    77.7 2253.82
   90.61 2251.44  101.33 2249.08  109.97 2247.98   115.5 2248.16  126.13 2247.96
  134.52 2249.93  138.84 2251.02  151.85 2257.56  157.95 2259.81  161.98 2261.66
   174.1 2263.15  183.57  2263.3  187.73 2263.62  193.37 2265.47   197.3 2266.44
  202.69 2270.33  210.17 2274.41  221.08  2277.2  232.81 2279.01   238.7 2279.67
#Mann= 3 , 0 , 0
       0     .08       0  101.33     .05       0  134.52     .07       0
#Block Obstruct= 2 ,-1
   48.16   66.892271.917  226.45   238.72289.668
Bank Sta=101.33,134.52
Exp/Cntr=0.5,0.3

Type RM Length L Ch R = 1 ,102442  ,45.33,37.31,52.92
BEGIN DESCRIPTION:
102363.6
END DESCRIPTION:
XS GIS Cut Line= 6
  925637.5362958   810057.306737  925601.5989978  810129.1823572
  925584.4112827  810191.6826739  925584.4112827  810246.3695549
  925579.7236309  810291.6821564  925565.6606756  810333.8699982
#Sta/Elev= 30
       0 2277.48     .91 2276.86    4.62 2275.28   18.54 2270.19   33.45 2259.82
    38.1 2257.56   41.94 2256.62   55.88 2255.82   84.38 2253.44  119.07 2252.99
  128.17 2252.51  138.48    2251  152.182248.029  155.28 2247.36  160.73 2246.66
  172.06 2247.45  182.89 2247.16  186.17 2248.32  191.97 2251.83  197.63 2256.18
  201.39 2257.62  205.58 2259.64  229.74 2261.18   240.7 2262.27  256.13 2264.47
  260.43 2264.83  269.43 2266.16  274.41 2267.42  276.32 2268.54  289.89 2279.38
#Mann= 3 , 0 , 0
       0    .075       0  152.18    .045       0  186.17     .07       0
#XS Ineff= 2 , 0
       0  144.91 2258.31  204.91       0 2258.31
Permanent Ineff=
       F       F
#Block Obstruct= 3 ,-1
   48.28   76.292268.455                          251.06     2722276.808
Bank Sta=152.18,186.17
Exp/Cntr=0.5,0.3

Type RM Length L Ch R = 3 ,102422  ,,,
Node Photo=H:\PROJ\06-0741\CE\GIS\DATA\FRENCH_BROAD_RIVER\SHAPEFILES\survey_data\photos\FBSTR_1278A.JPG
BEGIN DESCRIPTION:
102343.6  FBSTR_1278A
END DESCRIPTION:
Bridge Culvert--1,0,-1,-1, 0
Deck Dist Width WeirC Skew NumUp NumDn MinLoCord MaxHiCord MaxSubmerge Is_Ogee
15,10,2.6,0, 7, 7, , , 0.95, 0, 1,1,,
   36.55  154.91  154.91  169.91  194.91  194.91  205.58
 2258.31 2258.31 2258.31 2258.31 2258.31 2258.31 2259.64
                 2257.31 2257.31 2257.31
   49.43   164.7   164.7   184.7   204.7   204.7   239.6
 2258.29 2258.31 2258.31 2258.31 2258.31 2258.31 2259.59
                 2257.31 2257.31 2257.31
BR Coef=-1 , 0 , 0 ,, 0 ,,,0.8,0,,0,
WSPro=,,,, 1 ,,,, 0 ,,,, 0 ,,,,-1 ,-1 ,-1 , 0 , 0 , 0 , 0 , 0
BC Design=,, 0 ,, 0 ,,,,,,

Type RM Length L Ch R = 1 ,102404  ,27.05,99.36,176.99
BEGIN DESCRIPTION:
102326.2
END DESCRIPTION:
XS GIS Cut Line= 6
   925596.911346  810032.3076345  925576.5988711  810080.7449959
  925568.7864595  810108.8698823  925553.1606122  810147.9319401
  925545.3482007  810233.8694915  925517.2233142  810311.9946313
#Sta/Elev= 30
       0 2282.81    3.01 2280.67   10.65 2279.39    16.5    2275   25.12 2269.12
   31.82 2266.27   44.81 2259.76    53.9 2257.02   57.34 2256.24   82.05 2253.41
  123.79 2251.47  127.67 2251.56  152.68 2250.54  161.31 2249.21   171.6 2247.16
  180.42 2245.35   182.9 2245.28  192.72 2245.49  199.192247.143  203.41 2248.22
  205.36    2249  217.91 2257.29  218.98 2257.72   239.6 2259.59  250.91 2261.35
  271.98 2266.63  279.79 2269.39  287.01 2271.47  290.59 2271.73  293.13 2274.06
#Mann= 3 , 0 , 0
       0    .075       0   171.6     .05       0  199.19     .07       0
#XS Ineff= 2 , 0
       0   149.7    2254   219.7       0    2254
Permanent Ineff=
       F       F
#Block Obstruct= 3 ,-1
   53.01   81.782271.101                          249.85  285.192280.887
Bank Sta=171.6,199.19
Exp/Cntr=0.5,0.3