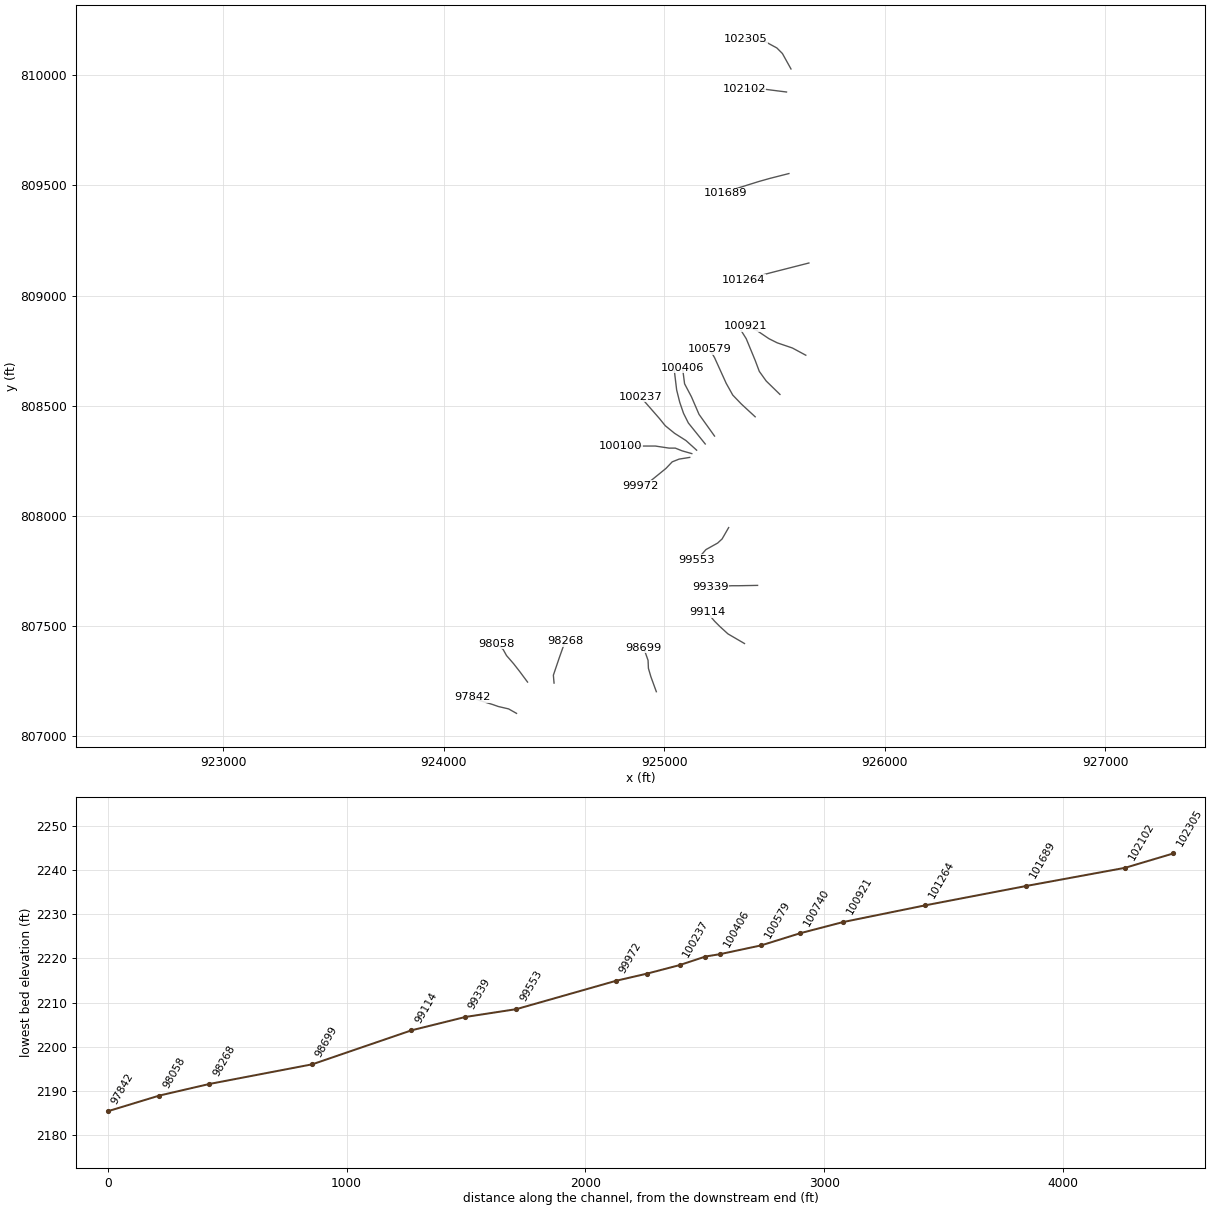
HEC-RAS study lds_big_laurel_crk.prj: lds_big_laurel_crk

--- lds_big_laurel_crk.g20 (geometry) --- (continued)

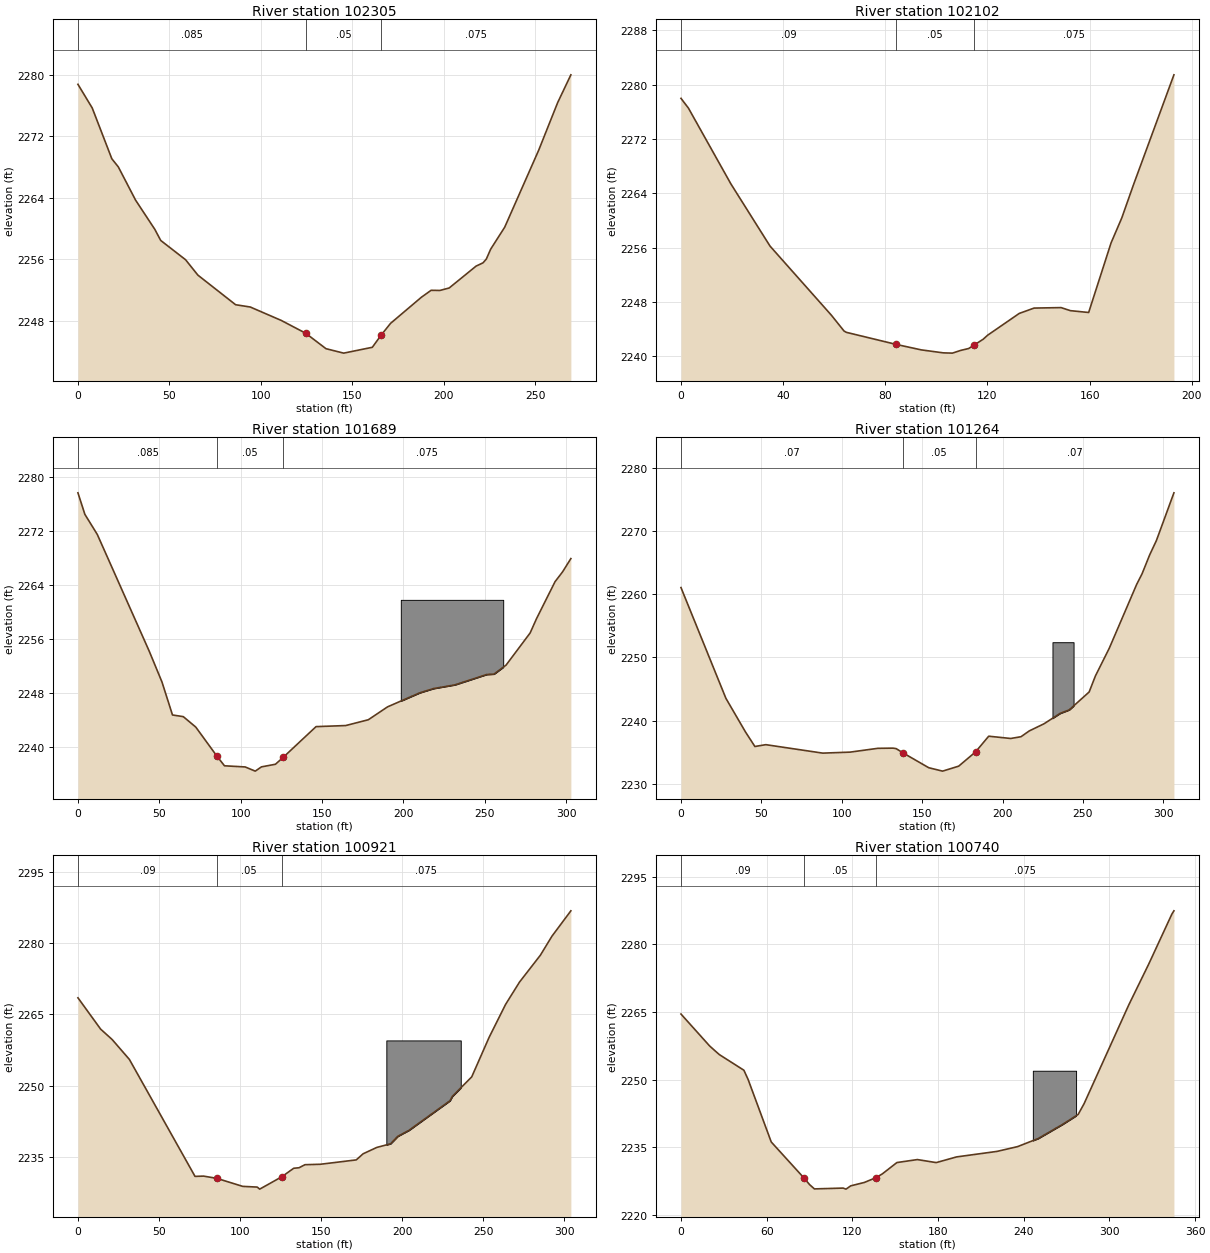
Type RM Length L Ch R = 1 ,102305  ,144.75,202.52,229.89
BEGIN DESCRIPTION:
102226.9
END DESCRIPTION:
XS GIS Cut Line= 6
  925575.0359791  810029.1818505  925535.9739213  810099.4945788
  925510.9737946  810124.4947054  925456.2858895  810154.1824839
  925389.0989452   810168.244415  925367.2235783  810163.5567633
#Sta/Elev= 30
       0 2278.79    7.81 2275.71   18.52 2269.09   22.09 2268.02   31.52 2263.69
   42.02 2259.89   45.25 2258.44   58.86 2255.92   65.56 2253.92   86.19 2250.06
   94.21 2249.76  111.16 2248.01  124.51 2246.34  135.58 2244.33  145.27 2243.75
  160.92 2244.51  165.74  2246.1  170.88 2247.63  187.76 2251.04  193.05 2251.94
  197.84 2251.92  202.92 2252.24  217.62 2255.09  221.42 2255.52  223.25 2256.02
   225.6  2257.3  233.29 2260.17  251.85  2270.2  262.25 2276.42  269.45 2280.03
#Mann= 3 , 0 , 0
       0    .085       0  124.51     .05       0  165.74    .075       0
Bank Sta=124.51,165.74
Exp/Cntr=0.3,0.1

Type RM Length L Ch R = 1 ,102102  ,388.6,413.01,474.79
BEGIN DESCRIPTION:
102024.4
END DESCRIPTION:
XS GIS Cut Line= 3
  925554.7235042  809924.4947162  925456.2858895  809936.9947796
  925362.5359266  809938.5576715
#Sta/Elev= 25
       0 2277.99    2.92 2276.55   19.55 2265.39   34.87 2256.24   58.91 2246.06
   63.85 2243.74   64.74 2243.55   84.18 2241.78   94.04 2240.97  102.67 2240.53
  106.25 2240.49  109.52 2240.89  112.64 2241.17  114.762241.675  118.33 2242.54
  120.04 2243.12  132.42 2246.33  138.24 2247.12  148.81 2247.19  152.47 2246.74
  159.61 2246.47  168.38 2256.71  172.57 2260.38  177.13 2265.24  192.99 2281.45
#Mann= 3 , 0 , 0
       0     .09       0   84.18     .05       0  114.76    .075       0
Bank Sta=84.18,114.76
Exp/Cntr=0.3,0.1

Type RM Length L Ch R = 1 ,101689  ,416.13,424.93,411.14
BEGIN DESCRIPTION:
101611.3
END DESCRIPTION:
XS GIS Cut Line= 5
  925565.6606756  809554.1825162  925479.7231242  809532.3071493
   925429.723895  809518.2452182  925325.0357365  809485.4326799
  925276.5983752   809465.120205
#Sta/Elev= 30
       0 2277.67    4.26 2274.48   11.91 2271.49   43.86 2254.15   51.62 2249.62
   58.09 2244.72   64.74 2244.47   72.41 2242.92   85.49 2238.58   90.03 2237.18
  102.74 2237.01  108.94 2236.39  112.74 2237.02  121.35 2237.41  126.23 2238.46
  146.29 2242.99  164.51 2243.15  178.41 2244.01   190.2 2245.92  209.88 2247.99
  218.41 2248.63  231.72 2249.19  251.11 2250.72  255.63 2250.78  263.01 2252.11
  277.84 2256.89  281.71 2258.99  293.12 2264.49   297.7 2265.93  302.85 2267.92
#Mann= 3 , 0 , 0
       0    .085       0   85.49     .05       0  126.23    .075       0
#Block Obstruct= 1 ,-1
  198.36  261.272261.796
Bank Sta=85.49,126.23
Exp/Cntr=0.3,0.1

Type RM Length L Ch R = 1 ,101264  ,403.64,343.67,239.21
BEGIN DESCRIPTION:
101186.4
END DESCRIPTION:
XS GIS Cut Line= 3
  925656.2858787   809147.931994  925503.1613831  809108.8699362
  925359.4111668  809071.3697461
#Sta/Elev= 30
       0 2261.06   27.94 2243.52   40.03 2238.23   45.97 2235.89   52.75 2236.18
   88.18 2234.84  105.22    2235   122.4  2235.6  131.88 2235.63  133.87 2235.55
  137.962234.899  154.08 2232.53  162.73 2231.99  172.74 2232.78   183.2 2235.03
  191.39 2237.52   205.1 2237.16  211.49 2237.44  216.64 2238.36  225.74 2239.48
  235.79 2241.13  241.49 2241.69  253.86 2244.52  257.79 2247.08  266.47  2251.5
  283.42 2261.56  286.78 2263.24  291.47 2266.21  295.72 2268.52  306.59 2276.06
#Mann= 3 , 0 , 0
       0     .07       0  137.96     .05       0   183.2     .07       0
#Block Obstruct= 1 ,-1
  231.05  244.172252.405
Bank Sta=137.96,183.2
Exp/Cntr=0.3,0.1

Type RM Length L Ch R = 1 ,100921  ,201.39,180.38,58.98
BEGIN DESCRIPTION:
100842.7
END DESCRIPTION:
XS GIS Cut Line= 6
  925642.2239476  808729.1824326  925581.2865229  808761.9949708
  925512.5356624  808785.4322055  925475.0364966  808804.1817885
  925417.2238317  808843.2448704  925370.3483381  808861.9944534
#Sta/Elev= 30
       0 2268.47      14 2261.88   21.14 2259.68   31.75  2255.5   72.24 2230.89
   77.47 2230.95   85.65 2230.48  101.66 2228.79  110.59 2228.64  112.15 2228.21
  125.72  2230.8  133.11  2232.6  136.43 2232.71  140.05 2233.35  149.56 2233.44
   171.7 2234.36  175.95 2235.65  184.35 2236.98  192.85 2237.75  197.39 2239.33
  204.17 2240.57  229.55 2246.81  230.96 2247.71  242.94 2251.83  253.63 2260.12
  263.87  2267.1  272.45 2271.79  285.29 2277.43  292.45 2281.44  304.11 2286.77
#Mann= 3 , 0 , 0
       0     .09       0   85.65     .05       0  125.72    .075       0
#Block Obstruct= 1 ,-1
  190.26  236.172259.503
Bank Sta=85.65,125.72
Exp/Cntr=0.3,0.1

Type RM Length L Ch R = 1 ,100740  ,155.19,161.41,167.74
BEGIN DESCRIPTION:
100662.4
END DESCRIPTION:
XS GIS Cut Line= 6
  925525.0357258  808551.0567861  925462.5364333   808611.995235
  925431.2857628  808655.7449446  925412.5361799  808705.7451979
  925371.9112301  808804.1817885  925348.4739954  808841.6819785
#Sta/Elev= 30
       0 2264.54   20.01 2257.47   24.47  2256.2   26.94 2255.52   44.06 2252.06
   47.04 2249.99    63.2 2236.14    85.9 2228.22   90.04 2226.68   93.42 2225.72
  113.52  2225.9  115.59 2225.67  118.87  2226.4  128.38 2227.15  136.73 2228.24
  141.06 2229.07   151.2 2231.57  165.52 2232.23  178.73 2231.56  192.97 2232.82
  221.39 2234.05  235.73 2235.11  250.13  2236.9  267.37 2240.07  278.09 2242.24
  282.26 2244.63  313.52 2266.54  327.52 2275.62  343.77 2286.74  345.17 2287.45
#Mann= 3 , 0 , 0
       0     .09       0    85.9     .05       0  136.73    .075       0
#Block Obstruct= 1 ,-1
  246.38  276.662251.954
Bank Sta=85.9,136.73
Exp/Cntr=0.3,0.1

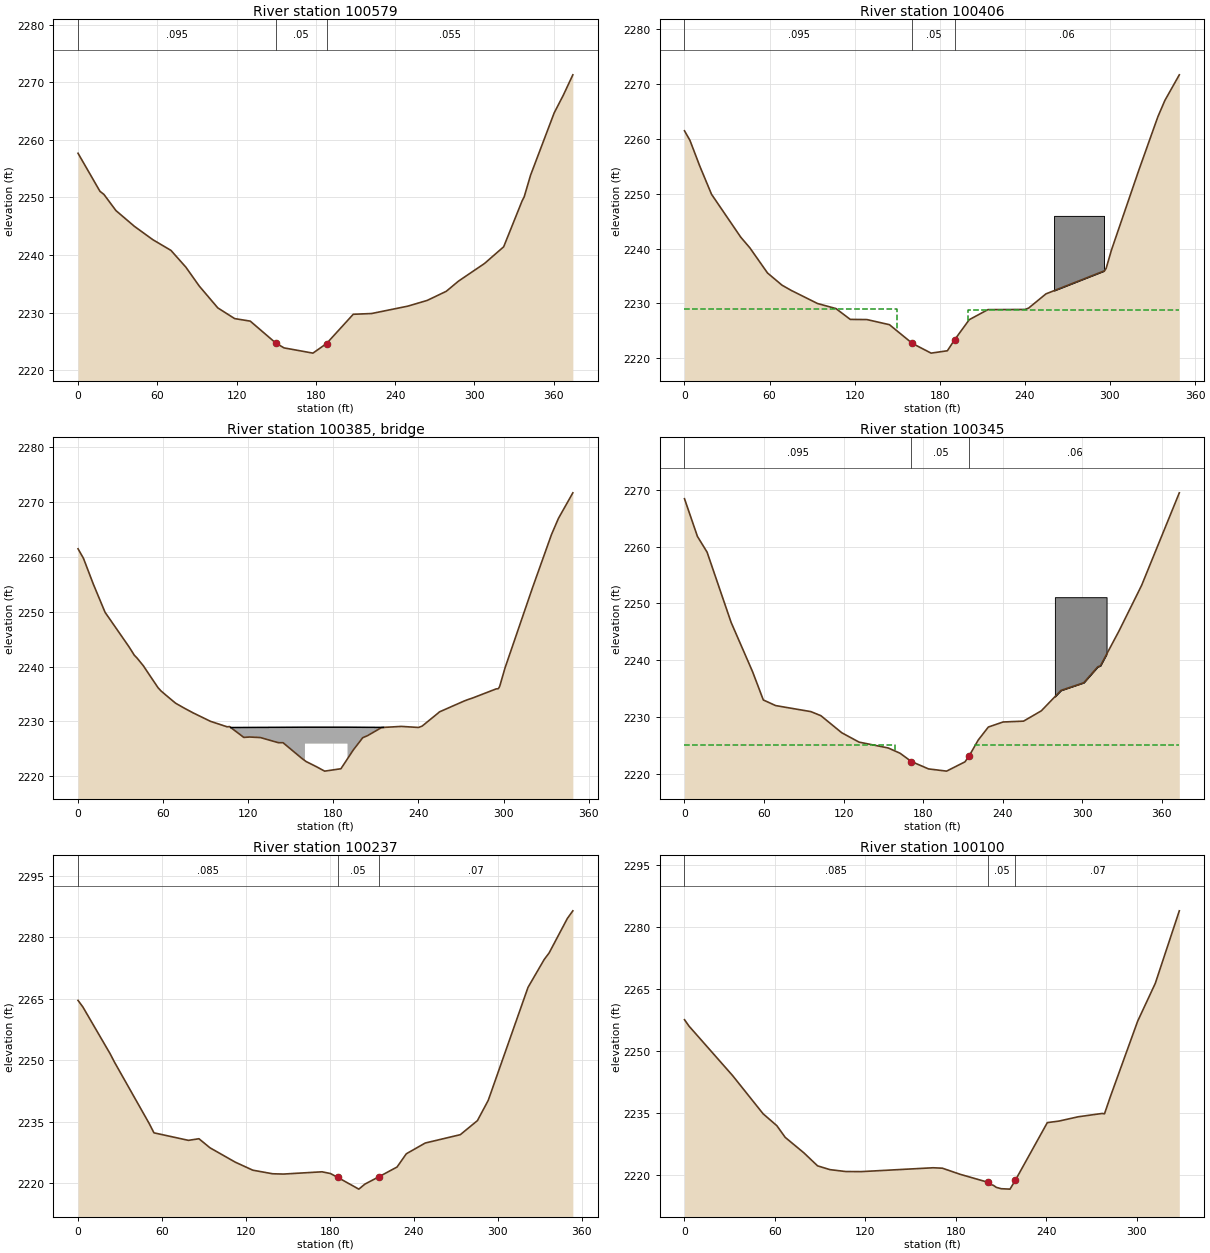
Type RM Length L Ch R = 1 ,100579  ,185.2,172.74,165.79
BEGIN DESCRIPTION:
100501.0
END DESCRIPTION:
XS GIS Cut Line= 6
  925412.5361799  808449.4944116  925350.0358632  808507.3070765
  925310.9738054  808547.9320263  925281.2860269  808601.0570394
  925228.1610138  808718.2442371  925206.2856469  808755.7444271
#Sta/Elev= 30
       0 2257.68   16.59 2251.07    19.6 2250.53   28.69 2247.72   42.67 2244.98
   56.56 2242.67   70.33  2240.8    81.6 2237.89   91.75  2234.6  105.77 2230.81
  118.53 2228.95  130.34 2228.51  149.66  2224.7  155.88 2223.86  177.76 2222.95
  188.04 2224.61  208.26  2229.7  222.11 2229.83  249.49 2231.11  264.24 2232.11
  278.64 2233.69  287.89 2235.46  307.62 2238.53   322.1 2241.43  336.04  2249.4
  337.61  2250.1  342.43 2253.86  360.31 2264.69  367.27 2267.79  374.44 2271.31
#Mann= 3 , 0 , 0
       0    .095       0  149.66     .05       0  188.04    .055       0
Bank Sta=149.66,188.04
Exp/Cntr=0.5,0.3

Type RM Length L Ch R = 1 ,100406  ,57.85,61.12,38.97
BEGIN DESCRIPTION:
100328.2
END DESCRIPTION:
XS GIS Cut Line= 6
  925228.1610138  808361.9949924  925196.9113675   808405.744702
  925157.8482856  808460.4326071  925123.4738795  808540.1196147
  925092.2232091  808599.4951716  925082.8489297  808672.9326597
#Sta/Elev= 30
       0 2261.44    3.82 2259.71   10.75 2255.03   19.06 2249.88    39.7 2242.06
   46.06 2240.14   58.54 2235.55   68.82 2233.32   75.25 2232.38   93.72    2230
  106.81 2229.07  116.88  2227.1  128.61 2227.07   144.5 2226.14   160.7 2222.72
  173.87 2220.96  185.35 2221.39  190.552223.425  200.78 2227.05  213.95 2228.88
  240.09 2228.91  242.64 2229.16  254.88 2231.75  296.26 2235.96  297.36 2236.44
  301.03 2239.72  320.49 2254.38  333.81 2264.02  338.72 2266.97  348.89 2271.63
#Mann= 3 , 0 , 0
       0    .095       0   160.7     .05       0  190.55     .06       0
#XS Ineff= 2 , 0
       0     150 2228.96     200       0 2228.86
Permanent Ineff=
       F       F
#Block Obstruct= 1 ,-1
  260.57  295.812245.947
Bank Sta=160.7,190.55
Exp/Cntr=0.5,0.3

Type RM Length L Ch R = 3 ,100385  ,,,
Node Photo=H:\PROJ\06-0741\CE\GIS\DATA\FRENCH_BROAD_RIVER\SHAPEFILES\survey_data\photos\FBSTR_1772.JPG
BEGIN DESCRIPTION:
100306.3  FBSTR_1772
END DESCRIPTION:
Bridge Culvert--1,0,-1,-1, 0
Deck Dist Width WeirC Skew NumUp NumDn MinLoCord MaxHiCord MaxSubmerge Is_Ogee
12,10,2.6,0, 7, 7, , , 0.95, 0, 1,1,,
  107.67     160     160  178.87     190     190  215.34
  2228.9 2228.96 2228.96 2228.96 2228.96 2228.96 2228.92
                 2225.96 2225.96 2225.96
  108.76  174.17  174.17  189.17  204.17  204.17  239.07
  2228.9 2228.96 2228.96 2228.96 2228.96 2228.96 2228.96
                 2225.96 2225.96 2225.96
BR Coef=-1 , 0 , 0 ,, 0 ,,,0.8,0,,0,
WSPro=,,,, 1 ,,,, 0 ,,,, 0 ,,,,-1 ,-1 ,-1 , 0 , 0 , 0 , 0 , 0
BR U #Sta/Elev= 61
       0 2261.44    3.82 2259.71   10.75 2255.03   19.06 2249.88   35.93  2243.6
    39.7 2242.06   41.55 2241.57   46.06 2240.14   51.02 2238.22   56.42 2236.15
   58.54 2235.55   61.95  2234.8   68.82 2233.32   75.25 2232.38   81.21 2231.56
   93.15 2230.06   93.44 2230.03   93.72    2230  105.12 2229.03  106.81 2229.07
  116.82 2227.11  116.88  2227.1  116.95  2227.1  120.97 2227.17  128.61 2227.07
  141.19 2226.14   144.5 2226.14  158.09 2223.22  159.97 2222.87  160.67 2222.73
   160.7 2222.72  161.65  2222.6  168.43 2221.72  173.87 2220.96  174.76 2220.99
   184.7 2221.37  185.35 2221.39  190.552223.425  194.09 2224.81  200.78 2227.05
  204.02  2227.4  213.95 2228.88  214.75 2228.91   227.9  2229.1  228.07  2229.1
  240.09 2228.91  242.64 2229.16  253.52 2231.45  254.88 2231.75  272.21 2233.72
  274.85 2233.98  278.49  2234.3  294.81 2235.93  296.26 2235.96  296.86 2236.17
  297.36 2236.44  301.03 2239.72  320.49 2254.38  333.81 2264.02  338.72 2266.97
  348.89 2271.63
BR U #Mann= 3
       0    .065   160.7     .04  190.55     .06
BR D #Sta/Elev= 73
       0 2268.43    1.21 2267.78    9.76 2261.79   15.24 2259.65   17.05 2259.01
   19.48  2257.3   32.97 2248.05   35.16 2246.64   46.55 2240.49   51.39 2237.93
   59.47 2232.96   68.79 2231.97   70.65 2231.93   71.26  2231.9   77.72 2231.55
   86.07 2231.16   86.89 2231.12   93.89 2230.86   95.33 2230.91  102.92 2230.19
  106.22 2229.34  118.48 2227.22  118.66 2227.18  120.93 2226.87  122.28 2226.68
  131.74 2225.53  142.38 2225.13   146.8 2224.91  153.72  2224.5  162.65 2223.57
   170.1 2222.28  171.19 2222.11  172.45 2221.92  174.19 2221.68  180.02 2221.11
  180.63 2221.05  184.13 2220.81  186.89 2220.66  194.17 2220.45  197.74 2220.42
  200.62 2220.63  204.25 2221.11  207.83 2221.59  211.64 2222.06  214.88 2223.15
  221.58 2225.89  224.06 2226.62  229.24 2228.19  237.21 2228.79  240.34 2229.08
  242.55 2229.14  253.13 2229.29  254.71 2229.32  255.81 2229.23  269.22 2231.05
  269.35 2231.08  270.16 2231.28  281.81 2234.19  282.04 2234.24  284.03 2234.64
  291.58 2235.45  299.53 2235.75  301.25    2236  304.31 2236.82  311.75 2238.79
  313.82 2238.99   323.7 2243.46  327.77  2245.1  344.86 2253.15  370.93 2267.91
  370.99 2267.95  371.07    2268  373.32 2269.47
BR D #Mann= 3
       0    .065  180.02     .04  204.25     .06
BR D Banks=174.19,
BC Design=,, 0 ,, 0 ,,,,,,

Type RM Length L Ch R = 1 ,100345  ,58.74,107.72,175.54
BEGIN DESCRIPTION:
100267.1
END DESCRIPTION:
XS GIS Cut Line= 6
   925185.973172  808326.0576943  925109.4109242  808421.3695251
  925087.5365815  808465.1192347  925070.3488664   808515.119488
   925056.285911   808571.369261  925045.3487397  808661.9944641
#Sta/Elev= 30
       0 2268.43    9.76 2261.79   17.05 2259.01   35.16 2246.64   51.39 2237.93
   59.47 2232.96   68.79 2231.97   95.33 2230.91  102.92 2230.19  118.66 2227.18
  131.74 2225.53  153.72  2224.5  162.65 2223.57  171.19 2222.11  184.13 2220.81
  197.74 2220.42  211.64 2222.06  214.88 2223.15  221.58 2225.89  229.24 2228.19
  240.34 2229.08  255.81 2229.23  269.22 2231.05  284.03 2234.64  301.25    2236
  311.75 2238.79  313.82 2238.99  327.77  2245.1  344.86 2253.15  373.32 2269.47
#Mann= 3 , 0 , 0
       0    .095       0  171.19     .05       0  214.88     .06       0
#XS Ineff= 2 , 0
       0  159.17    2225  219.17       0    2225
Permanent Ineff=
       F       F
#Block Obstruct= 1 ,-1
  279.46  318.432251.075
Bank Sta=171.19,214.88
Exp/Cntr=0.5,0.3

Type RM Length L Ch R = 1 ,100237  ,52.83,137.07,221.04
BEGIN DESCRIPTION:
100159.4
END DESCRIPTION:
XS GIS Cut Line= 6
  925146.9111142  808297.9317837  925098.4737528  808341.6825175
  925046.9106075  808374.4950557  925004.7237899  808408.8694618
  924978.1607712      808441.682  924892.2232198  808540.1196147
#Sta/Elev= 30
       0 2264.58    3.48 2262.97   23.05 2251.49   25.95 2249.57   50.99 2234.44
   54.27 2232.24   78.93  2230.4   86.43  2230.8    94.3 2228.59  112.38 2225.08
  124.89 2223.12  139.11 2222.24  146.85 2222.17  174.44 2222.72  180.44  2222.3
  185.54 2221.37  200.71 2218.49  205.09 2219.72  214.87 2221.47  228.04 2223.89
  234.66 2227.12  248.18 2229.75  273.26 2231.79  285.49 2235.22  293.22 2240.17
  321.66 2267.77  333.18 2274.55  336.73 2276.17   349.8 2284.61   353.7 2286.46
#Mann= 3 , 0 , 0
       0    .085       0  185.54     .05       0  214.87     .07       0
Bank Sta=185.54,214.87
Exp/Cntr=0.3,0.1

Type RM Length L Ch R = 1 ,100100  ,40.31,128.38,190.24
XS GIS Cut Line= 6
  925125.0357473  808282.3069606  925081.2860377  808294.8070239
  925050.0363915  808307.3070872   925021.911505  808307.3070872
  924959.4111883  808316.6823908  924801.5990409  808316.6823908
#Sta/Elev= 30
       0 2257.56    3.03    2256   31.91 2244.04    52.2 2234.77   61.29  2231.9
   66.84 2229.07   79.16 2225.35   88.28 2222.19   96.46 2221.27  106.99 2220.81
  117.32 2220.79  164.87 2221.72  171.08 2221.62  182.88 2220.14   201.1 2218.23
  202.58 2217.74  204.98 2217.46  206.87 2216.98  210.13 2216.65  215.97 2216.55
  219.57 2218.74  240.72 2232.65  248.55 2233.03  261.15 2234.06  277.15 2234.87
  278.65 2234.78  282.52 2238.91  300.64 2257.19  312.37 2266.38  328.29 2283.92
#Mann= 3 , 0 , 0
       0    .085       0   201.1     .05       0  219.57     .07       0
Bank Sta=201.1,219.57
Exp/Cntr=0.3,0.1

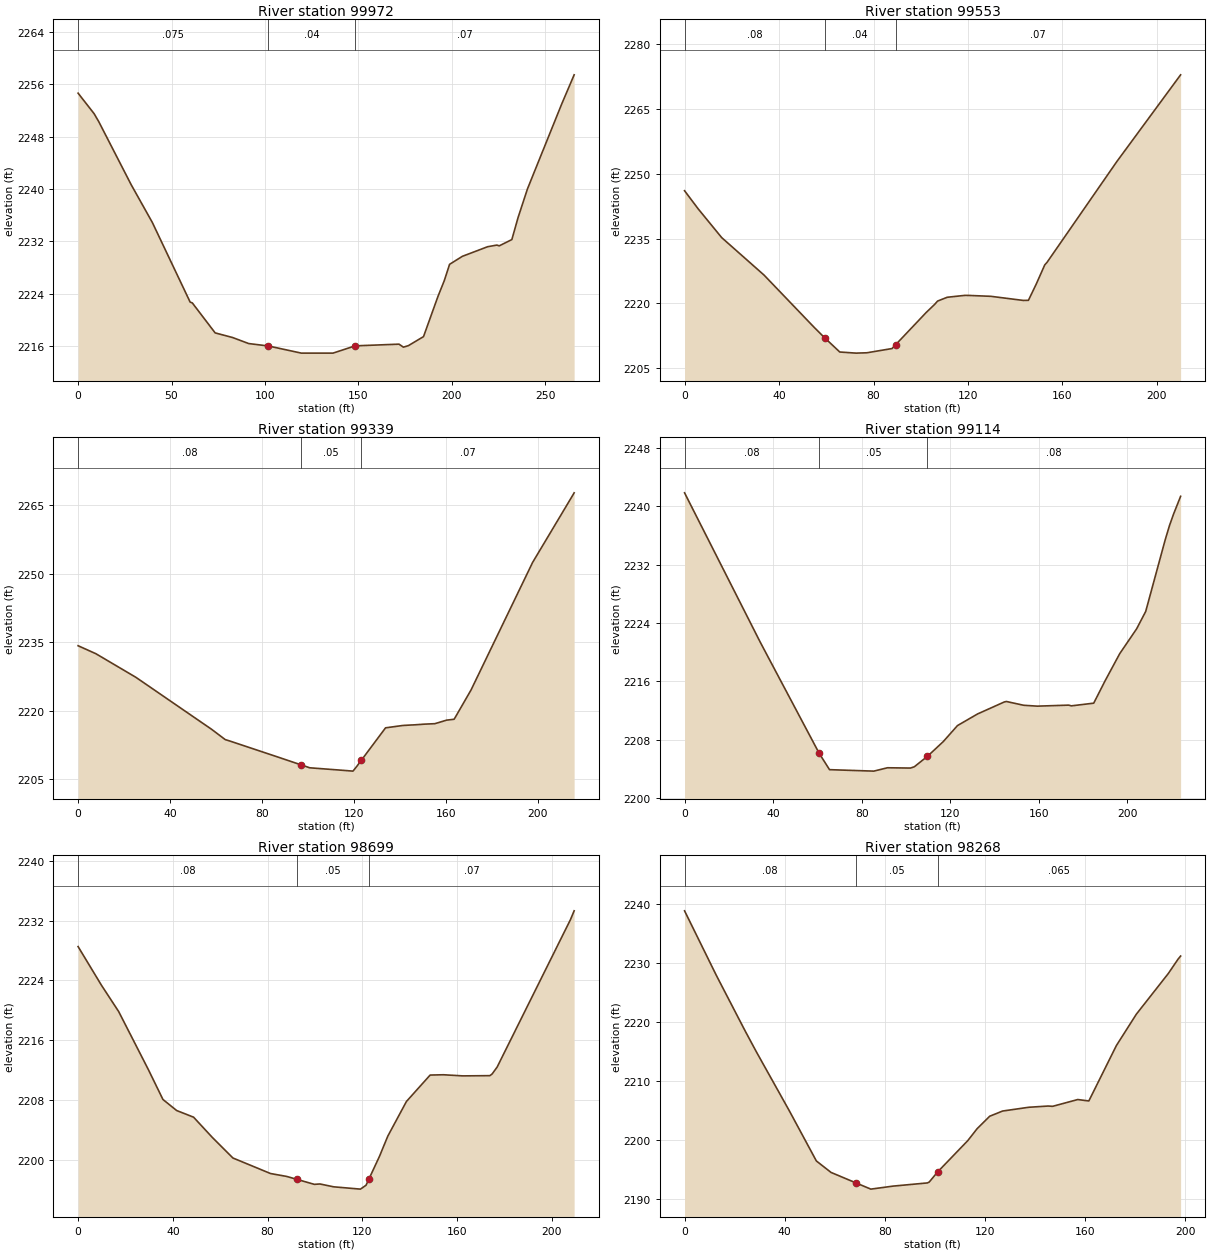
Type RM Length L Ch R = 1 ,99972   ,403.25,418.5,406.3
BEGIN DESCRIPTION:
99893.99
END DESCRIPTION:
XS GIS Cut Line= 6
  925115.6614679  808265.1192455  925067.2230824  808257.3068339
  925035.9734361  808244.8067706  925007.8485497  808215.1200163
  924940.6605812  808160.4321112   924890.661352  808136.9948765
#Sta/Elev= 30
       0 2254.65    8.59 2251.51   11.08 2250.29   28.41 2240.67   39.74  2234.9
   59.97 2222.74   61.12 2222.62   73.35 2218.04   82.72 2217.33   91.32 2216.41
  101.86 2216.04  119.48 2214.95  136.41 2214.95  148.27 2216.06  171.73 2216.32
  174.13 2215.86   176.8  2216.1  184.86 2217.47  192.54 2223.57  195.94 2225.99
  198.81 2228.51  205.63 2229.73  219.18  2231.2  224.16 2231.45  225.36 2231.33
  232.13 2232.29  235.48 2235.67  240.49 2240.03  258.78 2252.97  265.47 2257.45
#Mann= 3 , 0 , 0
       0    .075       0  101.86     .04       0  148.27     .07       0
Bank Sta=101.86,148.27
Exp/Cntr=0.3,0.1

Type RM Length L Ch R = 1 ,99553   ,264.5,214.36,178.67
BEGIN DESCRIPTION:
99475.48
END DESCRIPTION:
XS GIS Cut Line= 5
  925292.2231983  807946.3701908   925262.536444  807894.8070454
  925242.2239691  807876.0574625   925189.098956  807846.3696841
  925148.4740062  807799.4952147
#Sta/Elev= 25
       0 2246.08    5.81 2241.86   15.72 2235.24   33.64 2226.58   54.95 2214.44
    59.5 2211.97   65.72 2208.78   72.61 2208.52   77.21  2208.6   87.86 2209.58
   89.32 2210.43  102.33 2217.93  105.89 2219.79  107.14 2220.56  111.22 2221.44
   118.7 2221.88  120.61 2221.86  129.68 2221.66  143.41 2220.71  145.59 2220.73
  148.86 2224.44  152.49 2228.91   153.5 2229.54     183 2252.81  210.03 2272.89
#Mann= 3 , 0 , 0
       0     .08       0    59.5     .04       0   89.32     .07       0
Bank Sta=59.5,89.32
Exp/Cntr=0.3,0.1

Type RM Length L Ch R = 1 ,99339   ,254.7,225.28,147.27
BEGIN DESCRIPTION:
99261.12
END DESCRIPTION:
XS GIS Cut Line= 4
  925423.4733513  807683.8698849  925337.5357999  807682.3069929
  925306.2861536  807682.3069929  925207.8485389  807676.0574733
#Sta/Elev= 28
       0  2234.2    7.78 2232.44   25.19 2227.27   58.06 2215.91   64.03 2213.64
   65.85 2213.36   85.95 2209.99    93.5 2208.71   96.962208.122   100.8 2207.47
   117.2 2206.84  117.59 2206.82   119.6 2206.74  121.17 2207.72  121.932208.232
  123.182209.075  133.78 2216.22  141.35 2216.74  144.93 2216.84  146.27 2216.87
  150.81 2217.03  155.25 2217.13  160.32  2217.9  163.63  2218.1  170.99 2224.52
  197.78 2252.45   215.4 2267.29  215.84 2267.68
#Mann= 3 , 0 , 0
       0     .08       0   96.96     .05       0  123.18     .07       0
Bank Sta=96.96,123.18
Exp/Cntr=0.3,0.1

Type RM Length L Ch R = 1 ,99114   ,449.9,415.13,344.64
BEGIN DESCRIPTION:
99035.85
END DESCRIPTION:
XS GIS Cut Line= 5
  925364.0988185  807419.8077111  925289.0984385  807463.5574207
  925253.1611405   807496.369959  925228.1610138  807521.3700856
  925193.7855836  807561.9950354
#Sta/Elev= 27
       0 2241.84   34.24 2221.35   60.81 2206.16   65.48 2203.92   85.48 2203.72
   91.65 2204.18  102.05 2204.14   103.8 2204.32  109.71 2205.75  116.84 2207.76
  123.28 2209.96  132.34 2211.55   144.4 2213.19  145.34 2213.26  153.19 2212.74
  159.36 2212.62  173.52 2212.76  174.68 2212.66  184.82 2213.03  189.88 2216.05
  196.56 2219.81  204.19 2223.21  208.29 2225.59  217.16 2235.47  219.06 2237.38
  220.89 2238.94  224.06 2241.36
#Mann= 3 , 0 , 0
       0     .08       0   60.81     .05       0  109.71     .08       0
Bank Sta=60.81,109.71
Exp/Cntr=0.3,0.1

Type RM Length L Ch R = 1 ,98699   ,465.57,430.86,382.84
BEGIN DESCRIPTION:
98620.71
END DESCRIPTION:
XS GIS Cut Line= 5
  924964.0988401  807201.0571148  924939.0987134  807269.8069511
   924928.161542  807307.3071411  924926.5986501  807343.2444391
  924906.2861752   807401.057104
#Sta/Elev= 29
       0 2228.53    9.79 2223.39   17.13 2219.83   29.69 2212.04   35.83 2208.05
   41.62 2206.57   48.76 2205.68    56.7 2202.96   65.38 2200.21   81.25 2198.13
    88.1 2197.74    92.5 2197.34   99.75 2196.68  102.12 2196.73   107.9 2196.35
  119.22 2196.04  121.59 2196.56  122.782197.373  127.29 2200.45  130.77 2203.13
  138.65 2207.78  148.66 2211.32  154.29 2211.36  162.42 2211.21   173.9 2211.24
  174.85 2211.47  176.95 2212.39   207.9 2232.13  209.47 2233.32
#Mann= 3 , 0 , 0
       0     .08       0    92.5     .05       0  122.78     .07       0
Bank Sta=92.5,122.78
Exp/Cntr=0.3,0.1

Type RM Length L Ch R = 1 ,98268   ,155.6,209.42,289.06
BEGIN DESCRIPTION:
98189.86
END DESCRIPTION:
XS GIS Cut Line= 4
  924500.0356529  807240.1201968  924496.9108931  807276.0574948
  924525.0357796  807358.8692623  924550.0359063  807429.1819905
#Sta/Elev= 27
       0 2238.78   12.63 2227.89   24.07 2218.52    28.7 2214.86   41.92 2204.82
   52.65 2196.37   58.52 2194.42    68.52192.641   74.41 2191.59   83.27  2192.1
   96.98 2192.64   97.72 2192.78  101.08  2194.5  113.13 2199.81  116.88 2201.84
   121.9 2203.95  127.04 2204.83  137.49 2205.47  145.27 2205.68  147.04 2205.63
  157.07 2206.78   161.5 2206.54  172.51 2215.94  180.49 2221.26  193.26 2228.16
   197.1 2230.56  198.16 2231.11
#Mann= 3 , 0 , 0
       0     .08       0    68.5     .05       0  101.08    .065       0
Bank Sta=68.5,101.08
Exp/Cntr=0.3,0.1

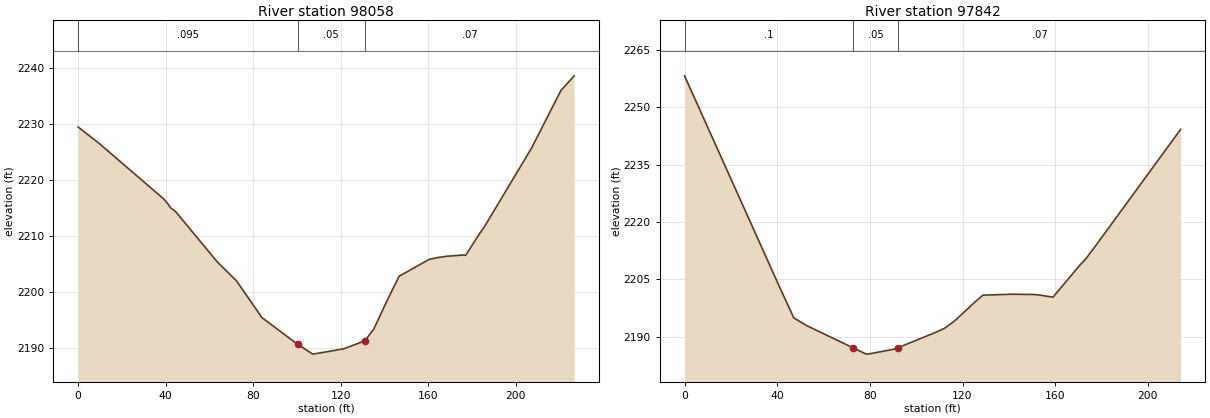
Type RM Length L Ch R = 1 ,98058   ,178.12,215.92,264.72
BEGIN DESCRIPTION:
97980.43
END DESCRIPTION:
XS GIS Cut Line= 6
  924379.7236955  807244.8068244  924343.7863975  807293.2452099
   924315.661511   807329.182508  924284.4108406   807365.119806
  924268.7860175  807393.2446925  924237.5363712  807419.8077111
#Sta/Elev= 26
       0 2229.48    9.53 2226.58   39.25 2216.61   41.19 2215.69   42.21 2215.09
   44.65 2214.36   63.66  2205.4    72.4 2202.05   84.05 2195.49  100.32 2190.73
   107.3 2188.97  121.27  2189.9  131.09 2191.34  135.17 2193.45  141.49 2198.71
  146.77 2202.87  160.47 2205.86  164.62 2206.21  168.69 2206.43  175.87 2206.64
  177.18  2206.6  183.77 2210.61  185.75 2211.69  207.24 2225.68  220.76 2236.01
  226.76  2238.6
#Mann= 3 , 0 , 0
       0    .095       0  100.32     .05       0  131.09     .07       0
Bank Sta=100.32,131.09
Exp/Cntr=0.3,0.1

Type RM Length L Ch R = 1 ,97842   ,224.73,205.79,141.24
BEGIN DESCRIPTION:
97764.51
END DESCRIPTION:
XS GIS Cut Line= 6
  924329.7234422  807102.6195001  924293.7861441   807122.931975
  924246.9106506  807133.8701705  924220.3486561  807143.2444499
  924164.0988831   807160.432165  924129.7234529  807176.0569881
#Sta/Elev= 24
       0 2258.28   41.28 2202.64   47.16 2194.91   52.73 2192.89   72.882187.035
   78.45 2185.42   80.45 2185.57   90.72 2186.75    92.3 2187.14  107.85 2190.98
  112.02 2192.11  116.39 2194.01   125.6 2199.19  128.84 2200.86   141.2  2201.1
  150.96 2201.03  153.19 2200.89  159.06 2200.33  170.54 2208.64  172.06 2209.61
  172.38 2209.75  173.26 2210.39   176.4  2212.9  214.16 2244.25
#Mann= 3 , 0 , 0
       0      .1       0   72.88     .05       0    92.3     .07       0
Bank Sta=72.88,92.3
Exp/Cntr=0.3,0.1