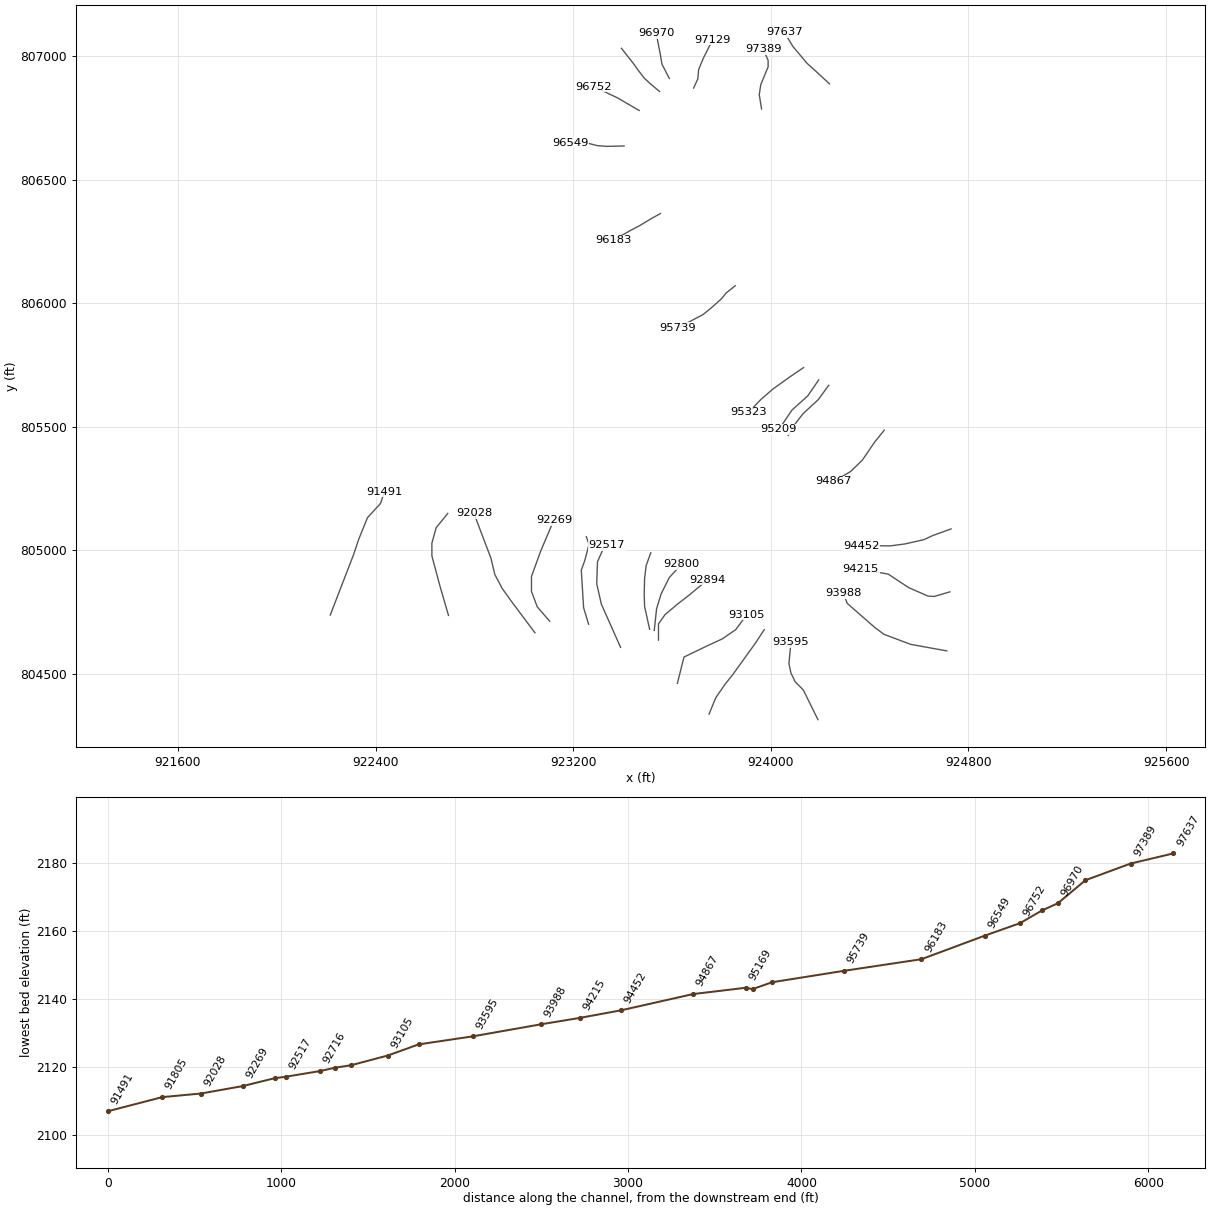
HEC-RAS study lds_big_laurel_crk.prj: lds_big_laurel_crk

--- lds_big_laurel_crk.g20 (geometry) --- (continued)

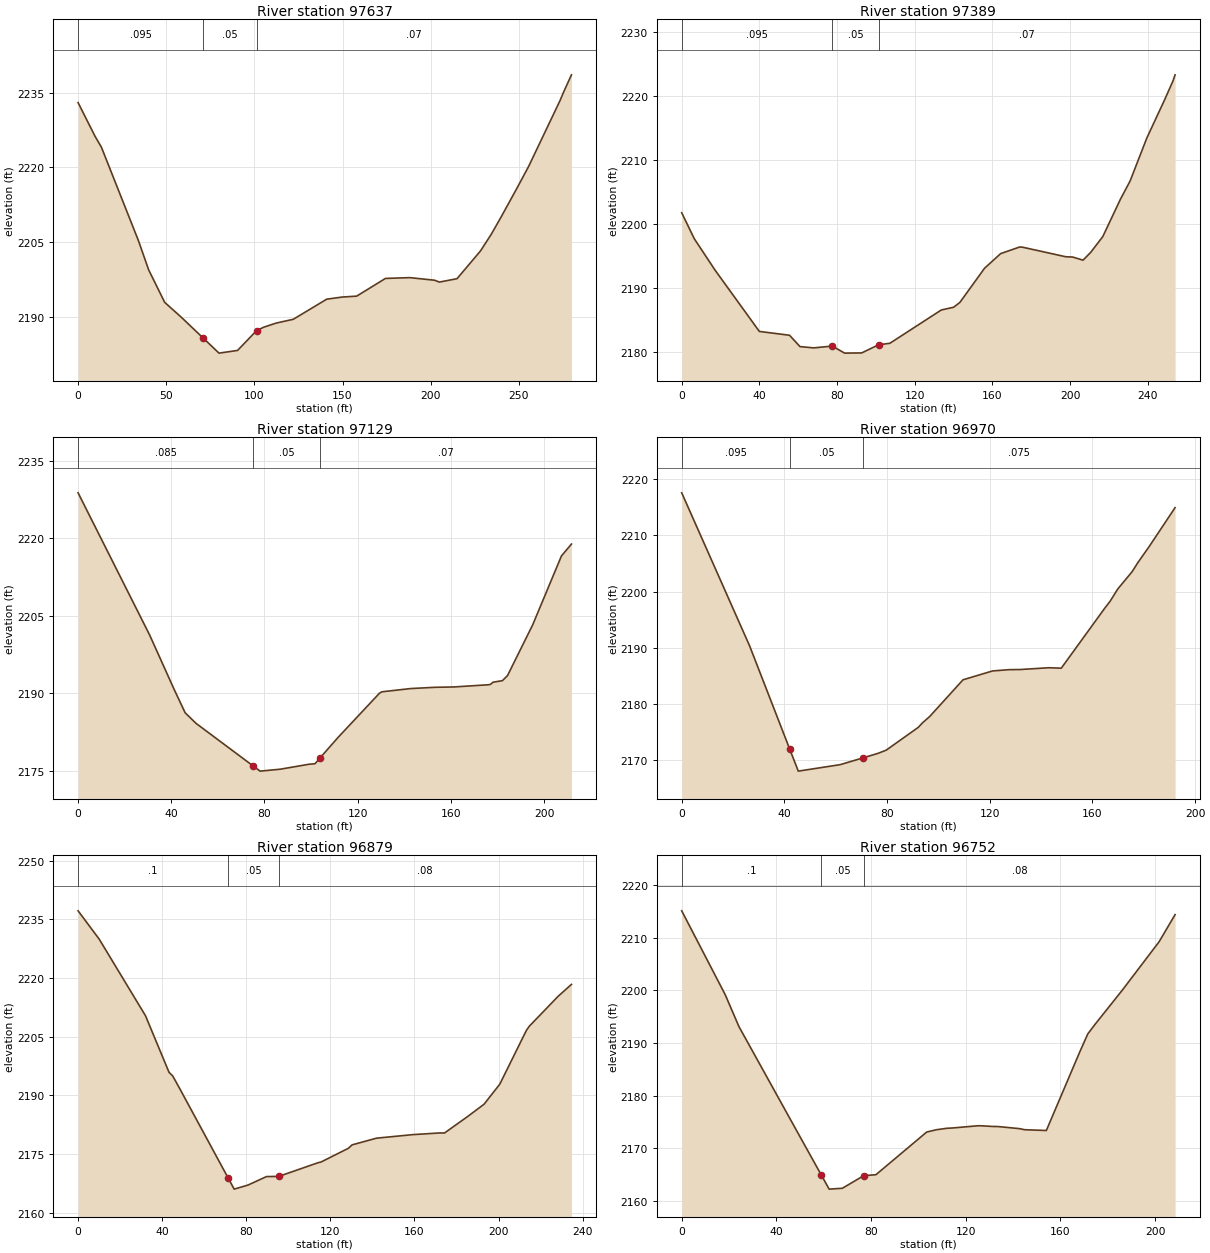
Type RM Length L Ch R = 1 ,97637   ,280.22,247.48,114.22
BEGIN DESCRIPTION:
97558.72
END DESCRIPTION:
XS GIS Cut Line= 5
  924237.5363712  806888.5575797  924178.1608143  806943.2444607
   924146.911168  806971.3693471  924089.0985031  807040.1202076
  924054.7230729  807097.9318483
#Sta/Elev= 30
       0 2232.99    9.61 2226.25   13.24 2224.05   34.23 2205.33   40.04 2199.47
   49.12 2192.96   58.49 2189.99   71.11 2185.75   79.93 2182.78   90.46 2183.32
  101.25 2187.29  105.34 2187.98  112.44 2188.81  122.07 2189.56  141.01 2193.59
  149.77 2194.02  158.01  2194.2  174.35 2197.75  188.23 2197.91  202.23 2197.39
  204.92 2197.02  214.95  2197.7  228.25 2203.26  234.38 2206.61  240.01  2210.1
  249.16 2215.98  255.59 2220.22  273.35 2233.38  275.28    2235  279.85 2238.56
#Mann= 3 , 0 , 0
       0    .095       0   71.11     .05       0  101.25     .07       0
Bank Sta=71.11,101.25
Exp/Cntr=0.3,0.1

Type RM Length L Ch R = 1 ,97389   ,269.18,260.07,249.42
XS GIS Cut Line= 6
  923962.5360019  806786.9952052  923953.1606984  806844.8068459
  923959.4112421  806885.4317957  923989.0990206   806957.307416
  923989.0990206  806983.8694105  923968.7865457   807029.182012
#Sta/Elev= 30
       0 2201.71    6.48 2197.65   17.19 2192.74   39.97 2183.18   55.52 2182.58
    60.9 2180.81   67.96 2180.61   77.54 2180.89   83.88 2179.79   92.66 2179.82
  101.36 2181.09   107.2 2181.33  133.62 2186.52  140.02 2186.96   143.2  2187.7
  155.95 2193.05  164.22 2195.33  173.99 2196.36  175.38 2196.34  197.76 2194.84
  201.24  2194.8  206.65 2194.31  210.61 2195.53  216.84    2198  225.91 2203.83
  230.88 2206.67   239.5 2213.39  248.71 2219.39  253.02 2222.34  254.04 2223.25
#Mann= 3 , 0 , 0
       0    .095       0   77.54     .05       0  101.36     .07       0
Bank Sta=77.54,101.36
Exp/Cntr=0.3,0.1

Type RM Length L Ch R = 1 ,97129   ,131.56,159.12,201.12
BEGIN DESCRIPTION:
97051.18
END DESCRIPTION:
XS GIS Cut Line= 5
  923687.5356327  806871.3698646  923704.7233478  806908.8700546
  923707.8481076  806946.3702446  923726.5987147   806991.681822
  923764.0989047  807066.6822021
#Sta/Elev= 25
       0 2228.85   30.72 2201.28   41.25 2190.72   45.95 2186.21   50.61 2184.16
   75.122175.901   78.12 2174.89   86.72 2175.26   99.08 2176.22  101.68 2176.32
  103.96  2177.5  111.64 2181.45   129.4 2190.01  130.41 2190.27  142.78  2190.9
  153.06 2191.14  161.32 2191.21  175.94 2191.63  176.94 2191.69  178.12 2192.13
  182.13 2192.43  184.32 2193.41  195.12 2203.24  207.48 2216.61  211.77 2218.92
#Mann= 3 , 0 , 0
       0    .085       0   75.12     .05       0  103.96     .07       0
Bank Sta=75.12,103.96
Exp/Cntr=0.3,0.1

Type RM Length L Ch R = 1 ,96970   ,79.64,90.6,133.25
BEGIN DESCRIPTION:
96892.07
END DESCRIPTION:
XS GIS Cut Line= 4
  923589.0990421  806910.4319224  923559.4112637  806968.2445873
  923551.5988521  807013.5571889   923535.974029  807093.2452207
#Sta/Elev= 24
       0 2217.53   26.45 2190.35   41.99 2172.11   45.41 2168.11   61.74 2169.26
   70.68 2170.47   76.49 2171.27   79.64 2171.83    92.2  2175.9   93.71 2176.65
   96.62 2177.82  109.58 2184.33  121.08  2185.9  127.64 2186.13  131.77 2186.15
  142.96 2186.47  147.85 2186.39  164.78 2197.04  166.88 2198.28  169.88 2200.47
  175.45 2203.53  177.66 2205.12  182.16 2208.04  192.18  2214.9
#Mann= 3 , 0 , 0
       0    .095       0   41.99     .05       0   70.68    .075       0
Bank Sta=41.99,70.68
Exp/Cntr=0.3,0.1

Type RM Length L Ch R = 1 ,96879   ,117.43,127.55,169.76
BEGIN DESCRIPTION:
96801.47
END DESCRIPTION:
XS GIS Cut Line= 6
  923550.0359601  806857.3069093  923512.5357701  806888.5575797
  923487.5356434  806911.9948144   923460.973649  806946.3702446
   923442.224066  806972.9322391  923395.3485725  807032.3067718
#Sta/Elev= 26
       0  2237.2   10.01 2229.99   32.08 2210.36   43.26  2195.9   45.04 2194.95
   48.81 2191.28   71.37 2168.88   74.25 2166.02   80.83 2167.06   89.64 2169.23
   95.49 2169.28  114.19 2172.78  115.59 2172.96  128.53 2176.45  130.35 2177.34
  141.94 2179.05  159.04 2179.95  172.09 2180.39  174.28 2180.37   185.1 2184.51
  193.11 2187.73  200.61 2192.87  213.28 2206.65   214.7 2207.72  228.39 2215.36
  234.69 2218.38
#Mann= 3 , 0 , 0
       0      .1       0   71.37     .05       0   95.49     .08       0
Bank Sta=71.37,95.49
Exp/Cntr=0.3,0.1

Type RM Length L Ch R = 1 ,96752   ,176.05,202.45,224.34
BEGIN DESCRIPTION:
96673.92
END DESCRIPTION:
XS GIS Cut Line= 3
  923467.2231685  806780.7446614  923378.1608574  806832.3067826
  923282.8490266  806877.6193842
#Sta/Elev= 29
       0 2215.09    18.4 2199.15   24.16 2193.13   44.97 2176.26   58.162165.596
   58.372165.426   58.992164.925   62.29 2162.26   67.87 2162.42   76.84  2164.8
   82.06    2165   84.02 2165.74  103.52  2173.1  107.69 2173.54   112.1 2173.81
   114.5 2173.87  125.17 2174.29   126.2 2174.29  131.29 2174.16  133.68 2174.14
  142.74 2173.74  144.83 2173.54  154.06 2173.39  168.04 2188.16  171.56 2191.72
  174.46 2193.44  186.24 2200.08  201.71 2209.23  208.45 2214.37
#Mann= 3 , 0 , 0
       0      .1       0   58.99     .05       0   76.84     .08       0
Bank Sta=58.99,76.84
Exp/Cntr=0.3,0.1

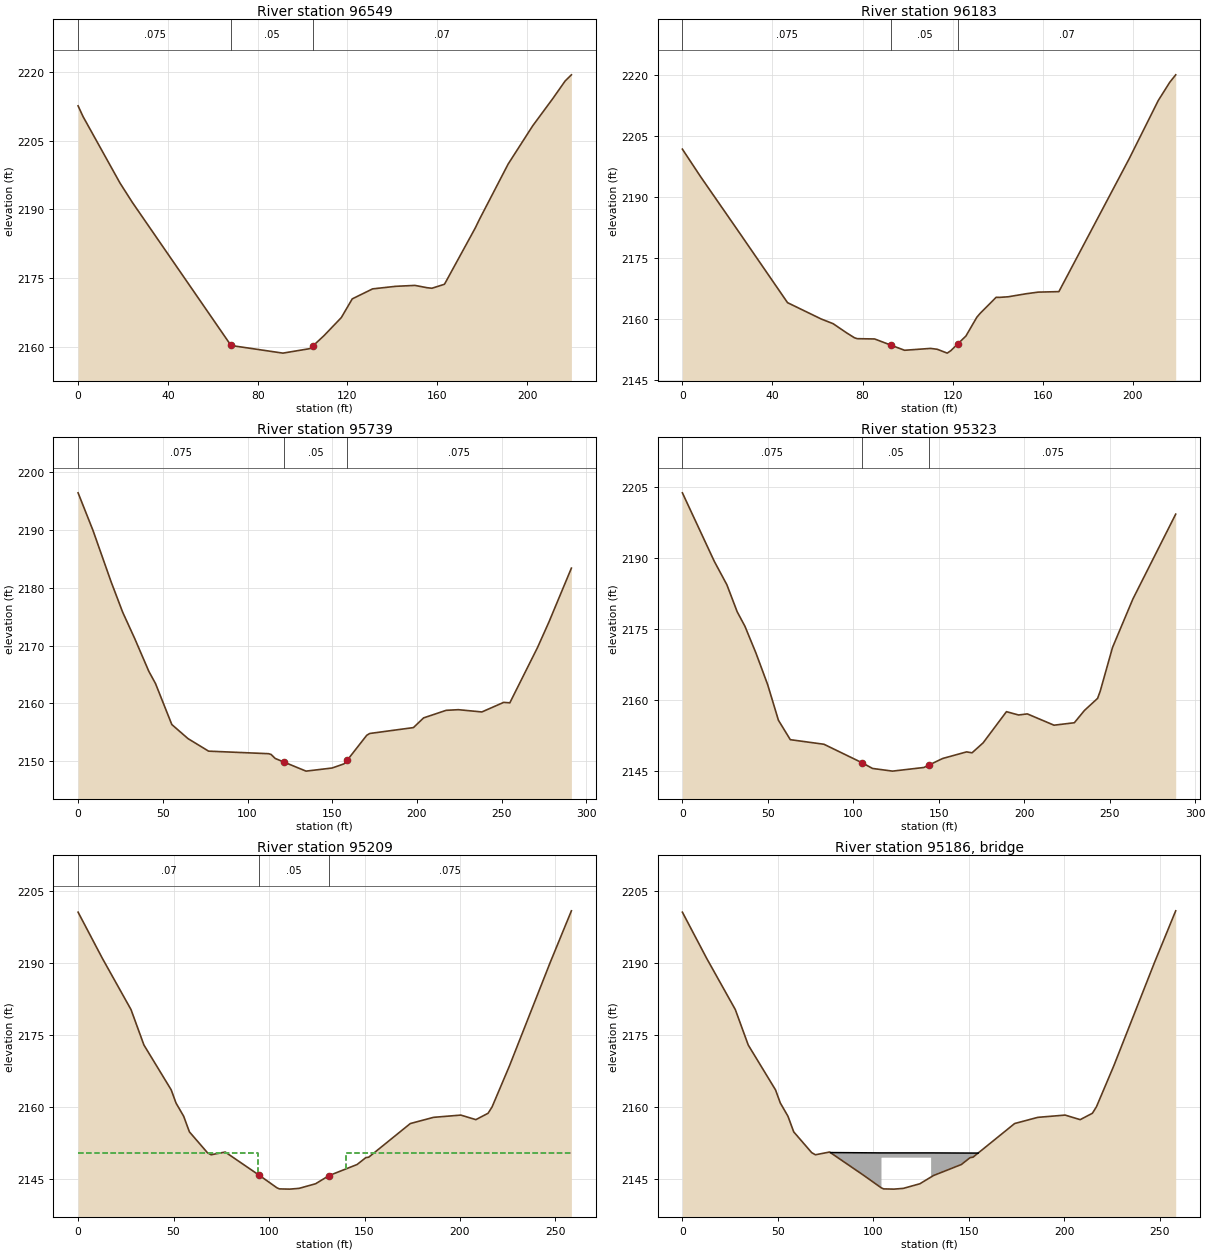
Type RM Length L Ch R = 1 ,96549   ,344.08,366.14,439.17
BEGIN DESCRIPTION:
96471.46
END DESCRIPTION:
XS GIS Cut Line= 5
  923406.2857438  806636.9944451  923335.9740398  806635.4325773
  923296.9109578  806638.5573371  923229.7240135  806655.7450522
  923189.0990637  806651.0574005
#Sta/Elev= 25
       0  2212.6    2.24 2210.24   18.68 2195.74   24.15 2191.54   68.13 2160.27
   91.24  2158.6  103.34 2159.59   104.62160.163  109.52  2162.4  117.26 2166.36
  122.14 2170.45   131.2 2172.63  141.49 2173.19  150.06 2173.39  155.42 2172.89
  157.62 2172.77  163.04 2173.61   163.3 2173.71  176.91 2185.91  178.87 2187.88
  191.59  2199.9  202.57 2208.28  211.35 2214.11  216.98 2218.04  219.76 2219.38
#Mann= 3 , 0 , 0
       0    .075       0   68.13     .05       0   104.6     .07       0
Bank Sta=68.13,104.6
Exp/Cntr=0.3,0.1

Type RM Length L Ch R = 1 ,96183   ,428.98,444.47,443.81
BEGIN DESCRIPTION:
96105.32
END DESCRIPTION:
XS GIS Cut Line= 5
  923553.1607199  806363.5569679  923514.0986621  806341.6826252
  923467.2231685  806313.5577387  923434.4106303  806296.3700236
  923362.5360342  806255.7450738
#Sta/Elev= 30
       0 2201.77    8.03 2195.05   25.69 2180.94   46.69 2164.05   61.66 2160.03
   66.91 2158.89   73.01  2156.6   76.38 2155.43   77.62  2155.2   85.36 2155.13
   92.492153.632   98.66 2152.35  110.17 2152.81  113.14  2152.6   117.6 2151.65
  119.22 2152.27  122.372153.966  125.89 2155.85  130.74 2160.47  132.19 2161.41
  139.29 2165.36  140.92 2165.35  144.73  2165.5  152.76 2166.25  158.02 2166.64
  167.17 2166.76  198.52 2199.56  211.27 2213.69  216.35 2218.16  219.04 2220.03
#Mann= 3 , 0 , 0
       0    .075       0   92.49     .05       0  122.37     .07       0
Bank Sta=92.49,122.37
Exp/Cntr=0.3,0.1

Type RM Length L Ch R = 1 ,95739   ,430.75,416.09,432.83
BEGIN DESCRIPTION:
95660.85
END DESCRIPTION:
XS GIS Cut Line= 6
  923856.2859756  806071.3699077  923818.7857856  806041.6821292
  923800.0362027  806018.2448945  923757.8483609  805980.7447045
  923725.0358227    805954.18271  923623.4734482  805901.0576969
#Sta/Elev= 30
       0 2196.45    8.76 2189.97   19.49 2181.04   26.31 2175.78   33.41 2171.22
   41.76 2165.53   45.69 2163.42   55.31 2156.32   64.88 2153.88   77.02 2151.71
  112.39 2151.27   113.9 2151.14  116.35 2150.44  121.31 2149.84  134.54 2148.25
   149.9 2148.79  156.93 2149.51  158.92 2150.17  170.35 2154.46  172.12 2154.77
   197.9 2155.79   203.9 2157.47  217.21 2158.78  224.45 2158.89  238.28  2158.5
   251.2 2160.16  254.79 2160.08  271.05 2169.61   277.9  2174.1  291.12 2183.41
#Mann= 3 , 0 , 0
       0    .075       0  121.31     .05       0  158.92    .075       0
Bank Sta=121.31,158.92
Exp/Cntr=0.3,0.1

Type RM Length L Ch R = 1 ,95323   ,99.88,113.59,133.39
BEGIN DESCRIPTION:
95244.75
END DESCRIPTION:
XS GIS Cut Line= 5
  924132.8482127  805740.1197655  924079.7231996  805704.1824674
  924007.8486035  805652.6193221    923960.97311  805611.9943723
  923909.4109888  805558.8693592
#Sta/Elev= 30
       0 2203.72   18.68 2189.23   26.03 2184.29   32.08 2178.56    36.6 2175.51
   43.06 2169.83   49.85 2163.22    56.2 2155.64   63.15 2151.53   82.85 2150.56
   105.3 2146.62  111.23 2145.45  122.95 2144.88  141.29 2145.65  144.432146.193
  152.27 2147.55  166.29 2148.95  169.49 2148.75  175.95 2150.85  189.62 2157.45
  196.73 2156.75  201.83 2156.98  217.46 2154.59  229.35 2155.11  235.26 2157.71
  242.95 2160.26  244.52 2161.82  251.69 2171.03  263.59 2181.26  288.66 2199.21
#Mann= 3 , 0 , 0
       0    .075       0   105.3     .05       0  144.43    .075       0
Bank Sta=105.3,144.43
Exp/Cntr=0.5,0.3

Type RM Length L Ch R = 1 ,95209   ,44.13,40.52,43.78
BEGIN DESCRIPTION:
95131.16
END DESCRIPTION:
XS GIS Cut Line= 4
  924193.7856374  805690.1195121  924150.0359278  805626.0573276
  924085.9737433  805568.2446627  924032.8487302  805490.1195229
#Sta/Elev= 30
       0 2200.58    12.7 2190.97   27.72 2180.28   34.49 2172.89   48.78 2163.54
   51.27 2160.82    55.3 2158.04   58.31 2154.79   67.72 2150.46   69.68 2150.02
   77.07 2150.59   94.992145.718  104.11 2143.14  105.39 2142.91  110.81 2142.86
  115.75 2143.02  124.38 2143.98  131.43 2145.68  146.11 2147.99  150.67 2149.42
  152.22 2149.52  173.99 2156.53  186.15 2157.82  200.44 2158.29  208.31 2157.34
  214.71 2158.67  216.83 2160.02  225.95 2168.59  247.14    2190  258.34 2200.86
#Mann= 3 , 0 , 0
       0     .07       0   94.99     .05       0  131.43    .075       0
#XS Ineff= 2 , 0
       0   94.27 2150.41  140.27       0 2150.41
Permanent Ineff=
       F       F
Bank Sta=94.99,131.43
Exp/Cntr=0.5,0.3

Type RM Length L Ch R = 3 ,95186   ,,,
Node Photo=H:\PROJ\06-0741\CE\GIS\DATA\FRENCH_BROAD_RIVER\SHAPEFILES\survey_data\photos\FBSTR_1247.JPG
BEGIN DESCRIPTION:
95111  FBSTR_1247
END DESCRIPTION:
Bridge Culvert--1,0,-1,-1, 0
Deck Dist Width WeirC Skew NumUp NumDn MinLoCord MaxHiCord MaxSubmerge Is_Ogee
13,10,2.6,0, 7, 7, , , 0.95, 0, 1,1,,
   77.58  104.27  104.27  117.27  130.27  130.27  154.89
 2150.48 2150.41 2150.41 2150.41 2150.41 2150.41 2150.37
                 2149.41 2149.41 2149.41
   78.44  111.56  111.56  124.56  137.56  137.56  160.53
 2150.38 2150.41 2150.41 2150.41 2150.41 2150.41 2150.41
                 2149.41 2149.41 2149.41
BR Coef=-1 , 0 , 0 ,, 0 ,,,0.8,0,,0,
WSPro=,,,, 1 ,,,, 0 ,,,, 0 ,,,,-1 ,-1 ,-1 , 0 , 0 , 0 , 0 , 0
BC Design=,, 0 ,, 0 ,,,,,,

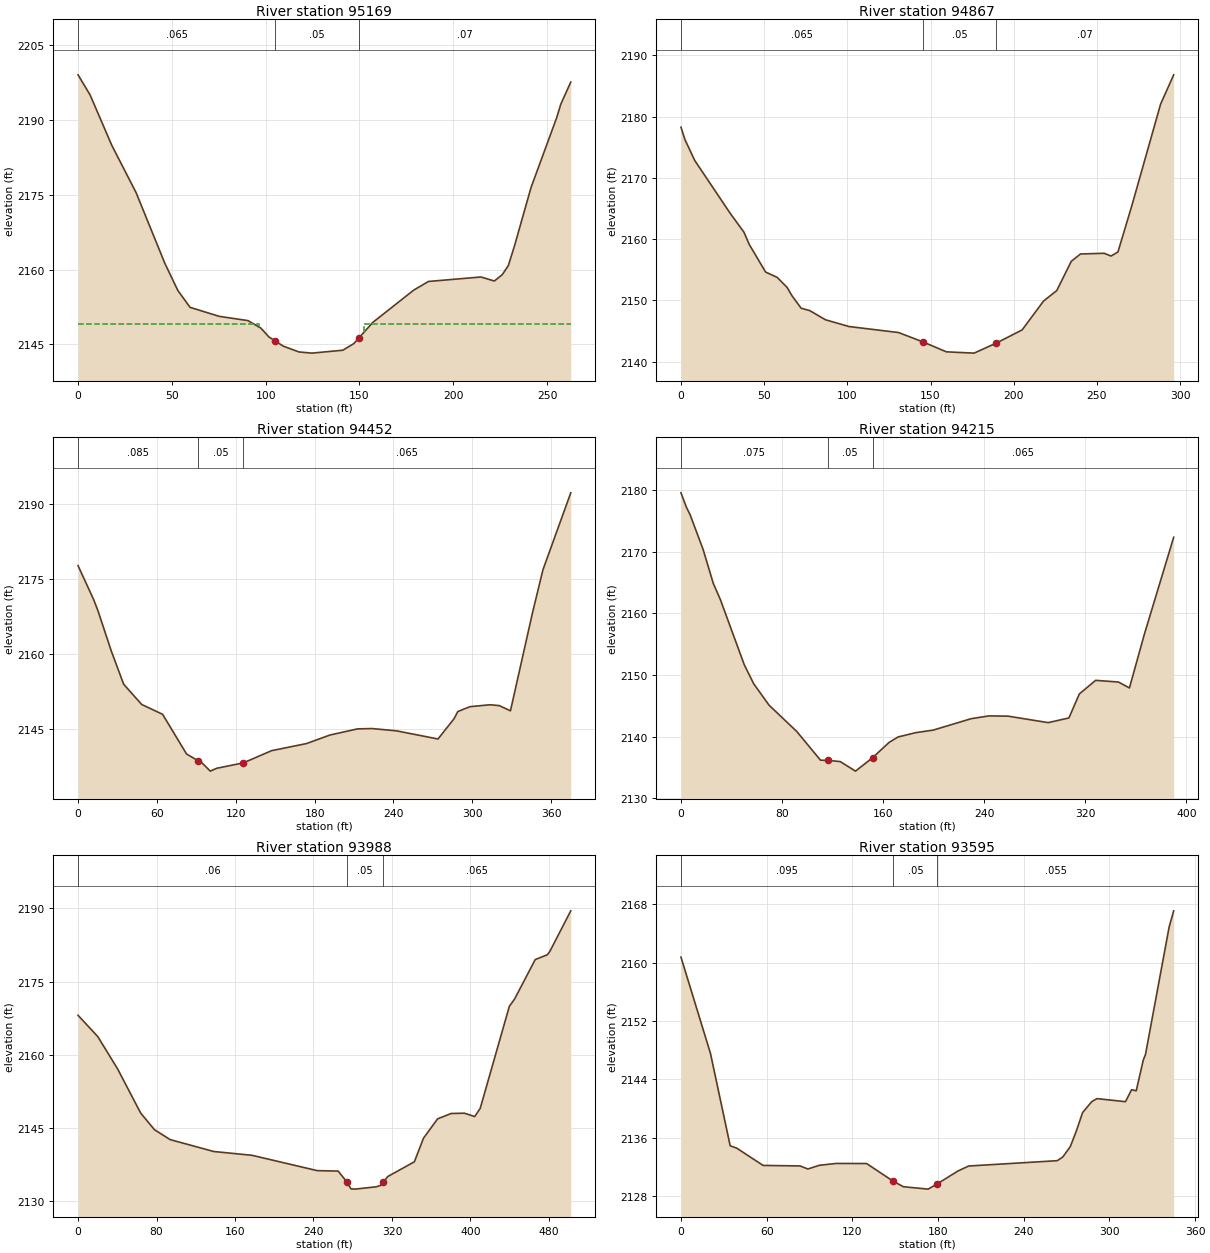
Type RM Length L Ch R = 1 ,95169   ,286.68,301.88,278.03
BEGIN DESCRIPTION:
95090.64
END DESCRIPTION:
XS GIS Cut Line= 5
  924234.4105872  805668.2451694  924192.2237696  805610.4325045
  924129.7234529  805552.6198396  924098.4738067  805511.9948898
  924070.3489202  805465.1193962
#Sta/Elev= 30
       0 2199.05    6.44 2195.01   17.95 2184.94   30.91 2175.45   46.28 2161.24
    53.2  2155.8   59.72 2152.42   75.19 2150.62    90.6 2149.76   97.48 2148.25
  101.72 2146.49  105.172145.656  109.33 2144.65  117.71 2143.48  124.56 2143.24
  141.12 2143.82  146.95 2145.14  149.762146.315  157.15 2149.41  178.86 2155.86
  186.76 2157.61  214.76 2158.51  221.89  2157.7  226.12 2158.98  229.36  2160.8
  232.61 2164.72  241.47 2176.47  255.09 2190.42  257.32 2193.16  262.63  2197.6
#Mann= 3 , 0 , 0
       0    .065       0  105.17     .05       0  149.76     .07       0
#XS Ineff= 2 , 0
       0   96.56    2149  152.56       0    2149
Permanent Ineff=
       F       F
Bank Sta=105.17,149.76
Exp/Cntr=0.5,0.3

Type RM Length L Ch R = 1 ,94867   ,465.8,414.39,307.61
BEGIN DESCRIPTION:
94788.76
END DESCRIPTION:
XS GIS Cut Line= 5
  924459.4107031  805486.9947631  924420.3486453  805438.5574017
   924370.348392  805365.1199137  924323.4739226  805319.8073121
  924254.7240863  805279.1823623
#Sta/Elev= 30
       0 2178.28    2.39 2176.26    8.27 2172.85   29.62 2164.21   37.88 2161.13
   40.98 2159.17   50.85 2154.64   57.83 2153.76   63.75 2152.14   66.69 2150.78
   72.22 2148.73   77.42 2148.34   86.89 2146.84  101.04 2145.74  130.76 2144.76
   145.42143.235  159.52 2141.61  176.17  2141.4   189.6 2143.05  205.03 2145.19
  217.94 2149.91  225.84 2151.61  234.58 2156.39  240.06 2157.58  254.32  2157.7
  258.49 2157.25  262.63 2157.92  271.02 2165.52  288.27 2182.06  296.12 2186.83
#Mann= 3 , 0 , 0
       0    .065       0   145.4     .05       0   189.6     .07       0
Bank Sta=145.4,189.6
Exp/Cntr=0.3,0.1

Type RM Length L Ch R = 1 ,94452   ,257.85,237.07,97.85
BEGIN DESCRIPTION:
94374.37
END DESCRIPTION:
XS GIS Cut Line= 6
  924729.7234206  805086.9947846  924656.2859326   805060.431766
  924618.7857426   805043.245075  924542.2234947  805026.0573599
   924482.848962  805018.2449484  924365.6607402  805019.8068162
#Sta/Elev= 30
       0 2177.74   11.75 2171.03   15.21 2168.69   25.22 2160.72   34.71 2154.02
   48.47 2149.96   64.33    2148   82.56 2140.06   91.51 2138.68   93.99 2138.36
  100.62 2136.63  105.53  2137.2  125.75 2138.28  147.35 2140.73  173.77 2142.14
  191.65 2143.85  212.63 2145.08  223.62 2145.15  242.35 2144.69  273.89 2143.06
  286.13 2147.13  288.92 2148.54  293.91 2149.08  298.33 2149.53  313.47 2149.91
   320.5 2149.74  329.01  2148.7  345.77  2168.3  353.73 2176.92   374.9 2192.32
#Mann= 3 , 0 , 0
       0    .085       0   91.51     .05       0  125.75    .065       0
Bank Sta=91.51,125.75
Exp/Cntr=0.3,0.1

Type RM Length L Ch R = 1 ,94215   ,212.71,226.88,177.99
BEGIN DESCRIPTION:
94137.30
END DESCRIPTION:
XS GIS Cut Line= 6
  924725.0357688  804832.3068903  924660.9735843  804813.5573074
  924635.9734577  804815.1201993  924557.8483179  804849.4946054
  924475.0365504  804904.1825105  924364.0988724  804922.9320934
#Sta/Elev= 30
       0 2179.56    4.29 2177.22    7.24    2176   17.48  2170.4   25.62 2164.84
   31.09 2162.29   50.13 2151.65   57.55 2148.59   69.66 2145.12   91.68 2140.83
  110.48 2136.17  116.04 2136.15  126.07 2135.95  138.16  2134.4  151.62 2136.56
   164.7 2139.05  171.83 2139.94  185.77 2140.64  199.76 2141.06  229.72 2142.91
  243.84 2143.36  258.97 2143.32  290.71 2142.27  307.12 2143.03  315.35 2146.92
  328.24 2149.13  346.27 2148.86  355.03  2147.9  366.79 2156.57  390.06 2172.35
#Mann= 3 , 0 , 0
       0    .075       0  116.04     .05       0  151.62    .065       0
Bank Sta=116.04,151.62
Exp/Cntr=0.3,0.1

Type RM Length L Ch R = 1 ,93988   ,503.52,393.06,344.17
BEGIN DESCRIPTION:
93910.42
END DESCRIPTION:
XS GIS Cut Line= 6
  924712.5357055  804593.2448432  924565.6607294  804619.8068377
  924457.8488353  804660.4317875  924420.3486453  804688.5576982
  924309.4109673  804785.4324209  924293.7861441  804826.0573707
#Sta/Elev= 30
       0 2168.11   20.14 2163.74   40.43 2157.09   63.78  2148.1   77.86 2144.68
   93.86 2142.64  138.35  2140.2  177.39 2139.42   243.8 2136.28  265.16 2136.19
  274.23 2133.91  278.19 2132.55  282.24 2132.49  304.03 2132.97  308.72 2133.27
  311.38 2133.96   315.7 2135.07  342.86 2138.09  352.15 2142.93  366.54 2146.89
  380.37 2147.99  393.92 2148.05  404.35 2147.36  409.97 2149.04   439.7 2169.96
  445.04 2171.45  466.05 2179.53  478.44 2180.52  480.98 2181.21  502.29 2189.52
#Mann= 3 , 0 , 0
       0     .06       0  274.23     .05       0  311.38    .065       0
Bank Sta=274.23,311.38
Exp/Cntr=0.3,0.1

Type RM Length L Ch R = 1 ,93595   ,410.32,311.76,142.55
BEGIN DESCRIPTION:
93517.35
END DESCRIPTION:
XS GIS Cut Line= 6
  924190.6608776  804315.1197142  924131.2863449  804435.4326958
  924098.4738067   804468.245234  924081.2860916  804504.1825321
    924073.47368  804541.6827221  924081.2860916  804627.6192493
#Sta/Elev= 30
       0 2160.76   20.67 2147.55   34.46 2134.89   38.96 2134.58   57.51  2132.2
   83.38 2132.13   88.88 2131.71   96.94 2132.22  108.59 2132.47  129.98 2132.46
  148.61 2130.03  155.74 2129.28  173.05 2128.95  179.58 2129.69  193.99 2131.44
  201.46 2132.12  263.49 2132.85  267.36 2133.36  272.61 2134.78  276.81  2136.9
  281.21 2139.44  287.59 2140.94  291.31 2141.36  311.25 2140.94  315.54 2142.58
  318.77 2142.43   323.7 2146.63  325.28 2147.43  341.82 2164.89  345.01 2167.11
#Mann= 3 , 0 , 0
       0    .095       0  148.61     .05       0  179.58    .055       0
Bank Sta=148.61,179.58
Exp/Cntr=0.3,0.1

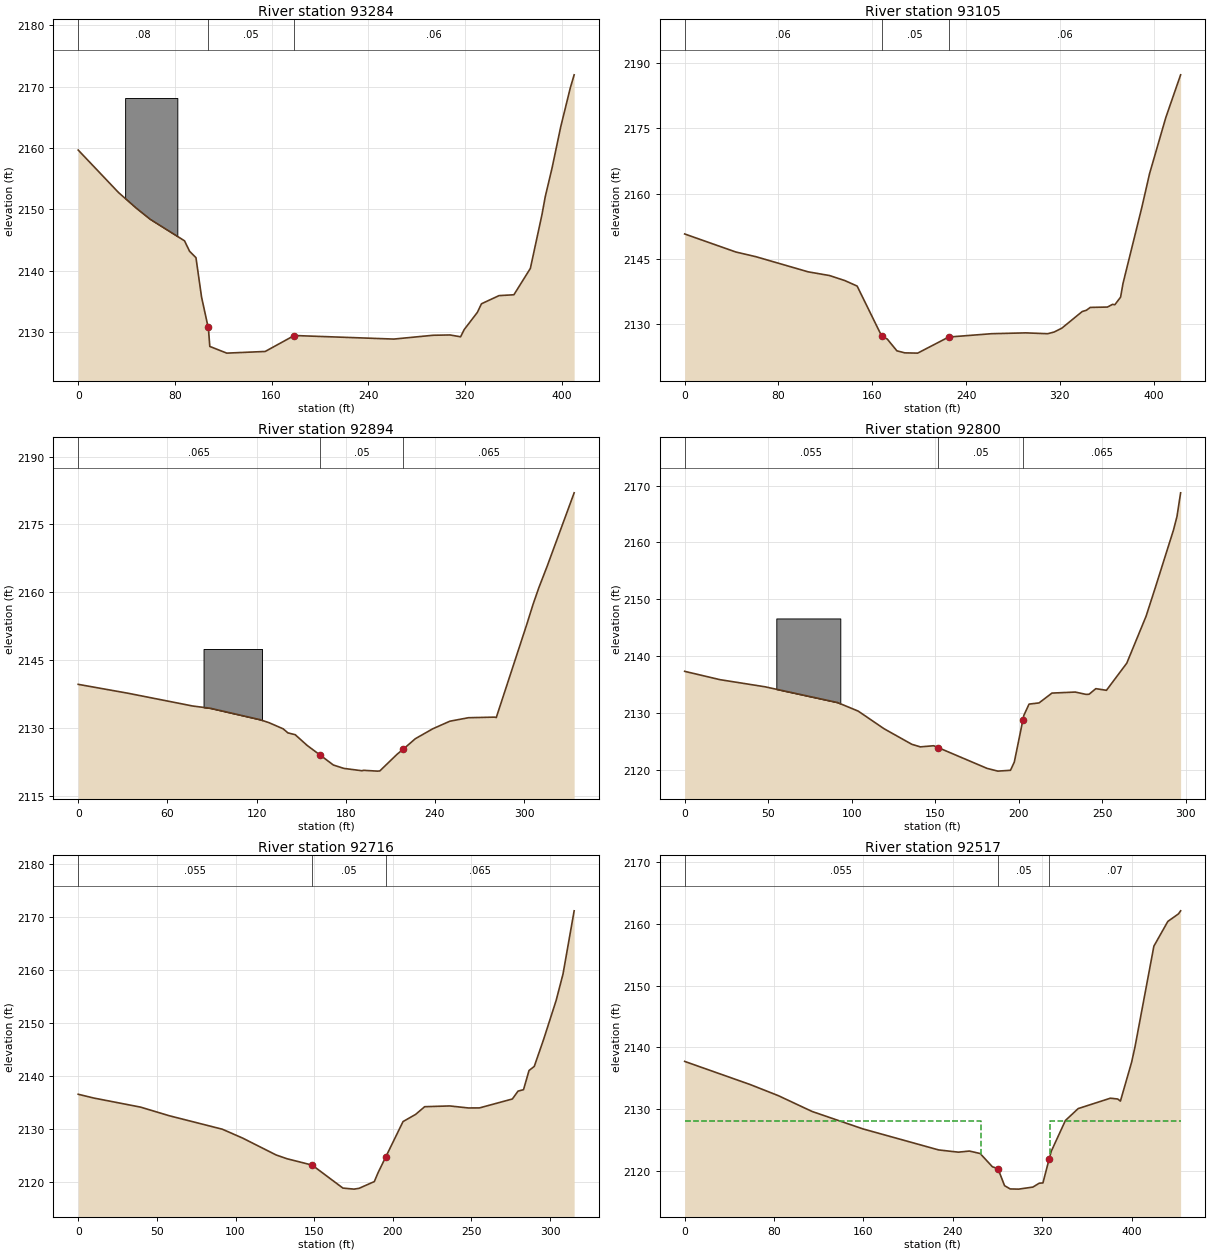
Type RM Length L Ch R = 1 ,93284   ,211.79,178.95,95.52
BEGIN DESCRIPTION:
93205.59
END DESCRIPTION:
XS GIS Cut Line= 6
  923750.0359494  804336.9950811   923776.598968  804402.6201575
  923814.0981339  804457.3070385  923845.3488043  804496.3701205
  923937.5358753  804624.4944895  923973.4731733  804679.1823946
#Sta/Elev= 30
       0 2159.68   33.31 2152.77   47.84 2150.25   59.43 2148.42   87.98 2144.89
   92.16 2143.19   97.45 2142.14  102.08 2135.72  107.432130.885  107.79 2130.56
  108.89 2127.68  122.94 2126.59  154.73 2126.86  178.77 2129.46  261.17 2128.88
  293.61  2129.5   307.7 2129.55  316.44 2129.25  319.38 2130.42  330.31 2133.23
   333.7 2134.63  348.23 2135.96  360.55  2136.1  374.18  2140.4  383.79 2149.17
  386.49 2152.08  392.12 2156.75  399.31 2163.48  407.21  2169.8  410.41 2171.94
#Mann= 3 , 0 , 0
       0     .08       0  107.43     .05       0  178.77     .06       0
#Block Obstruct= 1 ,-1
   38.82   82.022168.162
Bank Sta=107.43,178.77
Exp/Cntr=0.3,0.1

Type RM Length L Ch R = 1 ,93105   ,193.51,210.51,223.07
BEGIN DESCRIPTION:
93026.64
END DESCRIPTION:
XS GIS Cut Line= 6
  923621.9115804  804461.9946903  923648.4735749  804568.2447166
  923742.2235378  804613.5573181  923803.1609625  804641.6822046
  923857.8488676  804679.1823946  923903.1614692  804740.1198193
#Sta/Elev= 30
       0 2150.72   43.63 2146.57   60.74 2145.49  105.25 2142.01   123.6 2141.15
  136.65 2139.99   147.1 2138.73  168.22 2127.13  172.75 2126.55  181.01 2123.83
  187.81 2123.36  198.73  2123.3  225.18    2127  261.82 2127.77  290.87 2127.96
  309.61 2127.77  315.11 2128.15  321.73 2129.05  339.07 2132.87  342.65 2133.17
  345.93 2133.82   360.6  2133.9  364.93 2134.52  366.91 2134.44  371.81 2136.18
  373.86 2139.33  389.87 2156.77  396.51 2164.59  410.34 2177.48  423.01 2187.34
#Mann= 3 , 0 , 0
       0     .06       0  168.22     .05       0  225.18     .06       0
Bank Sta=168.22,225.18
Exp/Cntr=0.3,0.1

Type RM Length L Ch R = 1 ,92894   ,42.23,93.61,116.82
BEGIN DESCRIPTION:
92816.14
END DESCRIPTION:
XS GIS Cut Line= 6
  923545.3483084  804636.9945528  923545.3483084  804702.6196293
   923571.911327  804740.1198193  923621.9115804  804782.3076611
  923670.3489417  804819.8068269  923743.7864298  804880.7442517
#Sta/Elev= 30
       0 2139.65   33.88 2137.66   77.01 2134.86   89.07 2134.35  122.15 2131.85
  128.25 2131.19  137.92 2129.81  141.07 2128.92  146.03 2128.51  154.01 2126.15
  162.97 2123.96  171.68 2121.81  178.66 2121.07  190.96 2120.54  191.98 2120.64
  201.29 2120.46  202.92  2120.5  214.45 2124.16  218.822125.352  226.83 2127.63
  238.66 2129.84  250.09  2131.5  262.57 2132.27  280.13  2132.4  281.28 2132.31
  301.79 2152.89  306.04 2157.35  309.88 2160.98  315.58 2165.82  333.68    2182
#Mann= 3 , 0 , 0
       0    .065       0  162.97     .05       0  218.82    .065       0
#Block Obstruct= 1 ,-1
   84.32  123.682147.473
Bank Sta=162.97,218.82
Exp/Cntr=0.3,0.1

Type RM Length L Ch R = 1 ,92800   ,45.8,84.59,121.38
BEGIN DESCRIPTION:
92722.53
END DESCRIPTION:
XS GIS Cut Line= 5
  923528.1605932  804676.0576348  923537.5358968   804763.557054
  923556.2865039  804824.4944787  923589.0990421  804890.1195552
  923637.5364035  804943.2445683
#Sta/Elev= 30
       0 2137.29   21.19 2135.82    48.1 2134.57   91.48  2131.8  103.91 2130.29
  119.43 2127.18  135.99 2124.45  141.12 2123.99  149.14 2124.19  151.76 2123.87
  181.12  2120.2   187.6 2119.72  195.13 2119.87  197.42 2121.32  202.582128.753
  203.12 2129.53  206.24 2131.52  212.24 2131.73  219.96 2133.46  233.95 2133.64
  240.38 2133.23  242.22 2133.26  246.23 2134.24   252.6 2133.95  264.76 2138.72
  276.33 2146.99  281.99 2152.15  292.74 2162.16  294.85 2164.56  297.02 2168.72
#Mann= 3 , 0 , 0
       0    .055       0  151.76     .05       0  202.58    .065       0
#Block Obstruct= 1 ,-1
   54.88    93.22146.602
Bank Sta=151.76,202.58
Exp/Cntr=0.3,0.1

Type RM Length L Ch R = 1 ,92716   ,167.12,198.9,198.74
BEGIN DESCRIPTION:
92637.95
END DESCRIPTION:
XS GIS Cut Line= 6
  923509.4110103  804680.7442624  923489.0985354  804772.9323576
  923487.5356434  804821.3697189  923489.0985354  804886.9947954
  923495.3490792  804938.5569166  923514.0986621  804990.1200619
#Sta/Elev= 30
       0  2136.6    9.87 2135.89   39.61 2134.18   57.85 2132.56   91.65 2130.02
  104.41 2128.37  125.81 2125.18  132.71 2124.47  148.74 2123.27  168.26 2118.95
  175.34 2118.75  178.55  2118.9  188.26 2120.17  190.72 2121.89  195.642124.868
  206.52 2131.46  214.51 2132.81  220.29 2134.26  236.23  2134.4  248.09 2134.02
  255.13 2134.03  276.03 2135.71  279.62 2137.19  283.12 2137.46  286.62 2141.07
  289.94 2141.83  295.91 2146.93  303.89 2154.28  308.24 2159.24  315.31 2171.11
#Mann= 3 , 0 , 0
       0    .055       0  148.74     .05       0  195.64    .065       0
Bank Sta=148.74,195.64
Exp/Cntr=0.5,0.3

Type RM Length L Ch R = 1 ,92517   ,80.57,62.86,51.66
BEGIN DESCRIPTION:
92439.05
END DESCRIPTION:
XS GIS Cut Line= 6
  923391.9278259  804607.5996886  923314.0986729  804782.3076611
    923295.34909  804865.1194285  923298.4738497  804954.1817397
  923321.9110844  805007.3067528  923335.9740398  805021.3697082
#Sta/Elev= 30
       0 2137.73   58.46    2134   83.72  2132.2  114.08 2129.63  159.61 2126.81
  227.33 2123.41     245 2123.05  254.89 2123.23  264.48 2122.83  275.43 2120.69
  280.44 2120.38  286.33 2117.63  291.39  2117.1  298.97 2117.07  311.69  2117.4
  317.38 2118.03  320.68 2118.07  326.16 2121.88  328.18 2123.21  340.82 2128.18
  352.23  2130.1  381.08 2131.78  387.55 2131.65  390.03 2131.31  400.06  2137.6
  403.07 2140.07     420 2156.38  432.49 2160.38  442.01  2161.6  443.92 2162.09
#Mann= 3 , 0 , 0
       0    .055       0  280.44     .05       0  326.16     .07       0
#XS Ineff= 2 , 0
       0  265.38 2128.13  327.38       0 2128.13
Permanent Ineff=
       F       F
Bank Sta=280.44,326.16
Exp/Cntr=0.5,0.3

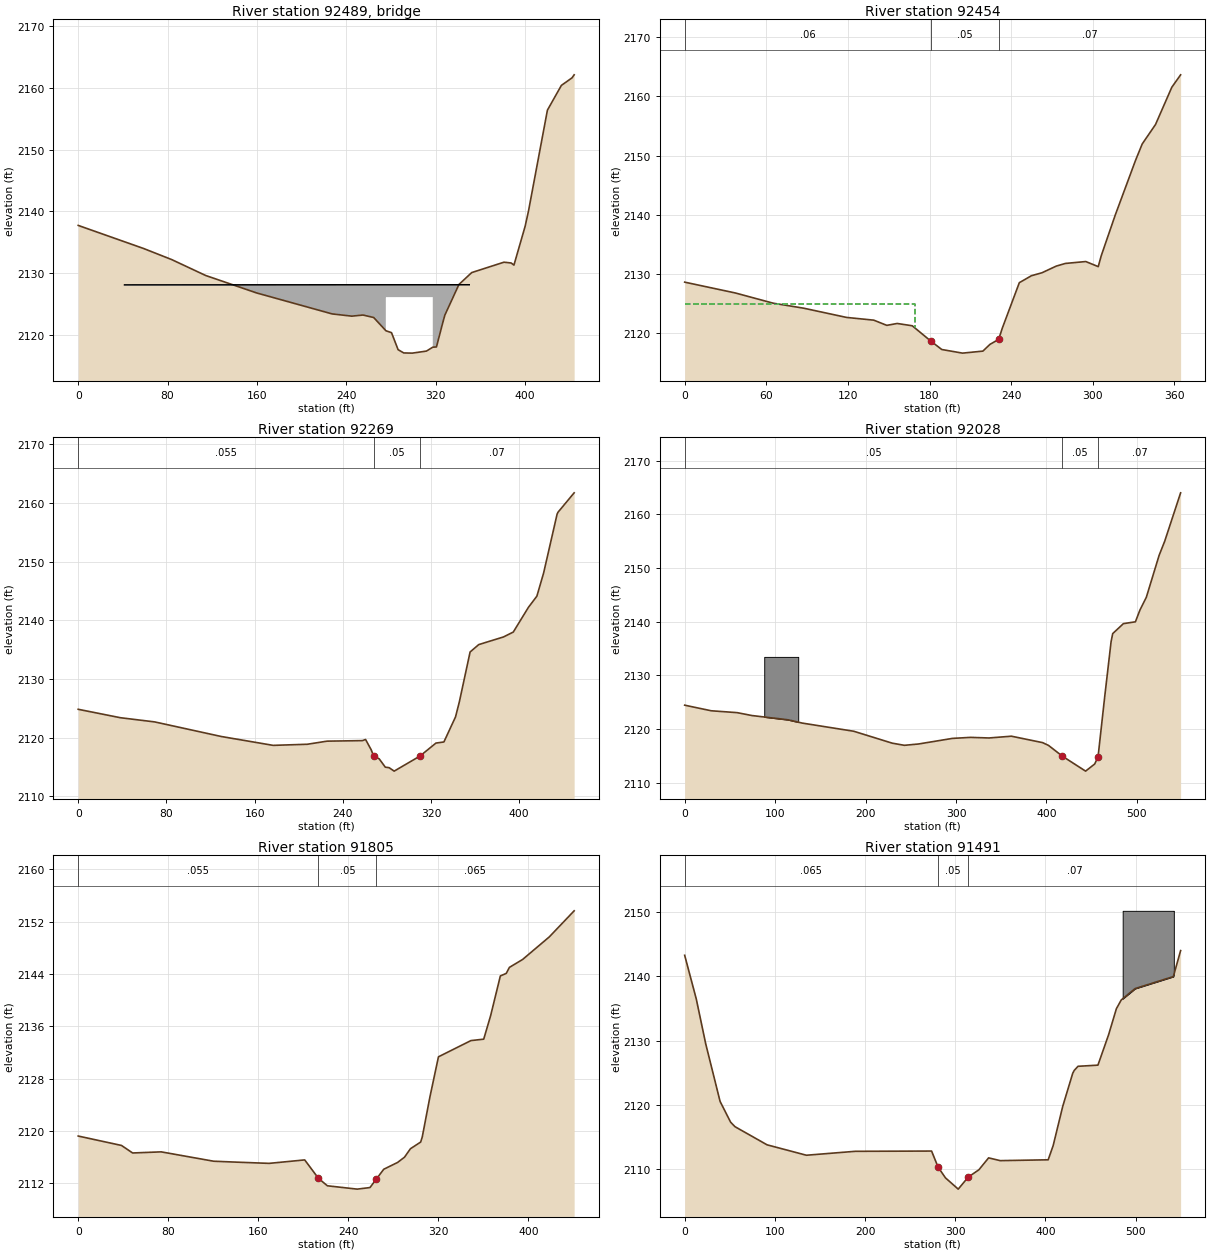
Type RM Length L Ch R = 3 ,92489   ,,,
Node Photo=H:\PROJ\06-0741\CE\GIS\DATA\FRENCH_BROAD_RIVER\SHAPEFILES\survey_data\photos\FBSTR_1241.JPG
BEGIN DESCRIPTION:
92409  FBSTR_1241
END DESCRIPTION:
Bridge Culvert--1,0,-1,-1, 0
Deck Dist Width WeirC Skew NumUp NumDn MinLoCord MaxHiCord MaxSubmerge Is_Ogee
20,24,2.6,0, 7, 7, , , 0.95, 0, 1,1,,
   41.45  275.38  275.38  296.38  317.38  317.38     350
 2128.11 2128.13 2128.13 2128.13 2128.13 2128.13 2128.13
                 2126.13 2126.13 2126.13
   11.39  184.12  184.12  205.12  226.12  226.12  245.38
 2128.16 2128.13 2128.13 2128.13 2128.13 2128.13 2128.18
                 2126.13 2126.13 2126.13
BR Coef=-1 , 0 , 0 ,, 0 ,,,0.8,0,,0,
WSPro=,,,, 1 ,,,, 0 ,,,, 0 ,,,,-1 ,-1 ,-1 , 0 , 0 , 0 , 0 , 0
BC Design=,, 0 ,, 0 ,,,,,,

Type RM Length L Ch R = 1 ,92454   ,191.62,185.5,174.98
BEGIN DESCRIPTION:
92376.19
END DESCRIPTION:
XS GIS Cut Line= 6
  923262.5365517  804701.0567373  923242.2240768  804768.2447058
  923232.8487733  804919.8073336  923246.9107044  804958.8693915
  923264.0984195   805024.494468  923253.1612482  805055.7451384
#Sta/Elev= 30
       0 2128.64   37.28 2126.81   65.15 2125.08   87.49 2124.24  118.99 2122.68
  138.99 2122.22   148.6 2121.34   156.2 2121.66   167.3 2121.27  180.942118.681
  188.98 2117.26  204.22 2116.65  219.19 2116.99  224.35 2118.12  230.78 2118.97
  233.52  2120.9  245.99 2128.55  254.83 2129.72  262.69 2130.23  273.12 2131.35
  279.85  2131.8  294.82 2132.12  303.99 2131.26  306.21 2133.11  316.41 2139.92
  331.43 2149.23  336.31 2151.98  346.12 2155.28  358.09 2161.57  364.54 2163.66
#Mann= 3 , 0 , 0
       0     .06       0  180.94     .05       0  230.78     .07       0
#XS Ineff= 2 , 0
       0  169.12    2125  241.12       0    2125
Permanent Ineff=
       F       F
Bank Sta=180.94,230.78
Exp/Cntr=0.5,0.3

Type RM Length L Ch R = 1 ,92269   ,102.33,240.83,287.87
BEGIN DESCRIPTION:
92190.69
END DESCRIPTION:
XS GIS Cut Line= 6
  923104.7233801  804713.5568007  923054.7231267  804771.3694656
   923031.285892  804833.8697823   923031.285892   804894.807207
  923068.7860821  804997.9324735  923121.9110952  805122.9320827
#Sta/Elev= 30
       0 2124.86   38.41 2123.42   69.37 2122.71  129.84 2120.22  176.83 2118.71
  207.82  2118.9  225.77 2119.43  257.72 2119.52  260.67 2119.71   265.7 2117.98
  267.97  2116.9  272.98 2116.42  278.58 2114.99  281.98 2114.91   286.6 2114.32
  309.95 2116.88  324.49  2119.1  331.71 2119.29  342.25 2123.56  345.69  2126.1
  355.48 2134.63  363.32 2135.89  385.75 2137.19  394.66 2138.03  408.35 2142.23
  416.06 2144.15  422.16 2148.09  434.37 2158.11  435.21 2158.45  449.86 2161.76
#Mann= 3 , 0 , 0
       0    .055       0  267.97     .05       0  309.95     .07       0
Bank Sta=267.97,309.95
Exp/Cntr=0.3,0.1

Type RM Length L Ch R = 1 ,92028   ,283.21,222.34,172.77
BEGIN DESCRIPTION:
91949.86
END DESCRIPTION:
XS GIS Cut Line= 6
  923045.3488474  804666.6823313  922951.5988844  804791.6819405
  922912.5358024  804846.3698456  922882.8490481  804902.6196185
  922867.2232008   804968.244695  922798.4733646  805149.4951013
#Sta/Elev= 30
       0 2124.42    29.3 2123.38   57.98 2123.03   74.39 2122.49  114.19  2121.7
  129.79 2121.09  186.98 2119.56  229.51 2117.34  242.96 2116.94  258.65 2117.19
  296.08 2118.23  316.03 2118.42  336.45 2118.31   361.3 2118.64  395.81 2117.44
  402.35 2116.92  417.77  2114.9  443.31 2112.13  453.45 2113.47  457.13 2114.85
  464.45 2126.01  471.51 2136.27  473.28 2137.76  485.12 2139.62  498.39 2139.96
   503.4 2142.15  510.48 2144.54  524.57 2152.33  530.81 2154.99  548.38    2164
#Mann= 3 , 0 , 0
       0     .05       0  417.77     .05       0  457.13     .07       0
#Block Obstruct= 1 ,-1
   87.96  125.542133.424
Bank Sta=417.77,457.13
Exp/Cntr=0.3,0.1

Type RM Length L Ch R = 1 ,91805   ,401.29,314.29,263
BEGIN DESCRIPTION:
91727.53
END DESCRIPTION:
XS GIS Cut Line= 6
  922695.3480981  804736.9950595   922662.536584  804849.4946054
  922628.1611538  804977.6199986  922628.1611538  805029.1821197
  922645.3488689  805091.6824364  922692.2233383  805149.4951013
#Sta/Elev= 30
       0  2119.2   38.48 2117.76   48.34 2116.61   73.74 2116.78   120.3 2115.35
  141.69  2115.2  169.66 2115.02  201.25 2115.55  213.47 2112.73   221.4 2111.59
  247.93 2111.08  259.25 2111.32  264.942112.628  271.48 2114.12  283.76 2115.16
   289.9 2115.96   295.2 2117.26  304.28 2118.28  305.69 2119.05  312.54 2125.21
  320.09 2131.32  348.94  2133.8   360.3 2134.02  366.46 2137.62  375.09 2143.69
  380.33 2144.08  383.14    2145  394.87 2146.21  418.56 2149.66  440.66 2153.65
#Mann= 3 , 0 , 0
       0    .055       0  213.47     .05       0  264.94    .065       0
Bank Sta=213.47,264.94
Exp/Cntr=0.3,0.1

Type RM Length L Ch R = 1 ,91491   ,250.26,302.63,263.97
BEGIN DESCRIPTION:
91413.24
END DESCRIPTION:
XS GIS Cut Line= 6
  922216.6863118  804738.1820791  922310.9739669  804982.3076503
  922331.2864418   805043.245075  922367.2237399  805132.3073862
   922420.348753  805190.1200511  922435.9735761  805236.9945205
#Sta/Elev= 30
       0 2143.28   12.83 2136.51   23.32 2129.52   39.26 2120.56   50.91 2117.34
   55.78 2116.63   91.35 2113.81  134.98 2112.19  189.03  2112.8  273.78 2112.84
  280.98 2110.34  289.18 2108.67  303.31 2106.92  314.41 2108.79  326.24 2109.93
  336.99 2111.78  349.86 2111.35  403.05 2111.48  408.58 2113.69  419.19 2119.79
  430.26 2124.93  431.94 2125.38  436.13 2126.02  458.22  2126.2  470.08 2130.94
  478.69 2134.98  484.09 2136.34  499.42  2138.1  541.83 2139.97   549.9 2144.01
#Mann= 3 , 0 , 0
       0    .065       0  280.98     .05       0  314.41     .07       0
#Block Obstruct= 1 ,-1
  485.65  542.372150.197
Bank Sta=280.98,314.41
Exp/Cntr=0.5,0.3