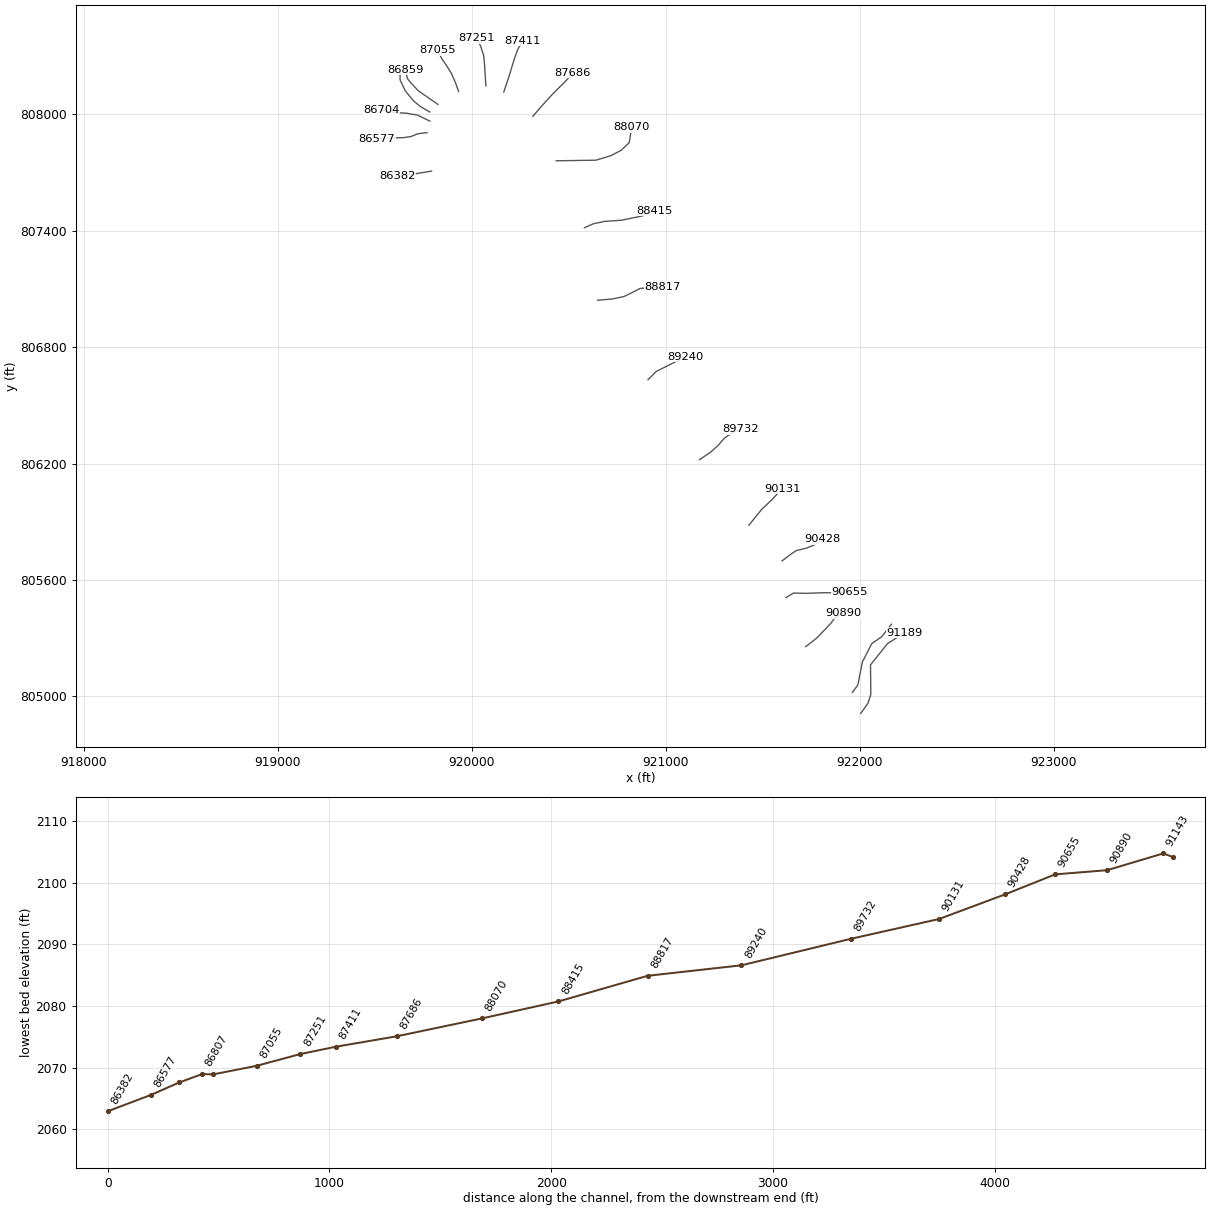
HEC-RAS study lds_big_laurel_crk.prj: lds_big_laurel_crk

--- lds_big_laurel_crk.g20 (geometry) --- (continued)

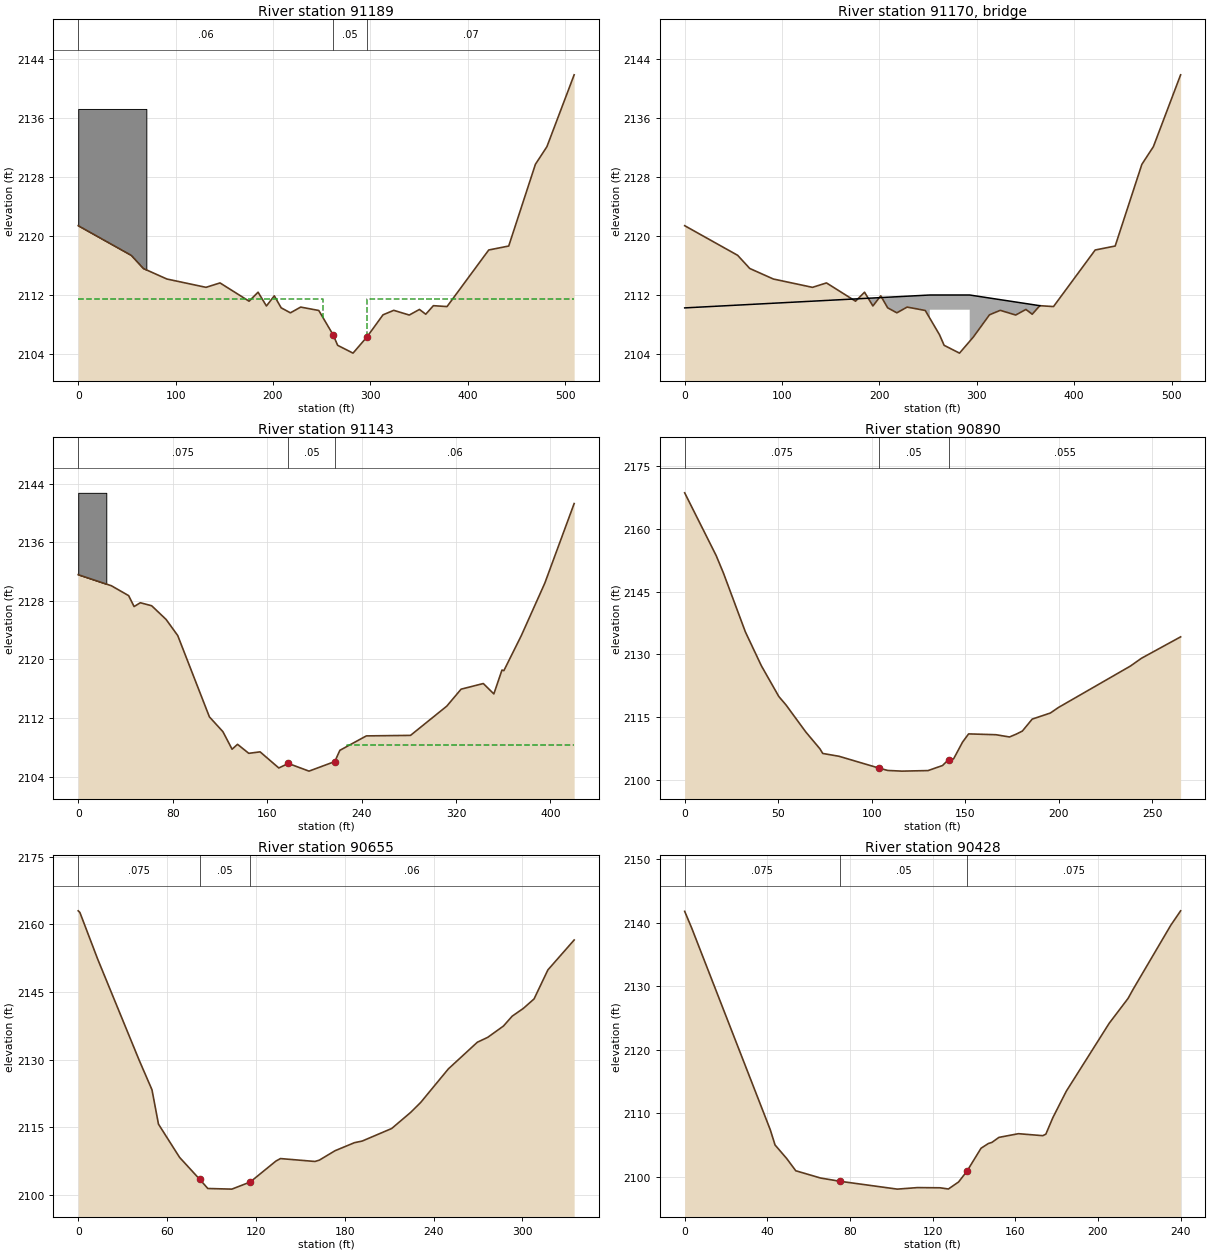
Type RM Length L Ch R = 1 ,91189   ,98.96,45.55,54
BEGIN DESCRIPTION:
91110.60
END DESCRIPTION:
XS GIS Cut Line= 6
  922004.7239514  804911.9949221  922042.2231172  804965.1199352
  922056.2860726  805010.4325368  922054.7231806  805161.9951647
  922142.2236239  805271.3699507  922229.7240673  805327.6197237
#Sta/Elev= 30
       0 2121.41   54.39 2117.39   66.86  2115.6   91.09 2114.17  131.25 2113.04
  145.64 2113.64  175.47 2111.16  184.72 2112.38  193.32 2110.51  201.37 2111.89
  208.45 2110.26  217.94 2109.58  228.49 2110.36  247.07  2109.9  261.71 2106.61
  266.46 2105.17  282.24 2104.11  296.45 2106.29  313.04 2109.31  324.11 2109.92
  339.98 2109.28  350.46 2110.04  356.93 2109.39  364.76 2110.55  378.79 2110.43
   421.6 2118.11  442.14 2118.65  469.54 2129.74  481.38 2132.14  509.34 2141.89
#Mann= 3 , 0 , 0
       0     .06       0  261.71     .05       0  296.45     .07       0
#XS Ineff= 2 , 0
       0  251.62  2111.5  296.45       0  2111.5
Permanent Ineff=
       F       F
#Block Obstruct= 1 ,-1
       0   69.962137.261
Bank Sta=261.71,296.45
Exp/Cntr=0.5,0.3

Type RM Length L Ch R = 3 ,91170   ,,,
BEGIN DESCRIPTION:
91085
END DESCRIPTION:
Bridge Culvert--1,0,-1,-1, 0
Deck Dist Width WeirC Skew NumUp NumDn MinLoCord MaxHiCord MaxSubmerge Is_Ogee
17,19,2.6,0, 4, 4, , , 0.95, 0, 0,0,,
       0  251.74  292.74  364.76
 2110.25    2112    2112 2110.55
            2110    2110
  122.59     187     228  289.53
 2110.12    2112    2112 2111.01
            2110    2110
BR Coef=-1 , 0 , 0 ,, 0 ,,,0.8,0,,0,
WSPro=,,,, 1 ,,,, 0 ,,,, 0 ,,,,-1 ,-1 ,-1 , 0 , 0 , 0 , 0 , 0
BC Design=,, 0 ,, 0 ,,,,,,

Type RM Length L Ch R = 1 ,91143   ,322.7,253.46,262.76
BEGIN DESCRIPTION:
91065.05
END DESCRIPTION:
XS GIS Cut Line= 6
  921960.9732176  805019.8068162  921989.0981041  805057.3070062
   922012.536363  805176.0570958  922060.9737243  805271.3699507
  922112.5358455  805307.3072488  922162.5360988  805371.3694333
#Sta/Elev= 30
       0 2131.56   28.09 2130.05   42.72  2128.7   47.34 2127.21    52.6 2127.73
    62.2 2127.32   74.44 2125.45    84.3 2123.25  111.11 2112.15  122.59 2110.12
  130.32 2107.73  134.95  2108.4  144.46 2107.17  154.05 2107.37  169.92 2105.17
  177.96 2105.79  195.47 2104.74  217.292106.044  221.63 2107.58  244.05 2109.55
  281.46 2109.62  312.16 2113.61  324.31 2115.93  343.12  2116.7  352.05 2115.28
  358.92 2118.54  360.53 2118.46  375.33 2123.25   395.2  2130.4  420.06 2141.27
#Mann= 3 , 0 , 0
       0    .075       0  177.96     .05       0  217.29     .06       0
#XS Ineff= 2 , 0
       0   164.9 2105.69     228       0 2108.37
Permanent Ineff=
       F       F
#Block Obstruct= 1 ,-1
       0   23.772142.736
Bank Sta=177.96,217.29
Exp/Cntr=0.5,0.3

Type RM Length L Ch R = 1 ,90890   ,266.74,234.64,147.06
BEGIN DESCRIPTION:
90811.59
END DESCRIPTION:
XS GIS Cut Line= 6
  921720.3482786  805255.7451276  921775.0361837  805297.9319452
  921821.9106531  805346.3693066  921850.0365638   805376.057085
  921870.3490387  805404.1819715   921917.223508  805429.1820982
#Sta/Elev= 30
       0 2168.68   16.84 2153.65   20.73 2149.46   32.44 2135.39   40.98 2127.28
   50.35 2119.89   54.19 2117.87   64.76  2111.4   72.31 2107.37   73.84 2106.25
    82.5 2105.58  103.88 2102.75  108.57 2102.18   116.1 2102.02  130.13 2102.15
  137.87 2103.36  141.14  2104.8  143.77 2104.94  148.61 2108.99  151.83 2110.94
  166.45 2110.74   173.7  2110.2  177.37  2110.9  180.55 2111.61  185.83 2114.48
  195.55 2115.94  199.85 2117.26  238.32 2127.18  244.28 2129.06  265.19 2134.18
#Mann= 3 , 0 , 0
       0    .075       0  103.88     .05       0  141.14    .055       0
Bank Sta=103.88,141.14
Exp/Cntr=0.3,0.1

Type RM Length L Ch R = 1 ,90655   ,202.96,226.84,265.6
BEGIN DESCRIPTION:
90576.95
END DESCRIPTION:
XS GIS Cut Line= 6
  921618.7859041    805508.87013  921657.8489861  805532.3073647
  921721.9111706  805530.7444727  921810.9734818  805533.8702567
  921892.2233814  805533.8702567  921946.9112865  805538.5568843
#Sta/Elev= 30
       0    2163    1.13 2162.64   13.14 2152.31   41.12 2129.94   49.82 2123.35
    54.2 2115.74   68.47 2108.37   82.12 2103.49   87.52 2101.48  103.76 2101.34
  116.12 2102.91  133.52 2107.56  136.59 2108.11  159.86 2107.47  162.82 2107.76
  173.45 2109.85  186.53 2111.63  191.77 2111.99  211.69 2114.77  224.54 2118.35
  231.32 2120.56  249.97 2127.98  269.55 2133.89  276.55 2134.97  287.19 2137.48
  293.06 2139.66  300.59 2141.38  307.84 2143.48  317.18 2149.91  334.91 2156.54
#Mann= 3 , 0 , 0
       0    .075       0   82.12     .05       0  116.12     .06       0
Bank Sta=82.12,116.12
Exp/Cntr=0.3,0.1

Type RM Length L Ch R = 1 ,90428   ,265.71,297.02,329.38
BEGIN DESCRIPTION:
90350.11
END DESCRIPTION:
XS GIS Cut Line= 6
  921598.4734292  805697.9319237  921643.7860308  805732.3073539
  921671.9109172  805751.0569368  921723.4740626  805763.5570002
  921762.5361204  805779.1818233   921807.848722  805808.8696017
#Sta/Elev= 28
       0 2141.78    3.44 2139.12   41.43 2107.41   43.74 2105.02   49.33 2102.91
   53.75 2100.97   65.82 2099.82   75.02 2099.32  102.88 2098.08  112.61 2098.32
  123.59 2098.29  127.61  2098.1  132.55 2099.21  136.63 2100.92   143.4 2104.51
  146.98 2105.26  148.67 2105.43  152.06 2106.22  161.51  2106.8  173.28 2106.49
  174.77 2106.73  178.18 2109.34  184.64 2113.47  205.42 2124.17  214.57 2128.09
  216.89 2129.46  235.24  2139.6  239.98 2141.86
#Mann= 3 , 0 , 0
       0    .075       0   75.02     .05       0  136.63    .075       0
Bank Sta=75.02,136.63
Exp/Cntr=0.3,0.1

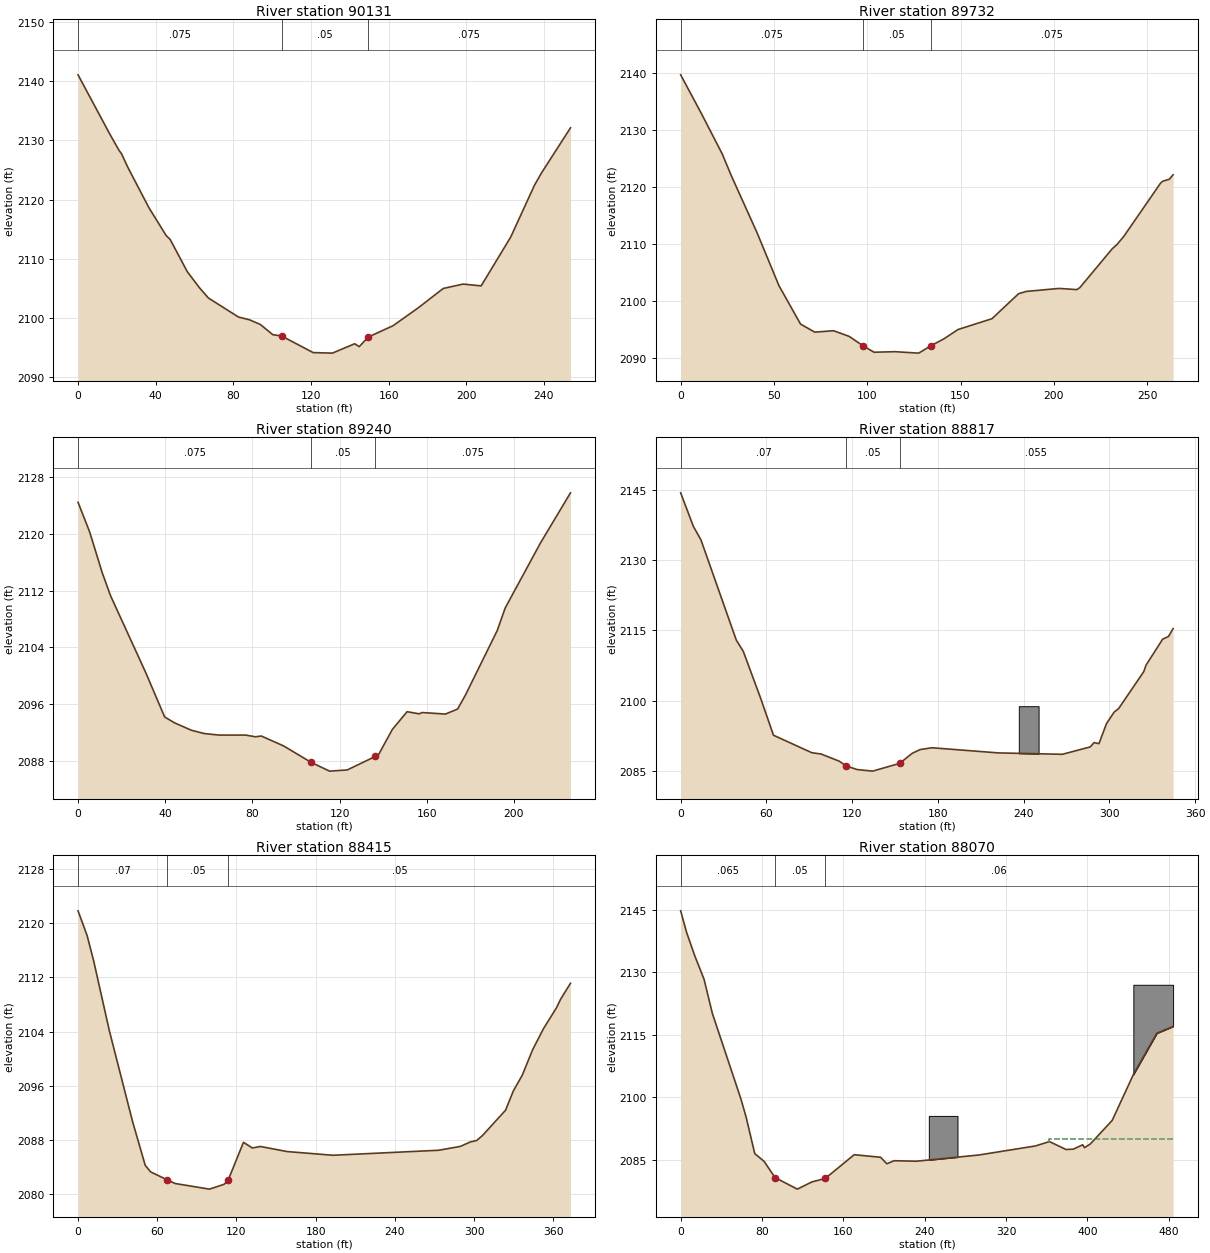
Type RM Length L Ch R = 1 ,90131   ,411.69,398.77,391.24
BEGIN DESCRIPTION:
90053.09
END DESCRIPTION:
XS GIS Cut Line= 4
  921428.1612184  805882.3070898  921493.7862949  805963.5569894
   921546.911308  806013.5572428  921598.4734292  806069.8070157
#Sta/Elev= 30
       0 2141.06   16.69 2130.87   21.01 2128.38   22.52 2127.67   25.43  2125.6
   36.48 2118.66   45.39 2113.95   47.45 2113.29    56.3 2107.84   62.56 2105.13
   67.12 2103.41   82.66 2100.19   88.31 2099.73   93.95 2098.93  100.35 2097.21
  104.83    2097  121.12 2094.19  131.04  2094.1  142.51 2095.68  144.88  2095.2
  149.56 2096.82  162.31 2098.73  175.31 2101.75  188.14 2105.01  198.38 2105.75
  207.69 2105.45  222.93  2113.7  235.12 2122.41  238.67 2124.45   253.7 2132.12
#Mann= 3 , 0 , 0
       0    .075       0  104.83     .05       0  149.56    .075       0
Bank Sta=104.83,149.56
Exp/Cntr=0.3,0.1

Type RM Length L Ch R = 1 ,89732   ,498.68,491.9,463.62
BEGIN DESCRIPTION:
89654.32
END DESCRIPTION:
XS GIS Cut Line= 6
   921173.473324  806219.8067516  921232.8488809  806260.4327255
   921268.786179  806293.2442396  921301.5987172  806330.7444296
   921342.223667  806358.8693161  921382.8486168  806376.0570312
#Sta/Elev= 30
       0 2139.69   11.28  2132.8   22.26 2125.83    27.2 2121.96   40.88 2112.05
   52.66 2102.73   64.27 2095.97    71.9 2094.56   81.96 2094.81   90.29 2093.82
    97.92092.135  103.67 2091.04  115.04 2091.13   127.6 2090.88  133.97 2092.14
  141.14 2093.39  148.66 2095.02  166.88 2096.92  181.13  2101.3  185.22  2101.7
  202.84 2102.23  212.39 2102.02     214 2102.38  231.32 2109.18  233.86 2109.92
  237.48 2111.33  257.16 2120.66  258.31 2121.02  261.94 2121.38  263.96 2122.16
#Mann= 3 , 0 , 0
       0    .075       0    97.9     .05       0  133.97    .075       0
Bank Sta=97.9,133.97
Exp/Cntr=0.3,0.1

Type RM Length L Ch R = 1 ,89240   ,464.19,423.04,394.43
BEGIN DESCRIPTION:
89162.41
END DESCRIPTION:
XS GIS Cut Line= 4
  920907.8482583  806632.3067934  920950.0361001  806674.4946352
  921025.0364801  806711.9948252  921098.4739682  806749.4950152
#Sta/Elev= 30
       0 2124.42    5.29 2120.29   11.11  2114.5   14.94 2111.26   31.05 2100.47
   39.75 2094.22    44.3 2093.39   52.03 2092.35   57.88 2091.89   64.66 2091.67
    76.9 2091.67   81.42 2091.43   84.11 2091.54   94.37 2090.14  106.96 2087.83
  115.42  2086.6  123.49 2086.76  136.44 2088.67  137.92 2088.93  144.24 2092.47
  150.99 2094.96  156.56 2094.66  157.88 2094.84   168.6 2094.63  174.16 2095.33
  177.72 2097.27  192.35 2106.37  196.03 2109.56  212.15 2118.67  225.97 2125.75
#Mann= 3 , 0 , 0
       0    .075       0  106.96     .05       0  136.44    .075       0
Bank Sta=106.96,136.44
Exp/Cntr=0.3,0.1

Type RM Length L Ch R = 1 ,88817   ,399.02,402.42,378.9
BEGIN DESCRIPTION:
88739.37
END DESCRIPTION:
XS GIS Cut Line= 6
  920648.4737364  807041.6820754  920723.4730922  807047.9326191
  920782.8486491  807060.4326825  920818.7859472  807077.6193734
  920867.2233085  807102.6195001  920981.2857464  807110.4319117
#Sta/Elev= 30
       0 2144.42    8.86 2137.26   14.22 2134.34   38.93 2112.93   43.84  2110.5
   55.79 2100.65   64.95 2092.58   91.76 2088.84   98.35 2088.55  111.03 2087.02
  115.68 2086.03  123.44 2085.24  134.37  2084.9  153.27 2086.56  161.98  2088.7
  167.56 2089.51  175.83  2089.9  222.12  2088.8  267.14  2088.5  286.62 2090.08
  289.32    2091  292.72 2090.78  298.02 2095.08  303.44 2097.56  306.43 2098.25
  324.08 2106.18  325.68 2107.57  337.29 2113.12  341.42 2113.71  344.61 2115.38
#Mann= 3 , 0 , 0
       0     .07       0  115.68     .05       0  153.27    .055       0
#Block Obstruct= 1 ,-1
  236.61  250.482098.786
Bank Sta=115.68,153.27
Exp/Cntr=0.3,0.1

Type RM Length L Ch R = 1 ,88415   ,354.89,344.6,394.88
BEGIN DESCRIPTION:
88336.94
END DESCRIPTION:
XS GIS Cut Line= 6
  920579.7239001  807415.1200594  920625.0365017  807435.4325343
  920682.8481424  807447.9325976  920771.9114778  807454.1821172
  920878.1615041  807476.0574841  920939.0989288  807502.6194785
#Sta/Elev= 30
       0 2121.84    6.86  2118.2   11.94 2114.37   23.69 2104.16   41.28 2090.74
    50.9 2084.25   55.05 2083.28   67.68  2082.1   73.52 2081.57   99.57 2080.74
  110.64 2081.45  113.75 2082.08  125.32 2087.65  132.08 2086.82  138.13 2087.04
  158.28 2086.29  193.09 2085.74  273.18 2086.48  289.64 2087.05  297.23 2087.71
   301.9 2087.91  306.26 2088.63  323.84 2092.39  329.78 2095.25  336.55 2097.58
  344.39 2101.34  352.69 2104.47  362.34 2107.49  365.64 2108.81  373.04 2111.14
#Mann= 3 , 0 , 0
       0     .07       0   67.68     .05       0  113.75     .05       0
Bank Sta=67.68,113.75
Exp/Cntr=0.3,0.1

Type RM Length L Ch R = 1 ,88070   ,329.38,384.71,461.46
BEGIN DESCRIPTION:
87992.35
END DESCRIPTION:
XS GIS Cut Line= 6
  920434.4107918  807760.4321327  920639.0984328  807763.5568925
  920717.2235726  807786.9951514  920770.3485858  807815.1200378
  920810.9735356  807854.1820956  920823.4735989  807933.8701274
#Sta/Elev= 30
       0 2144.71     5.8 2139.57   13.97 2133.86   22.97 2128.33   31.18 2120.11
   59.32 2099.55   64.39 2095.23   72.86  2086.5   82.03 2084.66   92.74 2080.77
  114.71 2077.99  128.97 2079.71  142.19 2080.55  170.62 2086.24  196.54 2085.63
  202.75 2084.07  209.91  2084.8  231.69 2084.68  292.92 2086.16   348.8 2088.34
  362.61 2089.39  378.92 2087.49  386.07 2087.57  395.25 2088.62  397.15 2087.93
  402.79 2088.81  424.33 2094.47  444.99 2105.38   468.2 2115.36   484.2 2116.99
#Mann= 3 , 0 , 0
       0    .065       0   92.74     .05       0  142.19     .06       0
#XS Ineff= 2 , 0
       0                  362.61       0    2090
Permanent Ineff=
       F       F
#Block Obstruct= 2 ,-1
     244   272.22095.548   445.1   484.22126.986
Bank Sta=92.74,142.19
Exp/Cntr=0.3,0.1

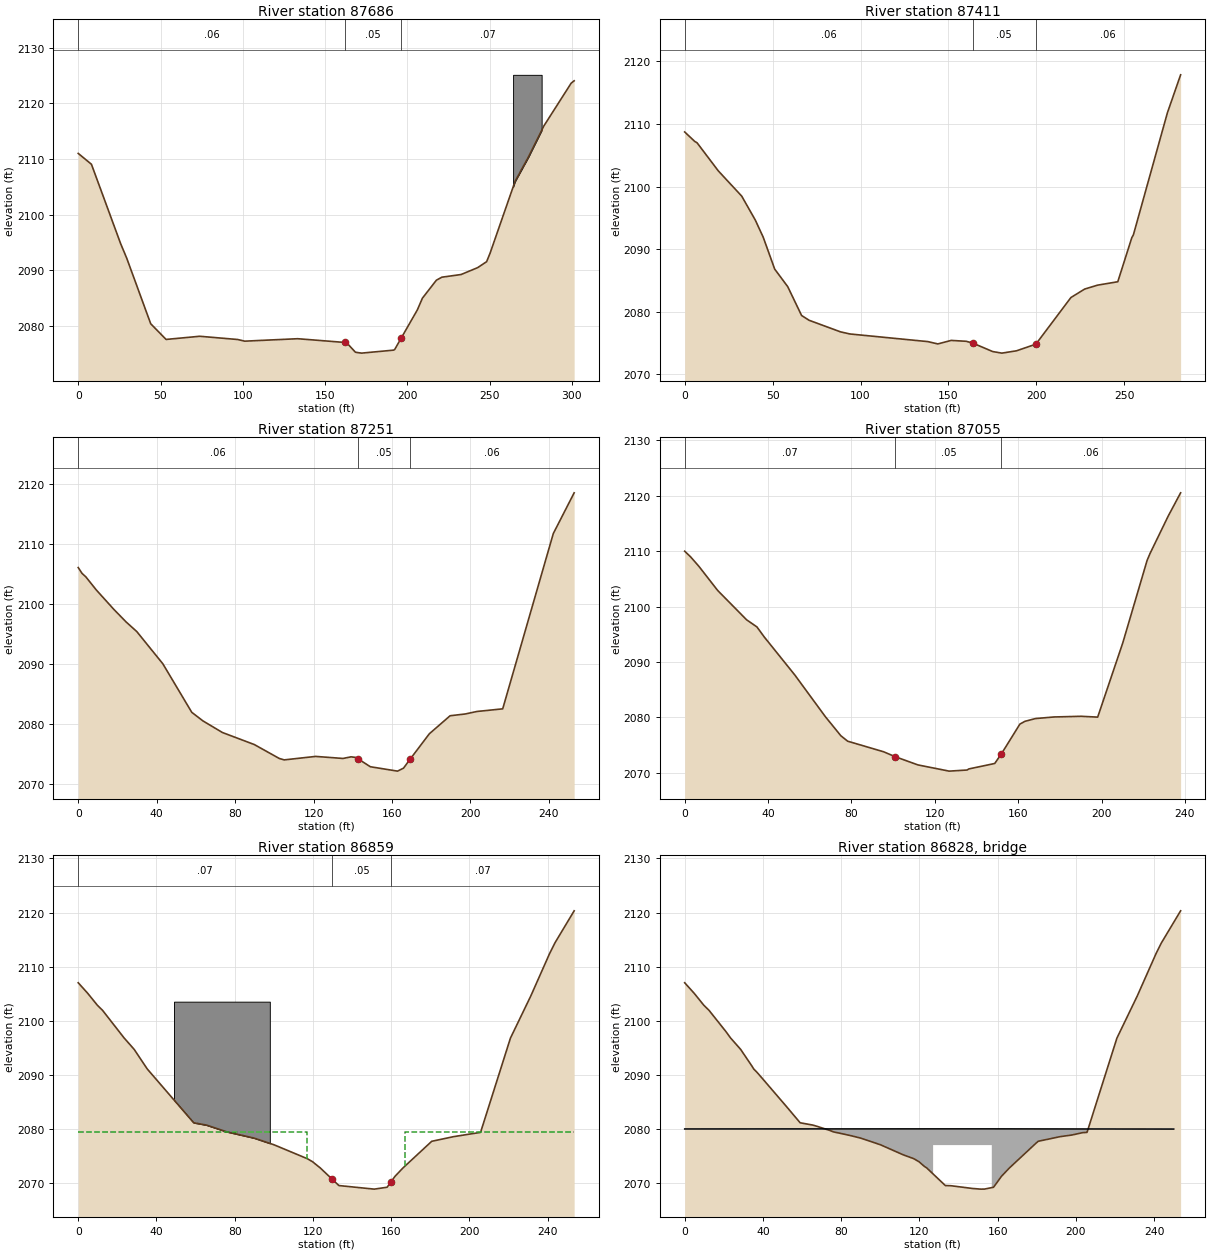
Type RM Length L Ch R = 1 ,87686   ,218.01,274.21,304.67
BEGIN DESCRIPTION:
87607.64
END DESCRIPTION:
XS GIS Cut Line= 6
  920314.0988344  807990.1199004  920370.3486073  808054.1820849
  920414.0983169  808102.6194462  920459.4109185  808147.9320478
  920492.2234567  808180.7445861  920515.6606914  808213.5571243
#Sta/Elev= 30
       0 2110.99    8.03 2109.04   25.82 2094.74   29.51 2092.13   44.05 2080.37
    53.4 2077.55   73.84 2078.12   96.83 2077.54  101.18 2077.24  133.34 2077.68
  161.98 2077.01  163.12 2076.95  168.45 2075.25  172.14 2075.09  191.68 2075.63
  192.33 2075.76   196.22077.764  206.04 2082.85  209.12 2084.96  217.63  2088.2
  220.97 2088.74  232.63 2089.22  242.72 2090.46  248.15 2091.53  250.28 2093.08
  265.42 2105.95   273.6 2110.37  282.92 2115.92  299.51 2123.61  301.33 2124.04
#Mann= 3 , 0 , 0
       0     .06       0  161.98     .05       0   196.2     .07       0
#Block Obstruct= 1 ,-1
  264.23  281.572125.114
Bank Sta=161.98,196.2
Exp/Cntr=0.3,0.1

Type RM Length L Ch R = 1 ,87411   ,117.09,160.6,216.57
BEGIN DESCRIPTION:
87333.42
END DESCRIPTION:
XS GIS Cut Line= 6
  920164.0980743  808115.1195096   920190.661093  808193.2446494
  920204.7240483   808240.120143  920218.7859795  808285.4327445
  920235.9736946  808333.8701059  920260.9738213  808379.1827075
#Sta/Elev= 30
       0 2108.72    5.75  2107.2    7.04 2106.99    19.1 2102.51   32.44 2098.47
   40.16 2094.65   44.68  2091.9   51.19 2086.82   58.62 2084.01   66.49 2079.41
   70.81 2078.64   88.59  2076.8   93.93 2076.46  138.27 2075.24  143.97 2074.87
  151.57 2075.43  160.12 2075.29  163.76 2075.01  175.19 2073.65   180.4  2073.4
  188.71 2073.77  199.73 2074.83  219.67 2082.28  227.49 2083.63  234.76 2084.25
  246.32  2084.8  254.31 2091.85  255.19 2092.29  274.55 2111.79  282.05 2117.84
#Mann= 3 , 0 , 0
       0     .06       0  163.76     .05       0  199.73     .06       0
Bank Sta=163.76,199.73
Exp/Cntr=0.3,0.1

Type RM Length L Ch R = 1 ,87251   ,157.67,195.4,211.22
BEGIN DESCRIPTION:
87172.82
END DESCRIPTION:
XS GIS Cut Line= 6
  920071.9110034    808146.37018  920067.2233516  808222.9324279
  920065.6614838  808249.4944223   920060.973832  808301.0575677
  920045.3490089  808351.0567968   920025.036534  808391.6817466
#Sta/Elev= 30
       0 2106.11    1.95 2105.14    3.91 2104.55    9.19 2102.39   18.21 2099.13
   24.39 2097.06   29.89 2095.44   43.16 2090.08   57.91    2082   63.62 2080.57
   73.53 2078.64   89.77 2076.64  102.46 2074.33  105.03 2074.08  121.06 2074.66
  134.99 2074.32  139.12 2074.59  141.58 2074.49  142.53 2074.29  148.97 2072.94
  162.82 2072.21  165.86  2072.7  169.14 2074.15  179.05 2078.43  189.64 2081.43
  197.44 2081.73  203.26 2082.14  216.46 2082.58  242.26 2111.77  252.89 2118.55
#Mann= 3 , 0 , 0
       0     .06       0  142.53     .05       0  169.14     .06       0
Bank Sta=142.53,169.14
Exp/Cntr=0.3,0.1

Type RM Length L Ch R = 1 ,87055   ,158.41,196.8,204.05
BEGIN DESCRIPTION:
86977.42
END DESCRIPTION:
XS GIS Cut Line= 6
   919931.286571  808118.2442694  919915.6607237  808161.9950031
   919893.786381  808211.9952565  919867.2233624  808254.1820741
  919845.3490197  808285.4327445  919823.4736528  808329.1824541
#Sta/Elev= 30
       0 2109.99     2.8 2108.99     6.8 2107.27   15.85  2102.9   29.73 2097.61
   34.67 2096.33   38.14 2094.54   52.89 2087.64    67.5 2080.14   74.96 2076.69
    78.2 2075.72   95.46 2073.81  101.03 2072.92  111.91 2071.44   126.9 2070.32
  135.54 2070.52  136.27 2070.71  148.76  2071.7  151.99 2073.45  160.83  2078.8
  163.24  2079.3  168.28  2079.8  177.26 2080.09  190.29 2080.21  198.16 2080.06
  210.19 2093.44  221.87 2108.33  223.28 2109.58  231.99 2116.32  237.95 2120.52
#Mann= 3 , 0 , 0
       0     .07       0  101.03     .05       0  151.99     .06       0
Bank Sta=101.03,151.99
Exp/Cntr=0.5,0.3

Type RM Length L Ch R = 1 ,86859   ,60.07,51.37,41.07
BEGIN DESCRIPTION:
86780.62
END DESCRIPTION:
XS GIS Cut Line= 6
  919825.0365448  808051.0573251  919723.4731461  808121.3700533
  919684.4110882   808163.556871  919668.7862651   808182.307478
  919660.9738536  808208.8694725  919659.4109616  808229.1819474
#Sta/Elev= 30
       0 2107.03    4.84 2105.09    9.78 2102.88   12.46 2101.93   23.47 2096.83
   28.62 2094.72   35.29 2091.11   59.03 2081.17    65.6 2080.74   75.85 2079.51
   89.94 2078.34  100.14  2077.1  117.12 2074.54  119.82 2073.97  123.74 2072.83
  129.89 2070.73  133.26 2069.58  151.32 2068.92  157.91 2069.27  160.02 2070.32
  161.91 2071.27  165.93  2072.8  180.71 2077.75   191.9 2078.61  205.68  2079.4
  220.96 2096.81  231.35 2104.58  240.97 2112.42  243.68 2114.38  253.52 2120.31
#Mann= 3 , 0 , 0
       0     .07       0  129.89     .05       0  160.02     .07       0
#XS Ineff= 2 , 0
       0     117  2079.5     167       0  2079.5
Permanent Ineff=
       F       F
#Block Obstruct= 1 ,-1
   48.98   97.942103.539
Bank Sta=129.89,160.02
Exp/Cntr=0.5,0.3

Type RM Length L Ch R = 3 ,86828   ,,,
Node Photo=H:\PROJ\06-0741\CE\GIS\DATA\FRENCH_BROAD_RIVER\SHAPEFILES\survey_data\photos\FBSTR_1771.JPG
BEGIN DESCRIPTION:
86754  FBSTR_1771
END DESCRIPTION:
Bridge Culvert--1,0,-1,-1, 0
Deck Dist Width WeirC Skew NumUp NumDn MinLoCord MaxHiCord MaxSubmerge Is_Ogee
19,9,3,0, 7, 7, , , 0.95, 0, 1,1,,
       0     127     127     142     157     157     250
 2080.03 2080.05 2080.05 2080.05 2080.05 2080.05 2080.01
                 2077.05 2077.05 2077.05
       0     127     127     142     157     157     250
 2080.03 2080.05 2080.05 2080.05 2080.05 2080.05 2080.01
                 2077.05 2077.05 2077.05
BR Coef=-1 , 0 , 0 ,, 0 ,,,0.8,0,,0,
WSPro=,,,, 1 ,,,, 0 ,,,, 0 ,,,,-1 ,-1 ,-1 , 0 , 0 , 0 , 0 , 0
BR U #Sta/Elev= 58
       0 2107.03    4.84 2105.09    9.78 2102.88   12.46 2101.93   21.09 2098.01
   23.47 2096.83   28.62 2094.72   34.37 2091.65   35.29 2091.11   36.95  2090.5
   39.63 2089.39   52.11 2084.14   59.03 2081.17    65.6 2080.74    68.2 2080.46
   68.48 2080.42   74.35 2079.74   75.85 2079.51   76.35 2079.47   77.19  2079.4
   78.93 2079.27   85.07 2078.78   89.94 2078.34   94.53 2077.79  100.14  2077.1
  111.67 2075.26  117.12 2074.54  119.82 2073.97  122.51 2073.12  123.53 2072.88
  123.74 2072.83  129.89 2070.73  133.26 2069.58  135.93 2069.55  136.05 2069.55
  146.95 2069.05  151.32 2068.92   153.3 2068.93  157.91 2069.27  158.95 2069.79
  160.02 2070.32  161.91 2071.27  165.93  2072.8  179.27 2077.29  180.71 2077.75
  181.05 2077.78  181.44 2077.81  189.08 2078.39   191.9 2078.61  197.95 2078.91
  203.32 2079.34  205.46 2079.39  205.68  2079.4  220.96 2096.81  231.35 2104.58
  240.97 2112.42  243.68 2114.38  253.52 2120.31
BR U #Mann= 3
       0     .07  129.89     .05  160.02     .07
BC Design=,, 0 ,, 0 ,,,,,,

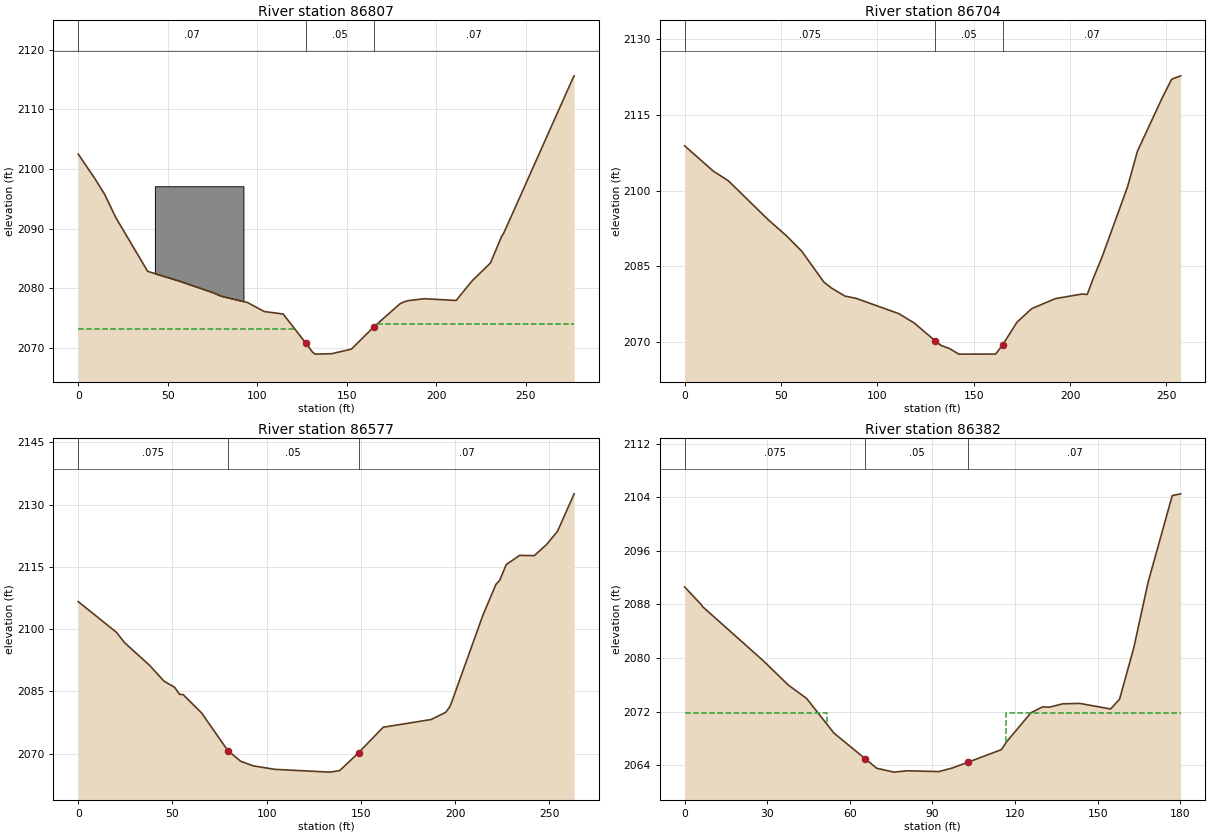
Type RM Length L Ch R = 1 ,86807   ,45.42,102.9,172.12
BEGIN DESCRIPTION:
86729.25
END DESCRIPTION:
XS GIS Cut Line= 6
   919782.848703  808011.9942431  919734.4113416  808040.1201537
  919698.4740436   808069.806908  919656.2862018  808121.3700533
  919629.7231831  808177.6198263  919629.7231831  808222.9324279
#Sta/Elev= 30
       0 2102.51    9.37 2098.37   14.76 2095.76    20.6 2092.11   22.18 2091.25
   38.81 2082.84   56.01 2081.26   74.88 2079.32   79.85 2078.69   94.47 2077.63
  103.94  2076.1  114.46 2075.69  126.982070.872  130.88  2069.3  132.37 2068.96
   141.6 2069.03  152.62  2069.8  165.05 2073.51  179.78 2077.41  181.91 2077.71
  184.29 2077.93  193.29 2078.25  211.12 2077.96  219.91 2081.21  230.26 2084.24
  236.49 2088.68   237.7 2089.27  241.21  2091.6   276.2 2115.15  277.03 2115.63
#Mann= 3 , 0 , 0
       0     .07       0  126.98     .05       0  165.05     .07       0
#XS Ineff= 2 , 0
       0  121.06  2073.2     167       0 2074.06
Permanent Ineff=
       F       F
#Block Obstruct= 1 ,-1
   42.83   92.28 2097.11
Bank Sta=126.98,165.05
Exp/Cntr=0.5,0.3

Type RM Length L Ch R = 1 ,86704   ,95.2,127.54,138.66
BEGIN DESCRIPTION:
86626.35
END DESCRIPTION:
XS GIS Cut Line= 6
   919782.848703  807965.1197737  919718.7865185    807996.36942
   919687.535848  808001.0570717  919664.0986133  808005.7447235
  919610.9736002  808008.8694833  919534.4113524  808019.8076788
#Sta/Elev= 30
       0 2108.85   14.98 2103.81   22.68 2101.93   43.29 2094.24   52.81 2091.04
   60.62 2088.04   72.25 2081.86   76.18 2080.69   83.13  2079.1   89.04 2078.64
   111.1 2075.62  119.14 2073.76     130 2070.22  132.93 2069.35  137.45  2068.7
  142.25  2067.6  161.34 2067.61  165.04 2069.46  172.46 2073.94  180.06 2076.61
  192.33 2078.59  205.93 2079.49  208.91 2079.44     212  2082.6  216.42 2086.67
  229.82 2100.76  234.96 2107.81  247.61 2118.21  252.68 2122.04  257.34 2122.72
#Mann= 3 , 0 , 0
       0    .075       0     130     .05       0  165.04     .07       0
Bank Sta=130,165.04
Exp/Cntr=0.3,0.1

Type RM Length L Ch R = 1 ,86577   ,201.4,194.44,203.14
BEGIN DESCRIPTION:
86498.81
END DESCRIPTION:
XS GIS Cut Line= 6
  919768.7857476   807905.745241  919720.3483863  807899.4946972
  919685.9739802  807885.4317419  919643.7861384  807879.1822223
  919603.1611886  807879.1822223  919509.4112257  807874.4945705
#Sta/Elev= 30
       0 2106.63   20.35 2099.22   24.44 2096.82   37.96 2091.25   45.44 2087.52
   51.12 2086.02   53.79  2084.3   55.68 2084.25   65.48 2079.83    79.4 2070.77
    86.3 2068.18   92.87 2067.09  104.36 2066.25  133.46 2065.58  138.72 2065.93
  148.792070.257  161.84 2076.39  187.24 2078.24  195.04 2079.98  197.19 2081.33
   198.5 2082.82  214.74 2103.33  221.64 2110.76  223.61 2111.71  227.17 2115.56
  234.23 2117.76  242.05 2117.71  248.46 2120.34  254.37 2123.58  263.18 2132.58
#Mann= 3 , 0 , 0
       0    .075       0    79.4     .05       0  148.79     .07       0
Bank Sta=79.4,148.79
Exp/Cntr=0.5,0.3

Type RM Length L Ch R = 1 ,86382   ,62.92,56.56,52.96
BEGIN DESCRIPTION:
86304.37
END DESCRIPTION:
XS GIS Cut Line= 4
  919792.2240065  807707.3071196  919715.6607345  807694.8070562
  919670.3481329  807688.5575366    919614.09836  807680.7451251
#Sta/Elev= 27
       0 2090.61    5.99 2087.98    6.47 2087.68   28.56 2079.58   37.61 2075.96
   44.26 2073.96   54.22 2068.77   65.592064.932   69.69 2063.53   75.93 2062.94
   80.89 2063.14   92.33 2063.02   97.23 2063.56  103.07 2064.45  115.02  2066.3
     117 2067.52  125.75 2071.81  129.98 2072.69  132.45 2072.65   137.3 2073.15
  143.46 2073.21  154.69 2072.38  157.95 2073.85  163.12 2081.56  168.28 2091.28
  177.07 2104.27  180.11 2104.53
#Mann= 3 , 0 , 0
       0    .075       0   65.59     .05       0  103.07     .07       0
#XS Ineff= 2 , 0
       0   51.83 2071.75  116.83       0 2071.75
Permanent Ineff=
       F       F
Bank Sta=65.59,103.07
Exp/Cntr=0.5,0.3