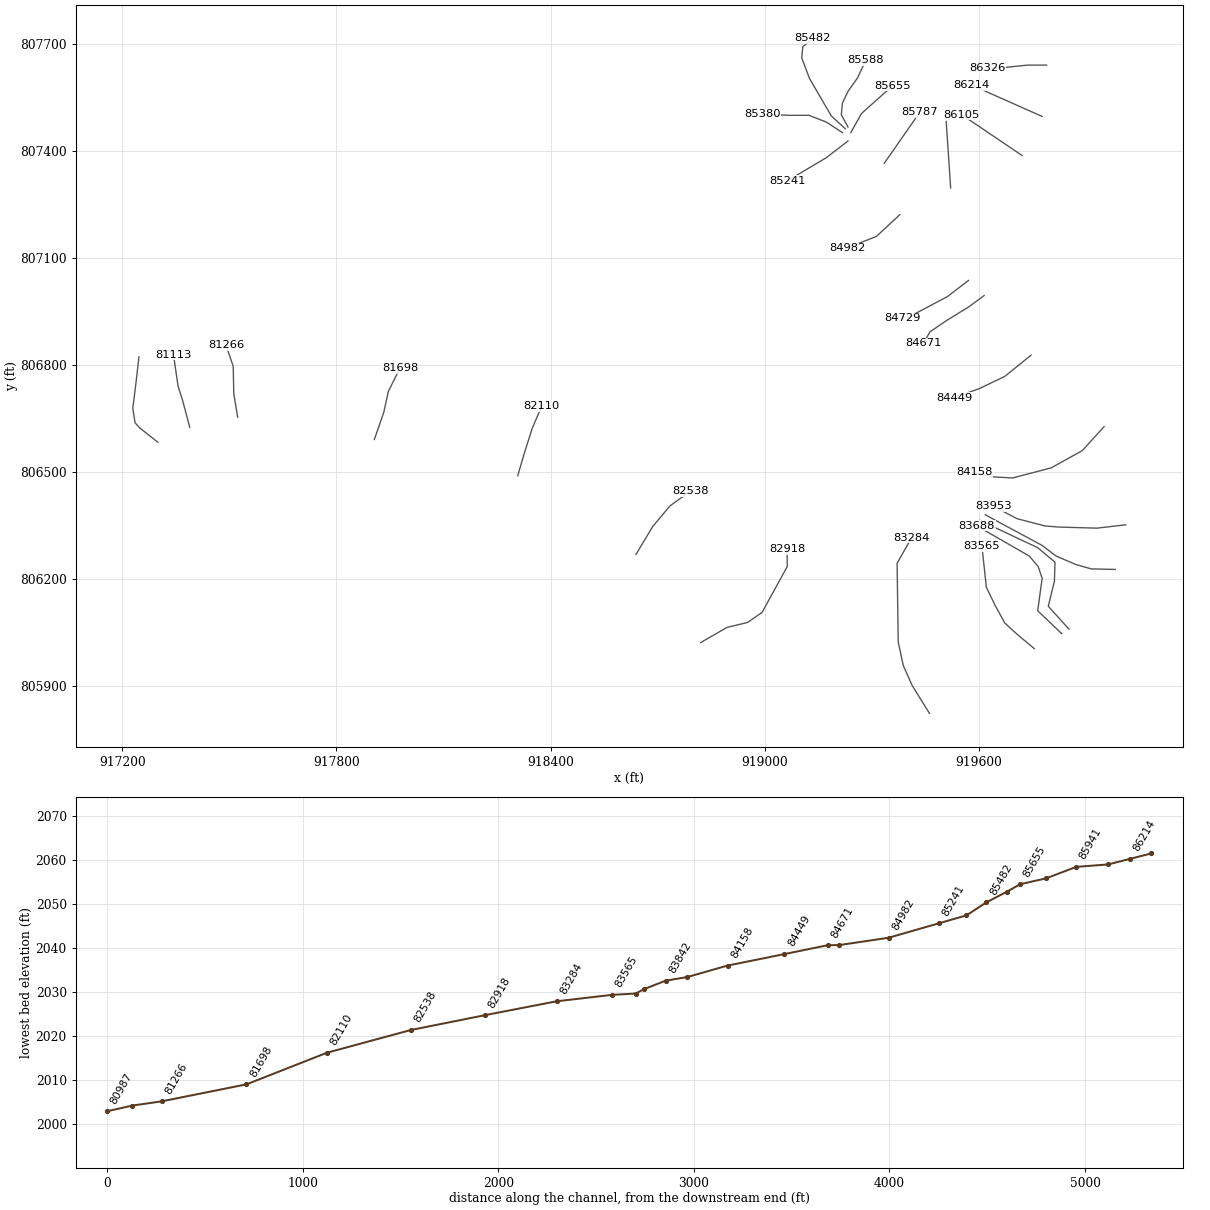
HEC-RAS study lds_big_laurel_crk.prj: lds_big_laurel_crk

--- lds_big_laurel_crk.g20 (geometry) --- (continued)

Type RM Length L Ch R = 3 ,86351   ,,,
BEGIN DESCRIPTION:
86274  BFSTR_5036
END DESCRIPTION:
Bridge Culvert--1,0,-1,-1, 0
Deck Dist Width WeirC Skew NumUp NumDn MinLoCord MaxHiCord MaxSubmerge Is_Ogee
23,12,2.6,0, 6, 6, , , 0.95, 0, 1,1,,
       0   61.83   61.83  106.83  106.83  129.98
 2072.26 2072.26 2072.26 2072.26 2072.26 2072.69
                 2070.76 2070.76
       0      50      50      95      95  124.53
 2072.76 2072.26 2072.26 2072.26 2072.26 2071.27
                 2070.76 2070.76
BR Coef=-1 , 0 , 0 ,, 0 ,,,0.8,0,,0,
WSPro=,,,, 1 ,,,, 0 ,,,, 0 ,,,,-1 ,-1 ,-1 , 0 , 0 , 0 , 0 , 0
BC Design=,, 0 ,, 0 ,,,,,,

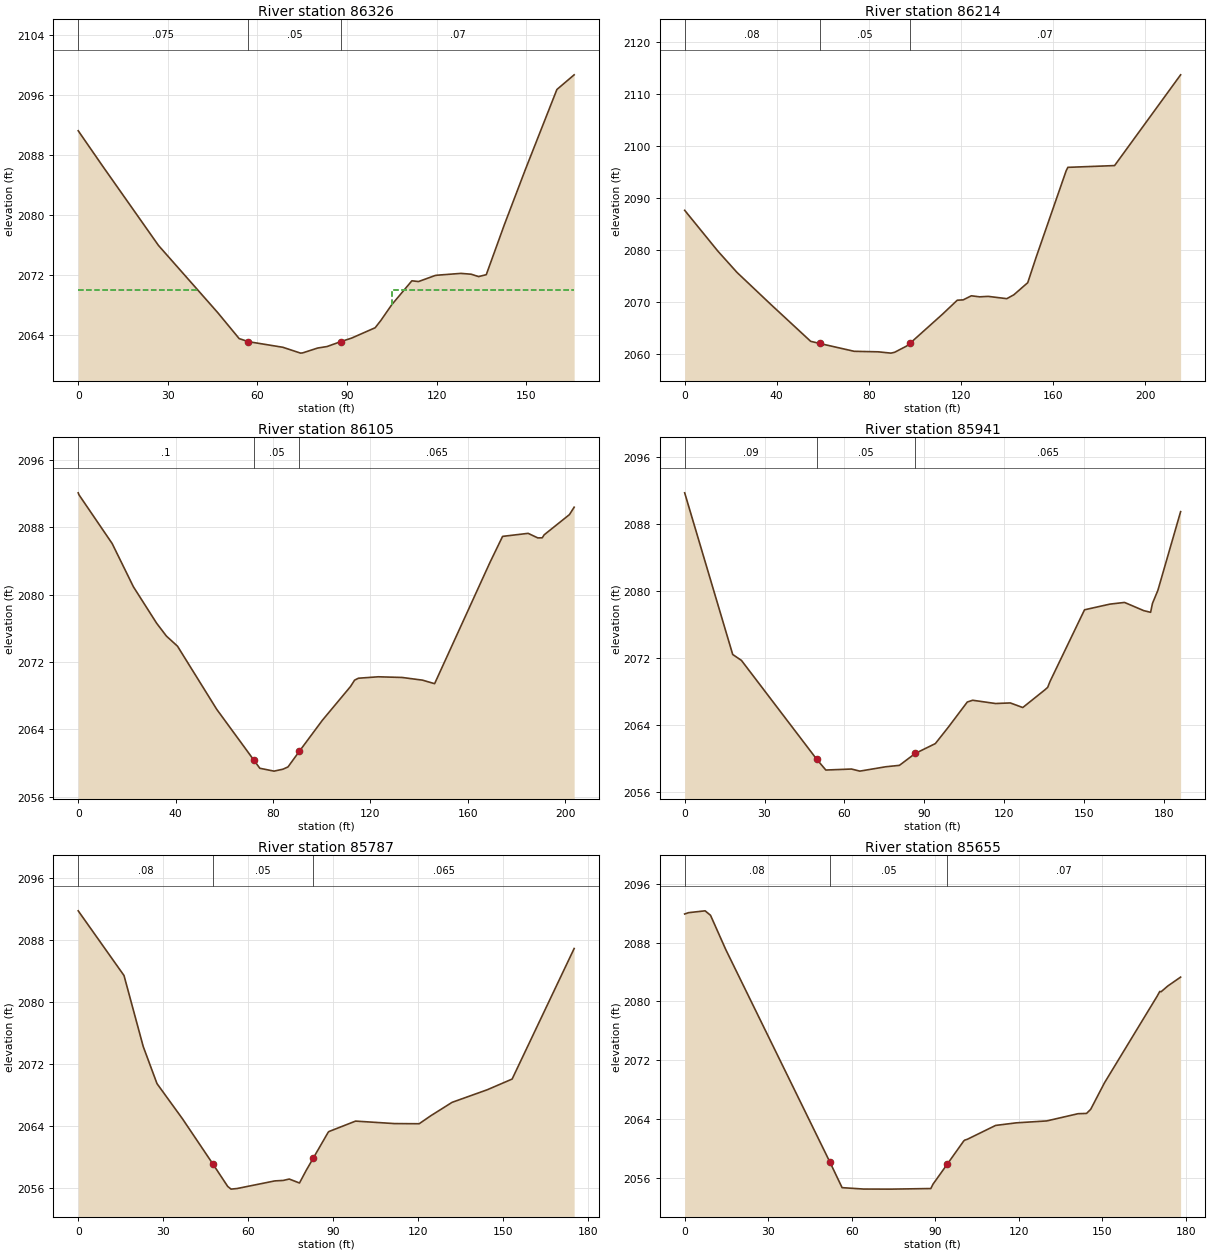
Type RM Length L Ch R = 1 ,86326   ,135.07,111.36,78
BEGIN DESCRIPTION:
86247.81
END DESCRIPTION:
XS GIS Cut Line= 4
  919789.0982226  807640.1201753  919735.9732094  807640.1201753
  919675.0357847  807633.8696315  919623.4736635  807630.7448717
#Sta/Elev= 28
       0 2091.22    8.18  2086.5   26.88  2075.9   46.69 2066.94   53.89 2063.46
   56.99 2063.05   68.53  2062.3   74.44 2061.52   75.14 2061.55   80.17  2062.2
    83.3  2062.4   87.822063.043   91.55 2063.53   99.42 2064.91  101.32 2065.88
  104.98 2067.99  111.71 2071.18  113.93 2071.08  119.59  2071.9  120.58 2071.94
   128.1 2072.17  131.57 2072.06  134.06 2071.74  136.62    2072  142.67 2078.67
  149.65 2085.98  160.26 2096.73  166.04 2098.69
#Mann= 3 , 0 , 0
       0    .075       0   56.99     .05       0   87.82     .07       0
#XS Ineff= 2 , 0
       0      40    2070     105       0    2070
Permanent Ineff=
       F       F
Bank Sta=56.99,87.82
Exp/Cntr=0.5,0.3

Type RM Length L Ch R = 1 ,86214   ,118.5,109.14,99.45
BEGIN DESCRIPTION:
86136.45
END DESCRIPTION:
XS GIS Cut Line= 2
  919776.5981592   807496.369959  919579.7239539  807583.8693782
#Sta/Elev= 26
       0 2087.69    14.4 2079.86   22.71 2075.77   37.31 2069.66   54.72 2062.53
    58.6 2062.12   73.64 2060.61   84.09 2060.51   89.58 2060.26    91.2 2060.42
   96.46 2061.63   97.88 2062.14  112.03 2067.75  118.41 2070.42  120.99 2070.49
  124.53 2071.27  128.15 2071.07  131.81 2071.16  139.94 2070.72  143.01 2071.47
  149.03 2073.79  152.68 2078.68   165.7 2095.26  166.46 2095.94  186.75 2096.28
  215.44 2113.71
#Mann= 3 , 0 , 0
       0     .08       0    58.6     .05       0   97.88     .07       0
Bank Sta=58.6,97.88
Exp/Cntr=0.3,0.1

Type RM Length L Ch R = 1 ,86105   ,205.76,163.84,86.92
BEGIN DESCRIPTION:
86027.32
END DESCRIPTION:
XS GIS Cut Line= 2
  919720.3483863  807386.9951729  919551.5990675  807501.0576107
#Sta/Elev= 30
       0 2092.12      .3 2091.89   13.94 2086.09   22.68 2080.94   32.21 2076.61
   36.23 2075.08   40.78 2073.88   56.89 2066.37   72.022060.378   74.59 2059.36
   80.41 2059.02   84.11 2059.25   86.16 2059.52   90.85 2061.39  100.25 2065.06
  111.83 2069.08   113.5 2069.84   115.1 2070.07  123.26 2070.24  133.04 2070.16
  141.41 2069.84  146.37 2069.42  169.07 2083.82  174.29 2086.94  184.78  2087.3
  188.74 2086.76  190.58 2086.77  191.38 2087.13  201.75 2089.53  203.68 2090.41
#Mann= 3 , 0 , 0
       0      .1       0   72.02     .05       0   90.85    .065       0
Bank Sta=72.02,90.85
Exp/Cntr=0.3,0.1

Type RM Length L Ch R = 1 ,85941   ,181.78,154.53,104.61
BEGIN DESCRIPTION:
85863.48
END DESCRIPTION:
XS GIS Cut Line= 2
   919520.348397  807296.3699697  919507.8483337  807482.3070036
#Sta/Elev= 28
       0 2091.72   18.05  2072.4   21.34 2071.69   49.572059.899   53.04 2058.59
    62.7 2058.71   65.83 2058.46   75.52 2058.98   80.69 2059.15   86.62 2060.57
   94.19 2061.75   99.07 2063.71   106.2 2066.72  108.23 2066.93  116.81 2066.54
  122.35 2066.61  127.05 2066.06   135.3 2068.16   136.4 2068.47  137.29 2069.18
  150.25 2077.74  159.81 2078.42  165.29 2078.62  172.51 2077.64  175.08 2077.44
   175.8 2078.52  177.81 2080.06  186.36 2089.47
#Mann= 3 , 0 , 0
       0     .09       0   49.57     .05       0   86.62    .065       0
Bank Sta=49.57,86.62
Exp/Cntr=0.3,0.1

Type RM Length L Ch R = 1 ,85787   ,131.16,132.22,113.82
BEGIN DESCRIPTION:
85708.95
END DESCRIPTION:
XS GIS Cut Line= 2
  919334.4113631   807365.119806  919434.4108457  807508.8700223
#Sta/Elev= 25
       0 2091.73   16.17 2083.39   22.96 2074.23   27.82 2069.45   36.81 2064.92
   47.672059.028   52.78  2056.2   53.97 2055.85   56.12 2055.93   69.42 2056.91
   72.39 2056.97   74.52 2057.15   78.13 2056.64   80.49 2058.26   82.952059.818
   88.26 2063.18   88.57 2063.28   97.93 2064.62  111.67  2064.3  120.39 2064.28
  124.49 2065.31  132.02 2067.04  144.42 2068.66  153.21 2070.04  175.11 2086.87
#Mann= 3 , 0 , 0
       0     .08       0   47.67     .05       0   82.95    .065       0
Bank Sta=47.67,82.95
Exp/Cntr=0.3,0.1

Type RM Length L Ch R = 1 ,85655   ,44.51,67.01,93.19
BEGIN DESCRIPTION:
85576.73
END DESCRIPTION:
XS GIS Cut Line= 4
  919240.6614002  807451.0573574  919270.3481545  807504.1823705
  919287.5358696  807519.8071937  919357.8485978  807582.3075104
#Sta/Elev= 27
       0 2091.88     1.4 2092.06    7.34 2092.31    9.29  2091.7   14.75 2087.06
   52.16  2058.2   56.55 2054.72   64.26 2054.53   74.11 2054.52   88.42  2054.6
   89.22  2055.2   94.37 2057.93  100.21 2061.04  100.63 2061.18   101.5 2061.28
   111.7 2063.17  119.13 2063.52  130.05 2063.78  141.29 2064.76  144.37  2064.8
  145.86 2065.36   150.8 2068.95  169.76 2080.74  170.67 2081.36  171.14 2081.32
  173.58 2082.11  178.16 2083.31
#Mann= 3 , 0 , 0
       0     .08       0   52.16     .05       0   94.37     .07       0
Bank Sta=52.16,94.37
Exp/Cntr=0.3,0.1

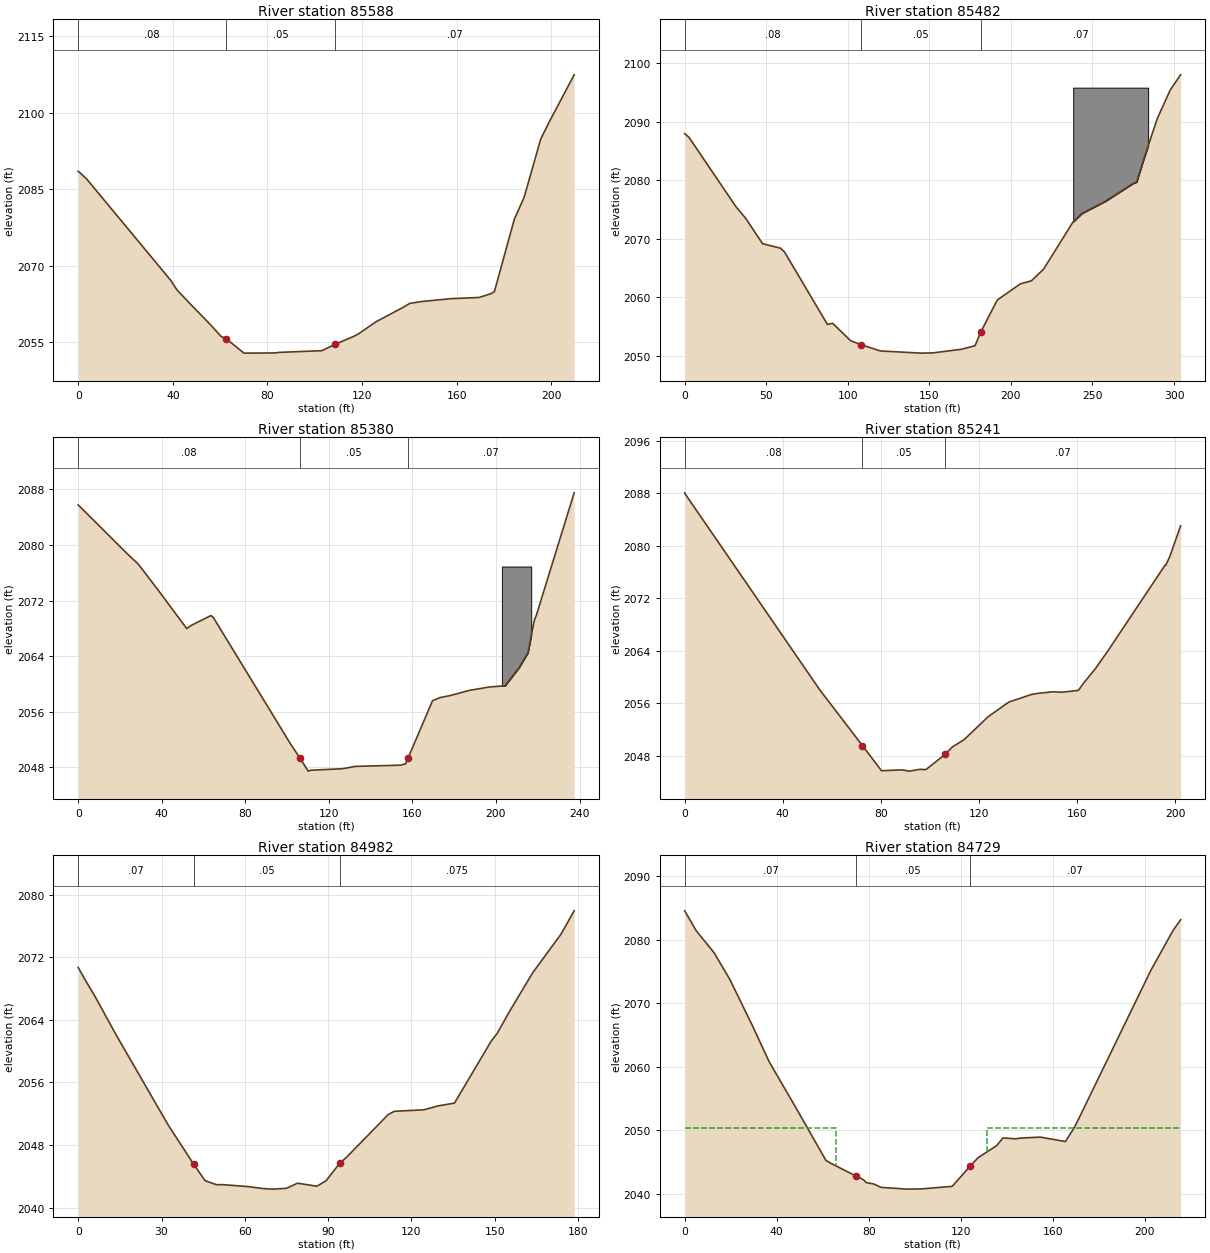
Type RM Length L Ch R = 1 ,85588   ,29.61,105.23,179.69
BEGIN DESCRIPTION:
85509.72
END DESCRIPTION:
XS GIS Cut Line= 6
  919232.8489886  807466.6821805  919214.0983815  807501.0576107
  919217.2231413   807533.870149  919232.8489886  807566.6826872
  919259.4109831  807604.1818531  919282.8482178  807654.1821064
#Sta/Elev= 28
       0 2088.53    3.55 2087.02   39.16 2067.09   41.62 2065.33   46.07 2063.12
   56.02 2058.36   60.39 2056.12   62.47 2055.69   70.08 2052.84    83.3 2052.88
    85.1 2052.99     103 2053.32  108.46 2054.54  116.32  2056.1  118.35 2056.58
  125.92    2059  137.39 2061.83  140.18  2062.6  145.13 2062.96  157.37 2063.52
  169.47 2063.76   174.4 2064.49  175.93 2064.91  184.33 2079.07  188.52 2083.45
   195.5 2094.82  198.74 2097.87  209.64 2107.44
#Mann= 3 , 0 , 0
       0     .08       0   62.47     .05       0  108.46     .07       0
Bank Sta=62.47,108.46
Exp/Cntr=0.3,0.1

Type RM Length L Ch R = 1 ,85482   ,23.94,102.2,202.48
BEGIN DESCRIPTION:
85404.5
END DESCRIPTION:
XS GIS Cut Line= 6
  919225.0365771  807461.9945287  919185.9734951  807497.9318268
  919125.0360704  807602.6199853  919103.1607035  807660.4326502
  919106.2864874  807691.6822964  919134.4113739  807715.1195311
#Sta/Elev= 30
       0 2087.99    2.66 2087.35   31.53 2075.45   37.44 2073.48   47.78 2069.14
   58.68 2068.39   61.17 2067.75    87.5 2055.33   90.69 2055.52  101.77 2052.53
  108.16 2051.85  120.02 2050.78   144.8 2050.41  152.18 2050.45  169.73 2051.07
     178 2051.68  181.68 2054.11  191.64  2059.5   205.8 2062.27  212.56 2062.79
  219.97 2064.76  237.99 2072.82   243.5 2074.31  257.95 2076.41  274.94 2079.46
  277.08 2079.69  281.37 2083.53  289.72 2090.56   297.8 2095.53  304.05 2098.06
#Mann= 3 , 0 , 0
       0     .08       0  108.16     .05       0  181.68     .07       0
#Block Obstruct= 1 ,-1
   238.2  284.142095.866
Bank Sta=108.16,181.68
Exp/Cntr=0.3,0.1

Type RM Length L Ch R = 1 ,85380   ,82.67,139.18,192.38
BEGIN DESCRIPTION:
85302.30
END DESCRIPTION:
XS GIS Cut Line= 5
  919217.2231413  807451.0573574  919171.9115639  807480.7451358
  919123.4731784  807499.4947188  919067.2234054  807499.4947188
  918992.2240496  807502.6194785
#Sta/Elev= 29
       0 2085.78   23.68 2078.69   28.72 2077.27   38.27 2073.52   51.97 2067.97
   54.17 2068.44   63.53 2069.85   64.75 2069.54  101.54 2051.42  106.11 2049.34
  110.13 2047.45  111.41 2047.58   126.7  2047.8  132.63 2048.13  154.32 2048.31
  156.76  2048.5  157.92 2049.33  169.63 2057.59  173.21 2058.04  177.95 2058.32
   187.2 2059.07  196.79 2059.56  204.36 2059.74  211.08 2062.35  215.32  2064.5
  218.03 2068.71  218.56 2069.35   219.3 2069.85  237.43 2087.52
#Mann= 3 , 0 , 0
       0     .08       0  106.11     .05       0  157.92     .07       0
#Block Obstruct= 1 ,-1
  202.83  216.872076.908
Bank Sta=106.11,157.92
Exp/Cntr=0.3,0.1

Type RM Length L Ch R = 1 ,85241   ,254.22,259.37,256.44
BEGIN DESCRIPTION:
85163.11
END DESCRIPTION:
XS GIS Cut Line= 3
  919232.8489886  807427.6201227  919171.9115639  807380.7446291
  919064.0986457  807316.6824446
#Sta/Elev= 26
       0 2088.04     .06 2087.95   55.17 2058.01   72.48 2049.57   80.29 2045.73
   88.61 2045.86   91.73 2045.67   95.98 2045.95   98.39  2045.9   106.2 2048.21
  109.11 2049.33  114.04 2050.48  123.71 2053.93  132.19 2056.18  141.37 2057.33
  143.71 2057.49  150.08 2057.75   153.8 2057.68  160.57 2057.96  162.97 2059.19
  167.46 2061.23  172.71 2064.02   195.9    2077  196.23 2077.01  197.89 2078.35
  202.29 2083.02
#Mann= 3 , 0 , 0
       0     .08       0   72.48     .05       0   106.2     .07       0
Bank Sta=72.48,106.2
Exp/Cntr=0.3,0.1

Type RM Length L Ch R = 1 ,84982   ,262.6,253.09,258.07
BEGIN DESCRIPTION:
84903.75
END DESCRIPTION:
XS GIS Cut Line= 3
  919378.1610727  807221.3695897  919312.5359963   807160.432165
  919229.7232047  807127.6196268
#Sta/Elev= 29
       0  2070.7    2.84 2068.91    5.94 2067.07   13.53 2062.16   32.42 2050.55
   41.63 2045.52    45.7 2043.44   49.74 2042.93   52.22 2042.93   61.28 2042.68
   66.39 2042.44   70.04 2042.36   74.97 2042.46   78.99 2043.12   85.97 2042.73
   89.27 2043.43   94.12 2045.64   96.72 2046.46  111.68  2051.9  113.85 2052.31
  124.51  2052.5  129.58    2053  135.53 2053.36   148.8 2061.31  150.87 2062.25
  155.47 2065.15  163.77 2070.06  173.92 2074.97  178.63 2077.94
#Mann= 3 , 0 , 0
       0     .07       0   41.63     .05       0   94.12    .075       0
Bank Sta=41.63,94.12
Exp/Cntr=0.5,0.3

Type RM Length L Ch R = 1 ,84729   ,59.65,57.81,65.79
BEGIN DESCRIPTION:
84650.66
END DESCRIPTION:
XS GIS Cut Line= 4
  919570.3486504  807036.9944236  919510.9730935   806991.681822
  919407.8488512  806936.9949411  919384.4105923  806930.7443973
#Sta/Elev= 30
       0 2084.56    5.06  2081.4   12.85 2077.93   19.68 2073.72   29.31 2066.57
   36.68 2060.82   48.99 2053.13    61.4 2045.24   63.52 2044.77   74.69 2042.72
   77.66 2042.19   79.04 2041.71   82.25  2041.5    85.4 2040.97   96.75 2040.69
  103.13 2040.73  116.34 2041.13  124.06 2044.28  127.64 2045.66  135.65 2047.54
  138.43 2048.76  143.82 2048.62  146.52 2048.75  154.68 2048.89  165.58 2048.19
   169.2 2050.25  170.57 2051.19   202.7 2075.15  212.37 2081.45  215.68 2083.16
#Mann= 3 , 0 , 0
       0     .07       0   74.69     .05       0  124.06     .07       0
#XS Ineff= 2 , 0
       0   65.69 2050.25  131.69       0 2050.25
Permanent Ineff=
       F       F
Bank Sta=74.69,124.06
Exp/Cntr=0.5,0.3

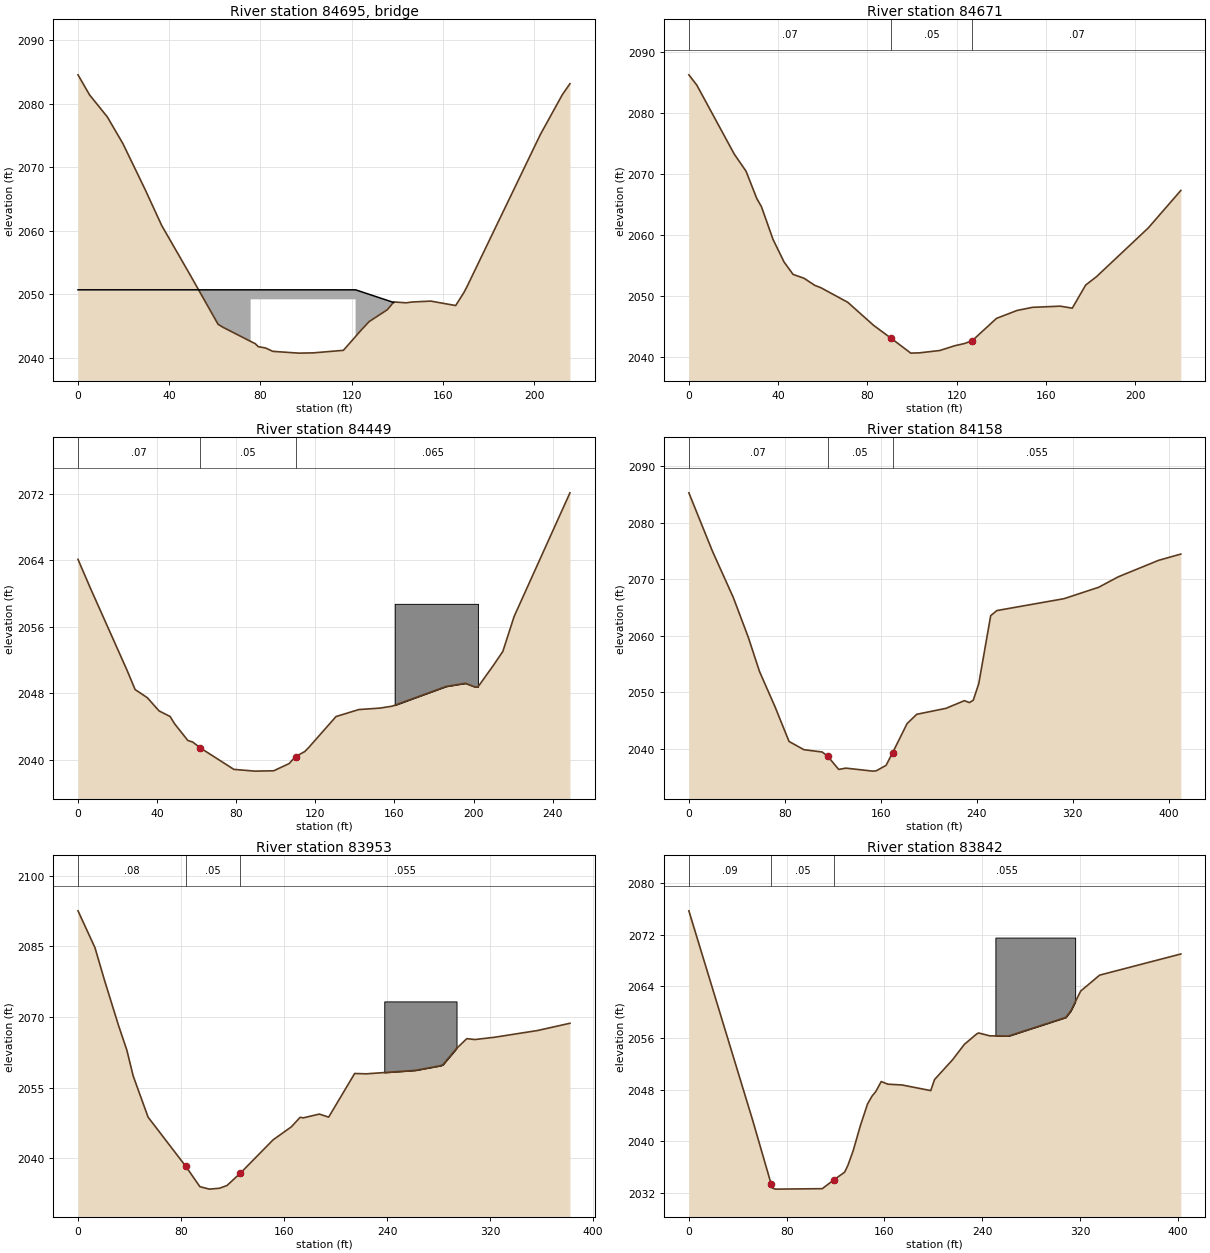
Type RM Length L Ch R = 3 ,84695   ,,,
BEGIN DESCRIPTION:
84613  FBSTR_5035
END DESCRIPTION:
Bridge Culvert--1,0,-1,-1, 0
Deck Dist Width WeirC Skew NumUp NumDn MinLoCord MaxHiCord MaxSubmerge Is_Ogee
28,12,2.6,0, 6, 6, , , 0.95, 0, 1,1,,
       0   75.69   75.69  121.69  121.69  138.43
 2050.67 2050.67 2050.67 2050.67 2050.67 2048.67
                 2049.17 2049.17
       0      81      81     127     127  157.59
 2050.67 2050.67 2050.67 2050.67 2050.67 2048.23
                 2049.17 2049.17
BR Coef=-1 , 0 , 0 ,, 0 ,,,0.8,0,,0,
WSPro=,,,, 1 ,,,, 0 ,,,, 0 ,,,,-1 ,-1 ,-1 , 0 , 0 , 0 , 0 , 0
BC Design=,, 0 ,, 0 ,,,,,,

Type RM Length L Ch R = 1 ,84671   ,214.48,221.77,201.32
BEGIN DESCRIPTION:
84592.85
END DESCRIPTION:
XS GIS Cut Line= 5
    919614.09836   806994.807606  919571.9115424  806963.5569356
  919510.9730935  806926.0567455  919462.5357321  806893.2452315
  919443.7861492  806860.4326932
#Sta/Elev= 30
       0  2086.3    3.55 2084.62   20.35 2073.29    25.6 2070.51   30.41 2066.03
   32.54 2064.65   37.68 2059.33   42.64 2055.61   46.67 2053.58   51.61 2052.94
   56.41 2051.78   59.16 2051.39   71.19    2049   82.73 2045.23   90.472043.136
    99.4 2040.67  103.38 2040.72  112.38  2041.1  119.08 2041.88  123.51 2042.25
   126.9 2042.71   137.8 2046.37  147.04 2047.67  153.96 2048.18  166.38 2048.37
  171.73 2048.04  177.73 2051.83  182.56  2053.2  205.73 2061.18  220.35 2067.34
#Mann= 3 , 0 , 0
       0     .07       0   90.47     .05       0   126.9     .07       0
#XS Ineff= 2 , 0
       0      71    2046     137       0 2043.93
Permanent Ineff=
       F       F
Bank Sta=90.47,126.9
Exp/Cntr=0.5,0.3

Type RM Length L Ch R = 1 ,84449   ,292.18,290.64,295.06
BEGIN DESCRIPTION:
84371.07
END DESCRIPTION:
XS GIS Cut Line= 4
   919745.348513   806827.620155  919671.9110249  806768.2445981
  919600.0364289  806733.8701921  919529.7237006  806708.8700654
#Sta/Elev= 30
       0 2064.11    6.24 2060.66   24.75  2050.8   28.87 2048.46   35.08 2047.47
   40.98 2045.89   46.56 2045.22    48.9 2044.32   55.56 2042.33   57.97 2042.15
    61.9 2041.43   78.81 2038.86   89.36 2038.65   98.92 2038.69  106.77 2039.56
  109.98  2040.4  114.57 2040.99  116.62 2041.48  130.44 2045.21  141.94 2046.05
  152.75 2046.23  158.87 2046.46  186.13 2048.83  195.83 2049.21  200.83 2048.76
  202.18 2048.76  210.09 2051.39  214.81 2053.05  220.49 2057.24  248.73 2072.11
#Mann= 3 , 0 , 0
       0     .07       0    61.9     .05       0  109.98    .065       0
#Block Obstruct= 1 ,-1
  160.14  202.192058.763
Bank Sta=61.9,109.98
Exp/Cntr=0.3,0.1

Type RM Length L Ch R = 1 ,84158   ,259.28,205.26,166.72
BEGIN DESCRIPTION:
84080.44
END DESCRIPTION:
XS GIS Cut Line= 6
   919950.036154  806627.6201658  919889.0987293  806560.4321973
  919801.5982859  806511.9948359  919693.7863918  806483.8699495
  919635.9737269  806486.9947093  919587.5363655  806499.4947726
#Sta/Elev= 30
       0 2085.25   19.61 2074.95   37.05 2066.74   49.56  2059.7   58.87 2053.67
   71.75 2047.46   83.51 2041.29   95.91 2039.83  111.15 2039.42  115.64  2038.7
  124.92 2036.34  130.88 2036.57   153.3 2036.04  156.18 2036.09   164.4 2037.06
   169.8 2039.27  181.92 2044.44  189.98 2046.09  214.33 2047.14   229.7  2048.5
  233.87 2048.16  237.11 2048.58   241.7 2051.52  251.64 2063.53  256.77 2064.43
   312.7 2066.53  341.55 2068.54  358.02  2070.4  391.56 2073.31  410.14 2074.42
#Mann= 3 , 0 , 0
       0     .07       0  115.64     .05       0   169.8    .055       0
Bank Sta=115.64,169.8
Exp/Cntr=0.3,0.1

Type RM Length L Ch R = 1 ,83953   ,122.45,111.54,67.26
BEGIN DESCRIPTION:
83875.17
END DESCRIPTION:
XS GIS Cut Line= 6
  920010.9735787  806352.6197965  919929.7236791   806343.244493
  919821.9107608  806346.3692528  919784.4105708  806349.4950367
  919706.2864551  806369.8075116  919640.6613787  806404.1819177
#Sta/Elev= 30
       0 2092.56   13.19 2084.72   20.57 2077.82   31.57 2068.13   37.92 2062.99
   42.84  2057.5   54.43 2048.74   83.64 2038.32   94.65 2033.97  102.07 2033.45
  109.99 2033.64  115.77 2034.23  126.16 2036.86  151.43  2043.9  165.68 2046.68
  172.58 2048.71   174.9 2048.58  187.44 2049.39  194.66 2048.74  214.87 2058.01
  223.89 2057.94  261.92 2058.67  281.77 2059.67  283.48 2059.89   294.1 2063.36
  301.98 2065.41   308.2 2065.22  323.33  2065.7  356.94 2067.14  382.08 2068.68
#Mann= 3 , 0 , 0
       0     .08       0   83.64     .05       0  126.16    .055       0
#Block Obstruct= 1 ,-1
  237.86  293.98 2073.32
Bank Sta=83.64,126.16
Exp/Cntr=0.3,0.1

Type RM Length L Ch R = 1 ,83842   ,197.02,111.08,13.19
BEGIN DESCRIPTION:
83763.64
END DESCRIPTION:
XS GIS Cut Line= 6
  919981.2858002  806227.6201873  919914.0988559  806229.1820551
  919870.3481222  806241.6821185  919815.6612412  806265.1193531
  919776.5981592  806294.8071316  919617.2231198   806380.744683
#Sta/Elev= 30
       0 2075.68   52.11 2043.33   67.21 2033.48   68.34 2032.78   70.97 2032.61
  109.16 2032.68  118.69 2034.05  127.44 2035.23  130.18 2036.31  134.42 2038.54
  140.45  2042.5   146.2 2045.79   149.9 2047.01  152.89 2047.69   157.4 2049.26
  162.85 2048.85  174.38 2048.73  197.91 2047.86  201.05 2049.57  215.96 2052.67
  225.46 2055.02  235.56 2056.63  237.06 2056.78  246.33 2056.33  261.62  2056.3
   308.4 2059.18  312.42 2060.15  320.61 2063.26  336.16 2065.73  402.56    2069
#Mann= 3 , 0 , 0
       0     .09       0   67.21     .05       0  118.69    .055       0
#Block Obstruct= 1 ,-1
  250.83  316.092071.539
Bank Sta=67.21,118.69
Exp/Cntr=0.5,0.3

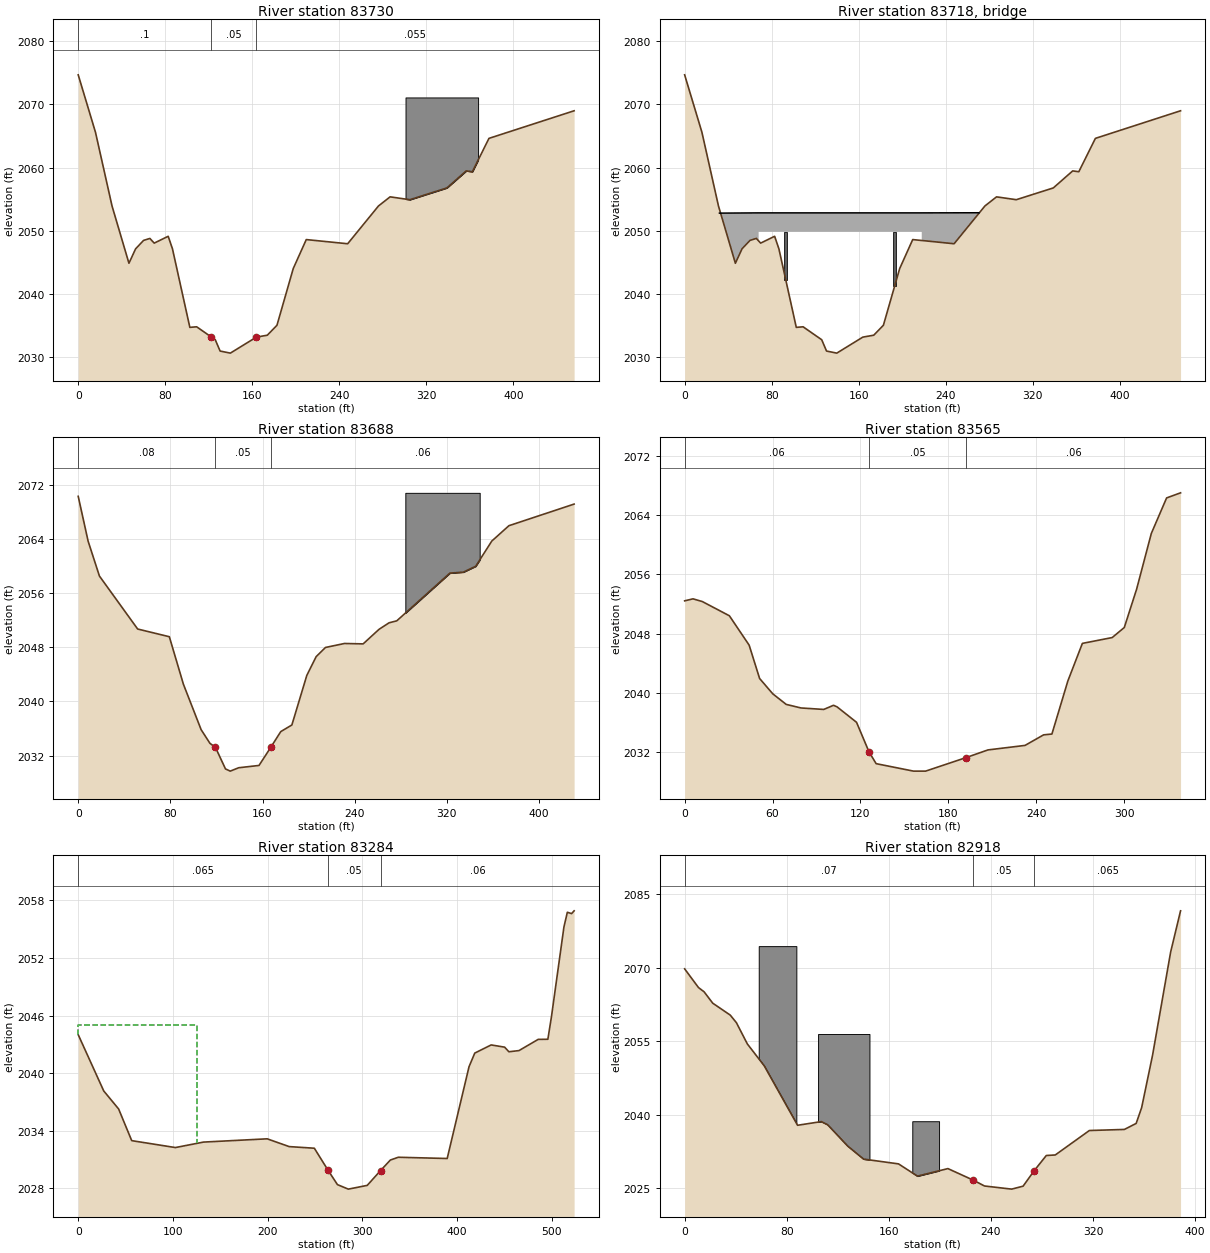
Type RM Length L Ch R = 1 ,83730   ,37.62,42.01,35.71
BEGIN DESCRIPTION:
83652.55
END DESCRIPTION:
XS GIS Cut Line= 6
  919851.5985392  806060.4327363  919793.7858743  806124.4949208
  919810.9735894  806194.8076491  919812.5364814  806247.9326622
  919764.0980959   806288.557612  919601.5982967  806365.1198598
#Sta/Elev= 30
       0 2074.65   15.89 2065.57   31.08 2053.94   46.64 2044.88   52.78 2047.16
    60.1 2048.49    65.9  2048.8   69.88 2048.06   82.73 2049.14   86.66 2047.16
  102.64 2034.75  108.91 2034.84  121.78  2033.3     126  2032.8  130.45 2031.01
  139.88 2030.68  163.82 2033.21  173.85 2033.51  182.73 2035.08   197.7 2044.04
  209.68 2048.62  247.74 2047.96  276.07 2053.93  286.75 2055.37  304.93 2054.92
  338.95 2056.78  356.77 2059.47   362.4 2059.34  377.64 2064.61  455.94 2068.97
#Mann= 3 , 0 , 0
       0      .1       0  121.78     .05       0  163.82    .055       0
#Block Obstruct= 1 ,-1
  300.92  367.652071.077
Bank Sta=121.78,163.82
Exp/Cntr=0.5,0.3

Type RM Length L Ch R = 3 ,83718   ,,,
Node Photo=H:\PROJ\06-0741\CE\GIS\DATA\FRENCH_BROAD_RIVER\SHAPEFILES\survey_data\photos\FBSTR_1255.JPG
BEGIN DESCRIPTION:
83630  FBSTR_1255
END DESCRIPTION:
Bridge Culvert--1,0,-1,-1, 0
Deck Dist Width WeirC Skew NumUp NumDn MinLoCord MaxHiCord MaxSubmerge Is_Ogee
10,24,2.6,0, 5, 5, , , 0.95, 0, 0,0,,
      32      68     143     218  270.58
  2052.8 2052.84 2052.84 2052.84 2052.86
         2049.84 2049.84 2049.84
      43      65     140     215  281.92
  2052.8 2052.84 2052.84 2052.84 2052.76
         2049.84 2049.84 2049.84
Pier Skew, UpSta & Num, DnSta & Num=  ,93, 2 ,90, 2 , 0 , 0 , 0 ,,
       3       3
    2030 2049.84
       3       3
    2030 2049.84
Pier Skew, UpSta & Num, DnSta & Num=  ,193, 2 ,190, 2 , 0 , 0 , 0 ,,
       3       3
    2030 2049.84
       3       3
    2030 2049.84
BR Coef=-1 , 0 , 0 ,, 0 ,,,0.8,0,,0,
WSPro=,,,, 1 ,,,, 0 ,,,, 0 ,,,,-1 ,-1 ,-1 , 0 , 0 , 0 , 0 , 0
BC Design=,, 0 ,, 0 ,,,,,,

Type RM Length L Ch R = 1 ,83688   ,91.44,123.35,136.57
BEGIN DESCRIPTION:
83610.53
END DESCRIPTION:
XS GIS Cut Line= 6
  919831.2860643   806047.932673  919764.0980959  806111.9948575
  919776.5981592  806202.6200606  919765.6609879  806235.4325989
  919740.6608612  806265.1193531  919593.7858851  806349.4950367
#Sta/Elev= 30
       0 2070.36    8.61 2063.72   18.42 2058.56    51.6 2050.72    79.1 2049.58
   91.32 2042.55  106.69 2035.83  114.32 2033.81  119.15  2033.2  127.83 2030.02
  131.96 2029.69   139.3 2030.19  156.94 2030.53  167.14 2033.21  175.83 2035.54
  185.47 2036.52  198.42 2043.85  206.53 2046.63  214.64 2047.99  231.12 2048.58
  247.33 2048.52  261.09 2050.67  269.82 2051.64  276.51 2051.93  322.59 2058.99
  334.37 2059.14  345.05 2060.01  359.02 2063.74  373.86 2066.01  430.47 2069.21
#Mann= 3 , 0 , 0
       0     .08       0  119.15     .05       0  167.14     .06       0
#Block Obstruct= 1 ,-1
  283.95   348.52070.876
Bank Sta=119.15,167.14
Exp/Cntr=0.5,0.3

Type RM Length L Ch R = 1 ,83565   ,317.61,280.99,244.24
BEGIN DESCRIPTION:
83487.19
END DESCRIPTION:
XS GIS Cut Line= 6
  919754.7238165  806005.7448312  919707.8483229   806044.806889
  919671.9110249  806077.6194273  919645.3490304  806126.0567886
  919620.3489038   806177.619934  919607.8488404  806293.2442396
#Sta/Elev= 30
       0 2052.43    5.74  2052.7   12.09 2052.33   30.53 2050.41   44.04 2046.43
   51.17 2041.92   60.18 2039.84   69.35 2038.41   79.42 2037.93   94.94 2037.73
  101.62 2038.29  104.04 2038.08  117.34 2035.99  125.85 2031.99  130.73 2030.39
  156.29 2029.38  164.48 2029.38  192.23 2031.22  207.04 2032.25  232.34 2032.86
  245.05 2034.29  250.71  2034.4  261.57 2041.57  271.51 2046.67  291.87 2047.46
  300.12 2048.82  308.52    2054  318.57 2061.55  329.01 2066.36  338.53 2067.05
#Mann= 3 , 0 , 0
       0     .06       0  125.85     .05       0  192.23     .06       0
Bank Sta=125.85,192.23
Exp/Cntr=0.3,0.1

Type RM Length L Ch R = 1 ,83284   ,533.96,366.13,312.14
BEGIN DESCRIPTION:
83206.21
END DESCRIPTION:
XS GIS Cut Line= 6
  919460.9738643  805824.4944249   919412.536503  805902.6195647
  919387.5363763  805958.8693376   919373.473421  806024.4944141
  919370.3486612  806244.8068782   919410.973611  806316.6824985
#Sta/Elev= 30
       0 2044.02   26.94 2038.16   42.66 2036.28   56.49 2032.98   102.6 2032.26
  132.25 2032.83  199.46 2033.17  222.72 2032.36  249.27 2032.19  263.65 2029.91
  273.65  2028.4  285.14 2027.93   305.1 2028.32  319.13 2029.86  329.51 2030.96
  337.87 2031.25   389.5 2031.12  412.55 2040.68  418.61  2042.1  435.91 2042.95
  450.12 2042.72  454.62 2042.24  465.28 2042.36  485.57 2043.53  495.77 2043.54
  499.61 2045.92  512.74 2055.24  516.34 2056.77  520.79 2056.63  523.49 2056.92
#Mann= 3 , 0 , 0
       0    .065       0  263.65     .05       0  319.13     .06       0
#XS Ineff= 2 , 0
       0     125    2045               0
Permanent Ineff=
       F       F
Bank Sta=263.65,319.13
Exp/Cntr=0.3,0.1

Type RM Length L Ch R = 1 ,82918   ,348.58,379.76,353.7
BEGIN DESCRIPTION:
82840.07
END DESCRIPTION:
XS GIS Cut Line= 6
  918820.3489468  806022.9325463  918893.7864349  806065.1193639
  918951.5980756  806079.1823192  918992.2240496  806107.3072057
  919062.5357537  806235.4325989  919062.5357537  806283.8699602
#Sta/Elev= 30
       0 2069.73   10.82 2065.92   15.26 2065.04   21.99 2062.73   35.74 2060.29
   40.53 2058.76   49.13 2054.41   62.34 2049.95   88.48 2037.81  107.13 2038.56
  112.05 2037.92  127.71 2033.58   140.2 2030.91  167.61 2029.93  182.43 2027.43
   206.3 2028.97  226.11 2026.62  234.97 2025.42  256.24 2024.78  265.21 2025.38
  274.03 2028.58  283.42 2031.64  290.45 2031.75  317.16 2036.74  344.62 2036.96
  353.84 2038.19  358.13 2041.41  366.69 2052.12  380.86 2073.17  388.62 2081.57
#Mann= 3 , 0 , 0
       0     .07       0  226.11     .05       0  274.03    .065       0
#Block Obstruct= 3 ,-1
   58.05   87.552074.366  104.56  144.83 2056.43  178.39  199.382038.637
Bank Sta=226.11,274.03
Exp/Cntr=0.3,0.1

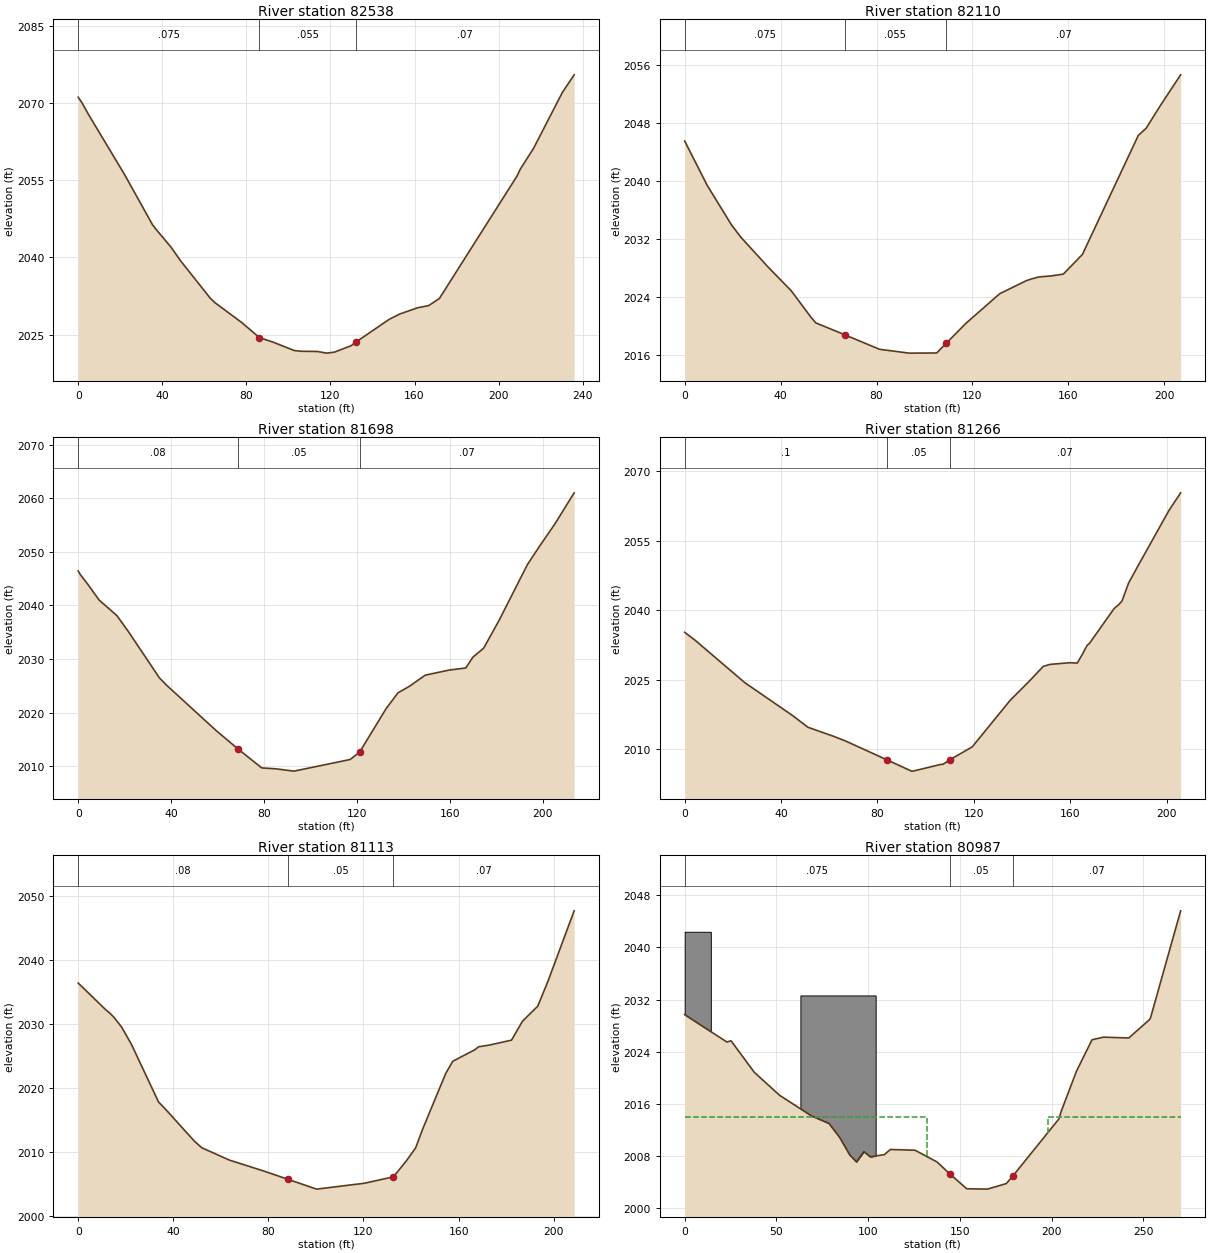
Type RM Length L Ch R = 1 ,82538   ,412.23,428.07,462.47
BEGIN DESCRIPTION:
82460.32
END DESCRIPTION:
XS GIS Cut Line= 4
  918639.0985405  806269.8070049  918685.9740341  806347.9321447
  918734.4113954  806405.7448097  918790.6611684  806446.3697595
#Sta/Elev= 30
       0 2071.11       2 2069.88    4.83 2067.79   21.96 2056.15   35.29 2046.38
   36.69 2045.61   44.18 2041.97   48.57  2039.4   62.75  2032.1   65.01 2031.21
   77.73 2027.36   86.21 2024.42   92.92  2023.5  102.81  2021.9  106.05 2021.76
  113.84 2021.72  118.08  2021.4  121.88 2021.59  129.86 2022.85  132.28 2023.59
   147.9 2027.95  152.97    2029  161.47 2030.21  166.72 2030.63  171.81 2032.01
   208.7 2055.76  210.28 2057.12  216.62 2061.18  230.31 2072.03  235.92 2075.45
#Mann= 3 , 0 , 0
       0    .075       0   86.21    .055       0  132.28     .07       0
Bank Sta=86.21,132.28
Exp/Cntr=0.3,0.1

Type RM Length L Ch R = 1 ,82110   ,413.77,412.13,413.8
BEGIN DESCRIPTION:
82032.25
END DESCRIPTION:
XS GIS Cut Line= 4
  918307.8483983  806490.1194691  918326.5990054  806554.1826777
  918348.4733481   806622.932514  918375.0363668  806685.4318065
#Sta/Elev= 25
       0 2045.51    9.35 2039.42   19.48 2033.96   23.35 2032.27   34.46 2028.24
   44.52 2024.82   52.67  2021.2   54.65 2020.43   66.75 2018.78   81.26 2016.78
   93.52 2016.25  105.08 2016.27  109.01 2017.59  117.22 2020.34  131.34 2024.44
  142.58 2026.26  143.95 2026.41  147.51 2026.75  153.06 2026.91  157.89 2027.15
  165.87 2029.87  189.16 2046.28  192.44 2047.27  198.27 2050.35  206.81 2054.64
#Mann= 3 , 0 , 0
       0    .075       0   66.75    .055       0  109.01     .07       0
Bank Sta=66.75,109.01
Exp/Cntr=0.3,0.1

Type RM Length L Ch R = 1 ,81698   ,405.17,431.64,465.13
BEGIN DESCRIPTION:
81620.12
END DESCRIPTION:
XS GIS Cut Line= 4
   917906.286552  806591.6818436  917932.8485465  806668.2451156
  917945.3486099  806726.0567563  917978.1611481  806791.6818328
#Sta/Elev= 28
       0 2046.45     .77 2045.86    4.21 2043.91    9.04    2041   16.66 2038.11
   21.65  2035.1   35.04 2026.43    38.3 2025.01   59.56 2016.57   68.83 2013.19
   79.03 2009.66   85.11 2009.49   92.92 2009.06  117.08 2011.23  121.17  2012.6
  132.64 2020.77  137.66 2023.67  142.66 2024.91  149.42 2026.98  159.79 2027.94
  166.88 2028.32  169.97 2030.35  174.58 2032.02  181.24 2037.22  193.45 2047.65
   198.9 2051.22  205.27 2055.23  213.56 2061.04
#Mann= 3 , 0 , 0
       0     .08       0   68.83     .05       0  121.17     .07       0
Bank Sta=68.83,121.17
Exp/Cntr=0.3,0.1

Type RM Length L Ch R = 1 ,81266   ,140.99,153.65,157.75
BEGIN DESCRIPTION:
81188.48
END DESCRIPTION:
XS GIS Cut Line= 4
  917523.4732645  806654.1821603  917512.5360932  806719.8072367
  917510.9732012  806796.3694846  917490.6607263  806855.7450415
#Sta/Elev= 30
       0 2035.21    4.17 2033.57   24.92 2024.35   44.87  2017.2   51.14  2014.7
   61.56 2012.79   66.53 2011.79   83.91 2007.67   94.12 2005.23   94.76 2005.22
  106.44 2006.69  107.19 2006.68   110.1 2007.68  119.37 2010.47  135.17 2020.56
  143.11 2024.69  148.82 2027.84  151.61 2028.28  159.78 2028.64  162.94 2028.56
  165.12  2030.5  167.03 2032.38  167.95 2032.77  178.26 2040.35  180.38  2041.3
  181.55 2042.01  184.26 2045.85  188.13 2049.53  200.95 2061.48  205.86 2065.35
#Mann= 3 , 0 , 0
       0      .1       0   83.91     .05       0   110.1     .07       0
Bank Sta=83.91,110.1
Exp/Cntr=0.3,0.1

Type RM Length L Ch R = 1 ,81113   ,142.34,126.2,107.08
BEGIN DESCRIPTION:
81034.83
END DESCRIPTION:
XS GIS Cut Line= 4
  917389.0983518  806626.0572738  917368.7858769  806702.6195216
  917356.2858135  806741.6826036  917343.7857502  806829.1820228
#Sta/Elev= 29
       0 2036.43   11.55 2032.27   13.34 2031.72   15.17 2031.02   18.29 2029.54
   22.39 2026.85    33.8 2017.84   36.74 2016.71   48.86 2011.73   51.95  2010.7
   63.58 2008.77   78.37 2007.02   88.052005.787  100.29 2004.23  120.23 2005.14
  132.59 2006.15  138.01 2008.64  141.94 2010.68  144.89 2013.61  154.63 2022.34
  157.58 2024.22  166.69 2025.98  168.38 2026.47  172.91 2026.74  182.26 2027.51
   186.9 2030.48  193.31 2032.82  197.59 2036.71  208.61 2047.72
#Mann= 3 , 0 , 0
       0     .08       0   88.05     .05       0  132.59     .07       0
Bank Sta=88.05,132.59
Exp/Cntr=0.5,0.3

Type RM Length L Ch R = 1 ,80987   ,45.38,35.35,27.61
BEGIN DESCRIPTION:
80908.64
END DESCRIPTION:
XS GIS Cut Line= 6
  917300.0360406   806583.869432  917248.4739194  806624.4943818
  917235.9738561  806638.5573371  917229.7233123  806679.1822869
  917239.0986159   806754.182667  917246.9110275  806822.9325032
#Sta/Elev= 30
       0 2029.69   23.05 2025.49   25.25 2025.69   37.96 2020.85   51.84 2017.31
    68.9 2014.22   78.64 2013.03   84.46 2010.88   89.99 2008.19   93.59 2007.14
   97.65 2008.71  101.14 2007.92  108.81 2008.24  112.15 2009.03  125.56 2008.92
  137.59 2007.12  144.432005.312  153.75 2003.02  164.99 2002.96  175.33 2003.81
  178.842004.953  204.01 2013.72  205.29 2014.91  213.56 2021.02  222.06 2025.84
  228.35 2026.24  242.09 2026.11  253.28  2028.9  253.97 2029.22  270.34 2045.59
#Mann= 3 , 0 , 0
       0    .075       0  144.43     .05       0  178.84     .07       0
#XS Ineff= 2 , 0
       0     132 2013.97     198       0 2013.97
Permanent Ineff=
       F       F
#Block Obstruct= 2 ,-1
   63.08  104.112032.631       0   14.252042.381
Bank Sta=144.43,178.84
Exp/Cntr=0.5,0.3