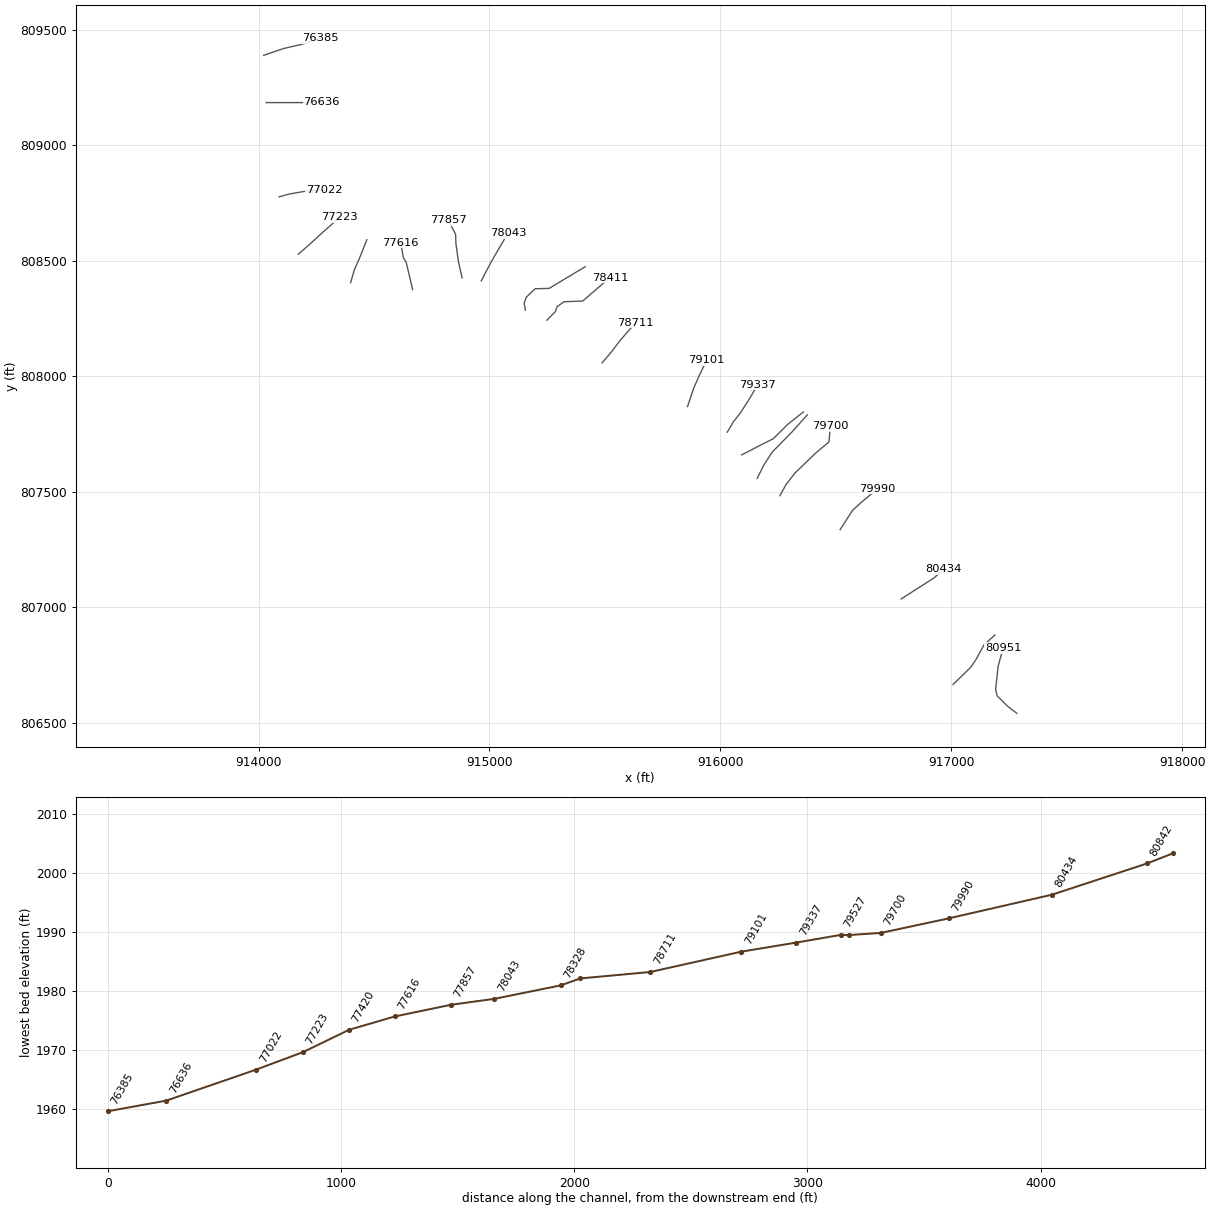
HEC-RAS study lds_big_laurel_crk.prj: lds_big_laurel_crk

--- lds_big_laurel_crk.g20 (geometry) --- (continued)

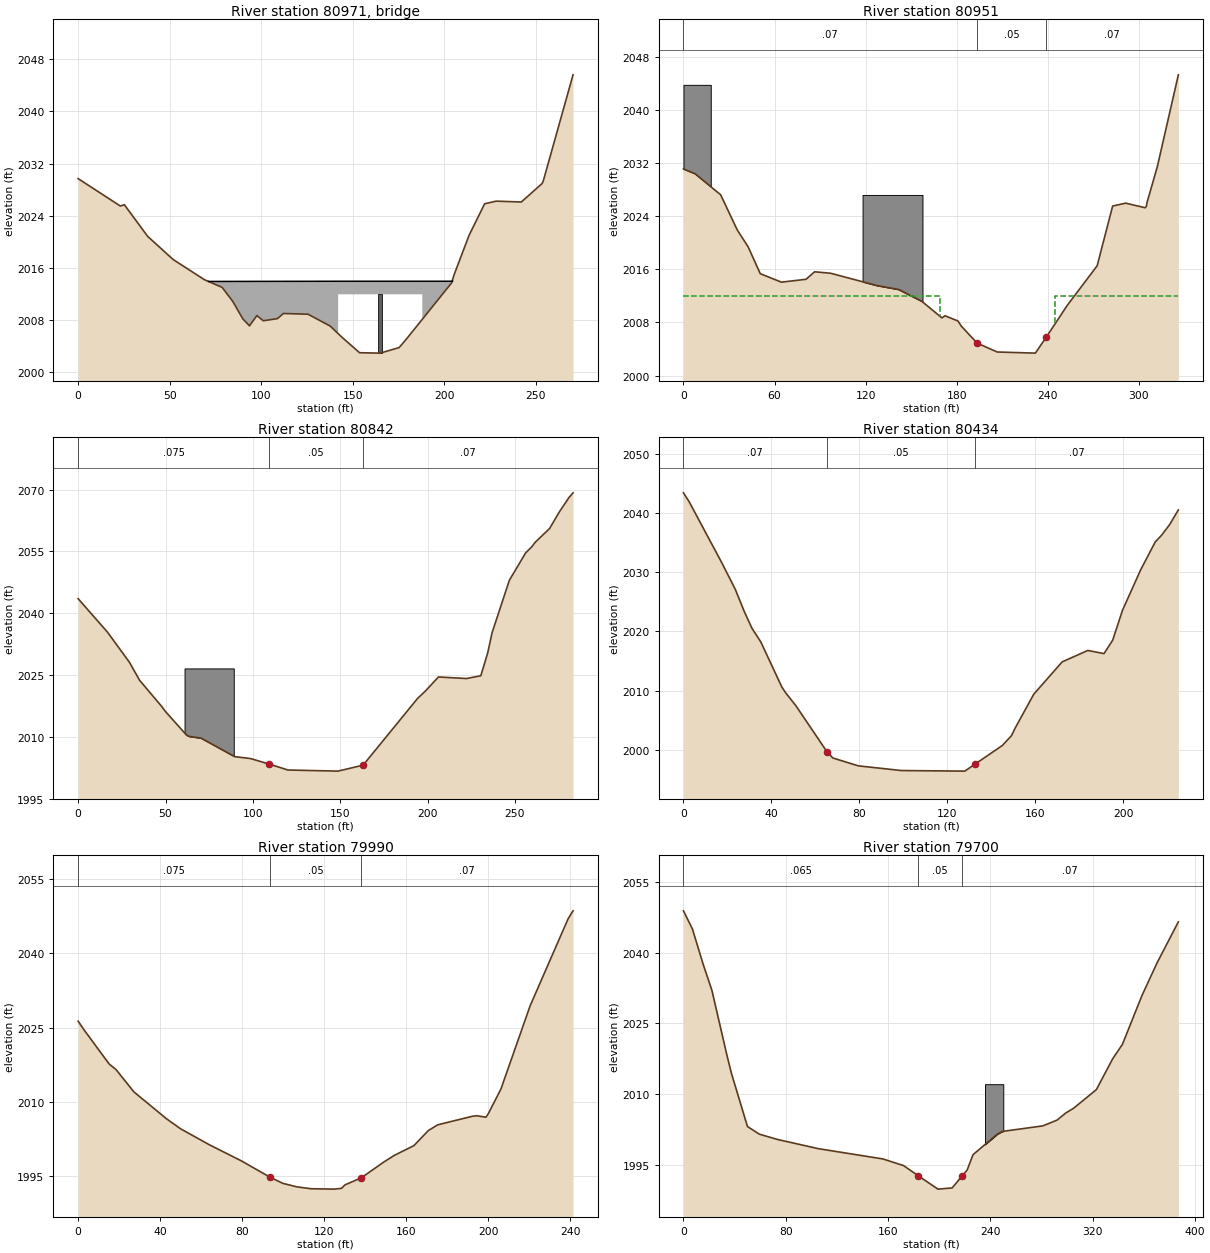
Type RM Length L Ch R = 3 ,80971   ,,,
Node Photo=H:\PROJ\06-0741\CE\GIS\DATA\FRENCH_BROAD_RIVER\SHAPEFILES\survey_data\photos\FBSTR_1256.JPG
BEGIN DESCRIPTION:
80895.6  FBSTR_1256
END DESCRIPTION:
Bridge Culvert--1,0,-1,-1, 0
Deck Dist Width WeirC Skew NumUp NumDn MinLoCord MaxHiCord MaxSubmerge Is_Ogee
7,13,2.6,0, 7, 7, , , 0.95, 0, 0,0,,
   71.21     142     142     165     188     188  204.51
 2013.94 2013.97 2013.97 2013.97 2013.97 2013.97 2013.97
                 2011.97 2011.97 2011.97
  121.17     184     184     207     230     230  264.22
 2013.93 2013.97 2013.97 2013.97 2013.97 2013.97 2013.92
                 2011.97 2011.97 2011.97
Pier Skew, UpSta & Num, DnSta & Num=  ,165, 2 ,207, 2 , 0 , 0 , 0 ,,
       2       2
    2000 2011.97
       2       2
    2000 2011.97
BR Coef=-1 , 0 , 0 ,, 0 ,,,0.8,0,,0,
WSPro=,,,, 1 ,,,, 0 ,,,, 0 ,,,,-1 ,-1 ,-1 , 0 , 0 , 0 , 0 , 0
BC Design=,, 0 ,, 0 ,,,,,,

Type RM Length L Ch R = 1 ,80951   ,173.09,109.64,86.9
BEGIN DESCRIPTION:
80873.28
END DESCRIPTION:
XS GIS Cut Line= 6
  917284.4112175  806541.6826144  917243.7862677  806572.9322606
  917198.4736661  806618.2448622  917192.2231223  806646.3697487
  917203.1613179  806746.3702554  917225.0356606   806824.494371
#Sta/Elev= 30
       0 2031.11    7.62 2030.39   24.46 2027.23   35.45 2021.92   42.59 2019.39
   50.58 2015.35   64.48 2014.07   80.71  2014.5   86.39 2015.63   96.94 2015.41
  127.39 2013.56  141.73 2012.97  157.05 2011.18  170.26 2008.69  172.33 2009.01
  180.87 2008.22  182.88 2007.49  193.39  2004.9  206.66 2003.56  231.79 2003.39
  238.95 2005.78  252.72 2010.55  272.51 2016.54  282.69 2025.52  291.26 2025.96
  304.09 2025.27  304.89 2025.46  305.31 2026.03  312.12 2031.44  325.97 2045.27
#Mann= 3 , 0 , 0
       0     .07       0  193.39     .05       0  238.95     .07       0
#XS Ineff= 2 , 0
       0     169    2012     245       0    2012
Permanent Ineff=
       F       F
#Block Obstruct= 2 ,-1
       0   17.982043.764  117.96  157.432027.197
Bank Sta=193.39,238.95
Exp/Cntr=0.5,0.3

Type RM Length L Ch R = 1 ,80842   ,426.37,407.69,366.92
BEGIN DESCRIPTION:
80763.64
END DESCRIPTION:
XS GIS Cut Line= 6
  917007.8489804  806666.6822236  917056.2863418  806713.5577172
   917085.973096  806743.2444714  917107.8484629  806776.0570097
  917142.2238932  806838.5573264  917189.0983625  806880.7451681
#Sta/Elev= 30
       0 2043.52   16.77 2035.41   29.34  2028.1   35.19 2023.71   47.87 2017.35
   49.75 2016.25   62.07 2010.41   63.58 2010.11   70.28 2009.71   89.62  2005.2
   98.65 2004.74  109.39  2003.4  120.03 2001.96   148.7 2001.69  163.08 2003.14
  194.24 2019.32  198.55 2021.05  206.22 2024.53  222.25 2024.15  230.44 2024.83
  234.38 2030.36  236.88 2035.26  246.79    2048   256.1 2054.63   259.6 2056.11
  261.52 2057.18  269.81 2060.55  275.36 2064.56  280.84 2068.03  283.22  2069.2
#Mann= 3 , 0 , 0
       0    .075       0  109.39     .05       0  163.08     .07       0
#Block Obstruct= 1 ,-1
   60.88   89.052026.606
Bank Sta=109.39,163.08
Exp/Cntr=0.3,0.1

Type RM Length L Ch R = 1 ,80434   ,421.52,444.09,453.33
BEGIN DESCRIPTION:
80355.95
END DESCRIPTION:
XS GIS Cut Line= 3
  916782.8488645  807036.9944236  916925.0361888  807127.6196268
  916967.2240306  807165.1198168
#Sta/Elev= 30
       0 2043.44    2.59 2041.93   17.43 2031.62   23.58 2027.11    27.7 2023.34
   31.16 2020.53   35.15 2018.25   44.75  2010.6   46.61 2009.56   51.01 2007.51
   65.26 1999.67   67.93 1998.61   79.55 1997.28   99.06 1996.49  127.95 1996.39
  132.471997.538  145.07 2000.74  149.19  2002.4  150.94 2003.73  159.32  2009.4
  172.23 2014.86  183.89 2016.79  191.26 2016.26  195.22 2018.54  199.64 2023.56
  207.86 2030.37  214.55 2035.14  217.36 2036.24  221.05 2038.04  225.06 2040.55
#Mann= 3 , 0 , 0
       0     .07       0   65.26     .05       0  132.47     .07       0
Bank Sta=65.26,132.47
Exp/Cntr=0.3,0.1

Type RM Length L Ch R = 1 ,79990   ,303.15,290.13,291.53
BEGIN DESCRIPTION:
79911.85
END DESCRIPTION:
XS GIS Cut Line= 4
  916518.7856666  807336.9949195  916571.9106797  807419.8077111
  916609.4108697  807454.1821172   916679.723598  807513.5576741
#Sta/Elev= 30
       0 2026.28    2.92  2024.5   15.12 2017.63   18.43 2016.52   27.18    2012
   43.02 2006.59   49.96 2004.54   64.11 2001.29   79.48 1998.09    93.6 1994.76
   99.77 1993.53   106.6 1992.82  113.53 1992.44   124.9 1992.36  128.37 1992.52
  130.18 1993.24     138 1994.63  149.06 1997.84  154.21 1999.19  163.67 2001.14
   170.8 2004.21  175.33 2005.35  192.23 2007.08  194.31 2007.18  198.83 2006.89
  199.98  2007.6  206.13 2012.58  220.43 2029.45  238.93    2047  241.29 2048.57
#Mann= 3 , 0 , 0
       0    .075       0    93.6     .05       0     138     .07       0
Bank Sta=93.6,138
Exp/Cntr=0.3,0.1

Type RM Length L Ch R = 1 ,79700   ,127.3,136.02,144.36
BEGIN DESCRIPTION:
79621.73
END DESCRIPTION:
XS GIS Cut Line= 6
  916257.8482527  807483.8698956  916284.4112713   807532.307257
  916323.4733291  807582.3075104  916412.5356403  807668.2450617
  916470.3483052  807716.6824231   916476.598849  807785.4322594
#Sta/Elev= 30
       0 2048.83    7.03 2044.97   15.34 2037.57   22.25 2031.98   33.92 2018.33
   37.43 2014.49   50.03 2003.16   59.34 2001.54   73.33 2000.43  105.39 1998.47
  155.95 1996.29  172.12 1994.88  183.55 1992.73  198.97  1989.9  210.02 1990.15
  217.771992.649   221.8 1993.94  226.37 1997.19  245.36 2001.55  249.14 2002.11
  280.94 2003.29  292.08 2004.52   298.9 2006.02  304.99 2007.02  322.85 2010.98
  335.54 2017.49   343.2 2020.56  358.32  2030.8  370.27 2037.81  386.91 2046.49
#Mann= 3 , 0 , 0
       0    .065       0  183.55     .05       0  217.77     .07       0
#Block Obstruct= 1 ,-1
  235.74  250.052012.119
Bank Sta=183.55,217.77
Exp/Cntr=0.5,0.3

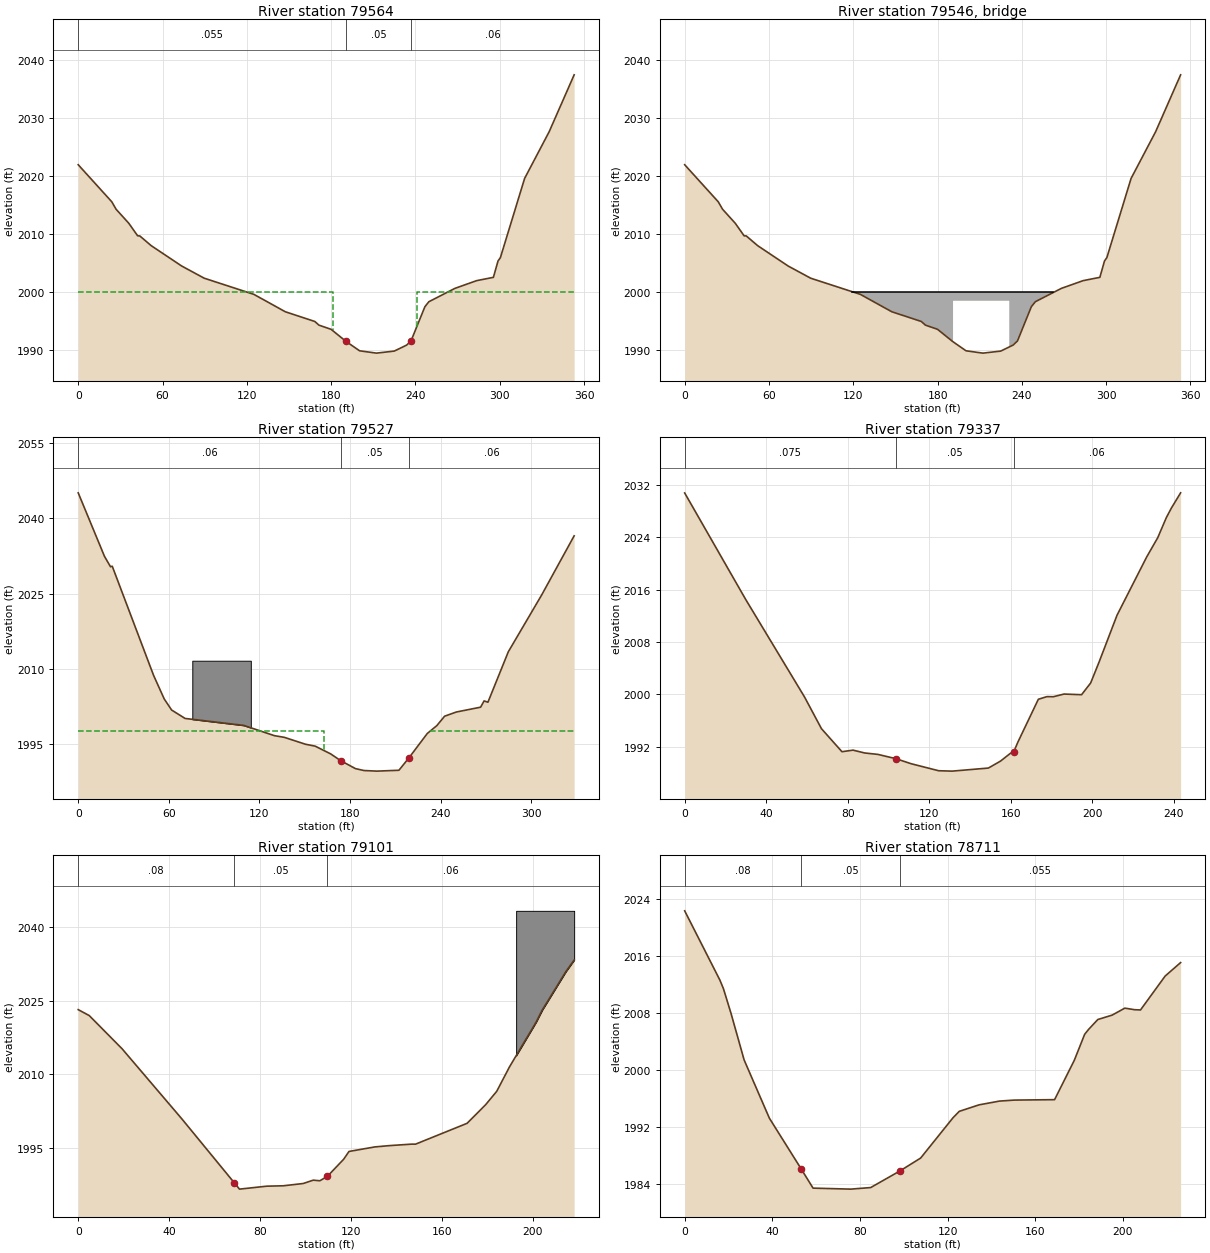
Type RM Length L Ch R = 1 ,79564   ,90.04,36.88,30.47
BEGIN DESCRIPTION:
79485.71
END DESCRIPTION:
XS GIS Cut Line= 5
  916159.4106379  807558.8692515  916187.5365486  807615.1200486
  916223.4738466  807671.3698215   916309.411398  807758.8692407
  916376.5983423  807833.8696207
#Sta/Elev= 30
       0 2021.98   23.93 2015.59   26.95 2014.32   35.97 2011.91   42.31 2009.74
   43.84 2009.72   51.92 2008.05   73.64 2004.54    89.7 2002.44  125.02 1999.66
  147.44 1996.66  168.41 1994.99  171.34 1994.36  179.99 1993.64  190.62 1991.56
  200.27 1989.94  212.28 1989.54  224.92 1989.89  233.73 1990.92  236.86 1991.63
  246.74 1997.53  249.57 1998.39  268.12 2000.69  283.58 2002.02   295.5 2002.59
  298.79  2005.4  300.49 2005.99  317.72 2019.62  335.21 2027.67  352.98 2037.46
#Mann= 3 , 0 , 0
       0    .055       0  190.62     .05       0  236.86     .06       0
#XS Ineff= 2 , 0
       0     181 2000.05     241       0 2000.05
Permanent Ineff=
       F       F
Bank Sta=190.62,236.86
Exp/Cntr=0.5,0.3

Type RM Length L Ch R = 3 ,79546   ,,,
Node Photo=H:\PROJ\06-0741\CE\GIS\DATA\FRENCH_BROAD_RIVER\SHAPEFILES\survey_data\photos\FBSTR_1770.JPG
BEGIN DESCRIPTION:
79470  FBSTR_1770
END DESCRIPTION:
Bridge Culvert--1,0,-1,-1, 0
Deck Dist Width WeirC Skew NumUp NumDn MinLoCord MaxHiCord MaxSubmerge Is_Ogee
8,10,2.6,0, 7, 7, , , 0.95, 0, 1,1,,
  119.24     191     191     221     231     231  261.95
 2000.05 2000.05 2000.05 2000.05 2000.05 2000.05 2000.05
                 1998.55 1998.55 1998.55
    70.8     178     178     198     218     218  241.53
 2000.07 2000.05 2000.05 2000.05 2000.05 2000.05 2000.05
                 1998.55 1998.55 1998.55
BR Coef=-1 , 0 , 0 ,, 0 ,,,0.8,0,,0,
WSPro=,,,, 1 ,,,, 0 ,,,, 0 ,,,,-1 ,-1 ,-1 , 0 , 0 , 0 , 0 , 0
BC Design=,, 0 ,, 0 ,,,,,,

Type RM Length L Ch R = 1 ,79527   ,147.26,190.01,211.36
BEGIN DESCRIPTION:
79448.83
END DESCRIPTION:
XS GIS Cut Line= 5
  916092.2236936  807660.4326502  916173.4735933  807702.6194678
  916229.7233662  807730.7443542  916290.6607909   807791.681779
  916359.4106272  807846.3696841
#Sta/Elev= 30
       0 2045.09   17.41 2032.41    21.4 2030.34   22.55 2030.44   49.93 2008.66
   56.99 2003.95   61.87 2001.75    70.8 2000.07  109.67 1998.68  130.02 1996.63
  136.53  1996.3  150.49 1994.93     157 1994.54  167.21    1993  173.82 1991.65
  183.64 1990.06  189.25 1989.68  197.77 1989.56  212.41 1989.73     219 1992.19
   231.2 1997.07  237.51 1998.64  242.67 2000.52  250.37 2001.35  266.52 2002.32
   268.8 2003.57  271.37 2003.31  284.86 2013.37  306.96 2024.71  328.47 2036.51
#Mann= 3 , 0 , 0
       0     .06       0  173.82     .05       0     219     .06       0
#XS Ineff= 2 , 0
       0     163 1997.55     233       0 1997.55
Permanent Ineff=
       F       F
#Block Obstruct= 1 ,-1
   75.56  114.312011.594
Bank Sta=173.82,219
Exp/Cntr=0.5,0.3

Type RM Length L Ch R = 1 ,79337   ,217.24,235.51,242.95
BEGIN DESCRIPTION:
79258.82
END DESCRIPTION:
XS GIS Cut Line= 5
   916029.723377  807758.8692407  916057.8482634  807805.7447343
  916087.5360419  807843.2449243  916131.2857515  807911.9947606
  916160.9735299  807963.5568817
#Sta/Elev= 30
       0 2030.81   29.92 2014.54   58.79 1999.63   67.16 1994.75   77.22 1991.23
   82.67 1991.47   88.32 1991.04   94.86 1990.82  103.74 1990.16  111.22 1989.39
  124.68 1988.32  131.33 1988.26   149.1 1988.73  155.05 1989.79  159.94 1990.99
  161.51  1991.2  163.64 1992.73  173.63 1999.25  177.89 1999.66  180.99 1999.64
  186.26 2000.05  194.85 1999.95  199.31 2001.74  203.42 2004.92  212.25  2012.1
  226.84 2021.03  232.24 2023.96  236.47 2027.04  238.93 2028.49  243.48 2030.83
#Mann= 3 , 0 , 0
       0    .075       0  103.74     .05       0  161.51     .06       0
Bank Sta=103.74,161.51
Exp/Cntr=0.3,0.1

Type RM Length L Ch R = 1 ,79101   ,405.2,390.4,361.17
BEGIN DESCRIPTION:
79023.32
END DESCRIPTION:
XS GIS Cut Line= 4
  915857.8482742  807869.8069188  915884.4112928  807949.4949506
  915910.9732873  808008.8694833  915940.6610658     808071.3698
#Sta/Elev= 26
       0 2023.17    4.85 2021.97   19.33 2015.21    45.6 2000.99   68.661988.019
   70.97 1986.72   82.99 1987.32   90.29  1987.4      99 1987.86  103.41 1988.54
  106.36 1988.42  109.68 1989.33  116.82 1992.79  119.16 1994.37   130.5 1995.29
  136.77 1995.55   146.8 1995.86  148.43 1995.85   171.1 2000.08  179.28 2003.86
  184.18 2006.59  189.72 2011.49  201.52 2020.65  204.17 2023.06  214.62 2030.91
  218.24 2033.24
#Mann= 3 , 0 , 0
       0     .08       0   68.66     .05       0  109.68     .06       0
#Block Obstruct= 1 ,-1
  192.71  218.242043.237
Bank Sta=68.66,109.68
Exp/Cntr=0.3,0.1

Type RM Length L Ch R = 1 ,78711   ,299.06,300.19,225
BEGIN DESCRIPTION:
78632.92
END DESCRIPTION:
XS GIS Cut Line= 4
  915487.5360742  808058.8697366   915526.598132  808104.1823382
   915565.661214  808155.7444594  915632.8481583  808232.3077314
#Sta/Elev= 28
       0 2022.31   16.08 2012.59   17.69 2011.39   21.14 2007.94   27.14 2001.39
   38.67 1993.22   53.15 1986.12    58.6 1983.41   75.84 1983.27   84.91 1983.49
   98.31 1985.83  107.71 1987.63  122.51 1993.29  125.34 1994.18  134.34 1995.09
  143.68 1995.62  150.54 1995.76  168.85 1995.82  177.85 2001.34  182.58 2004.99
  184.35 2005.67  188.57 2007.06  195.12 2007.68  200.91 2008.66  205.36 2008.44
  208.06  2008.4  219.32 2013.16  226.38 2015.05
#Mann= 3 , 0 , 0
       0     .08       0   53.15     .05       0   98.31    .055       0
Bank Sta=53.15,98.31
Exp/Cntr=0.5,0.3

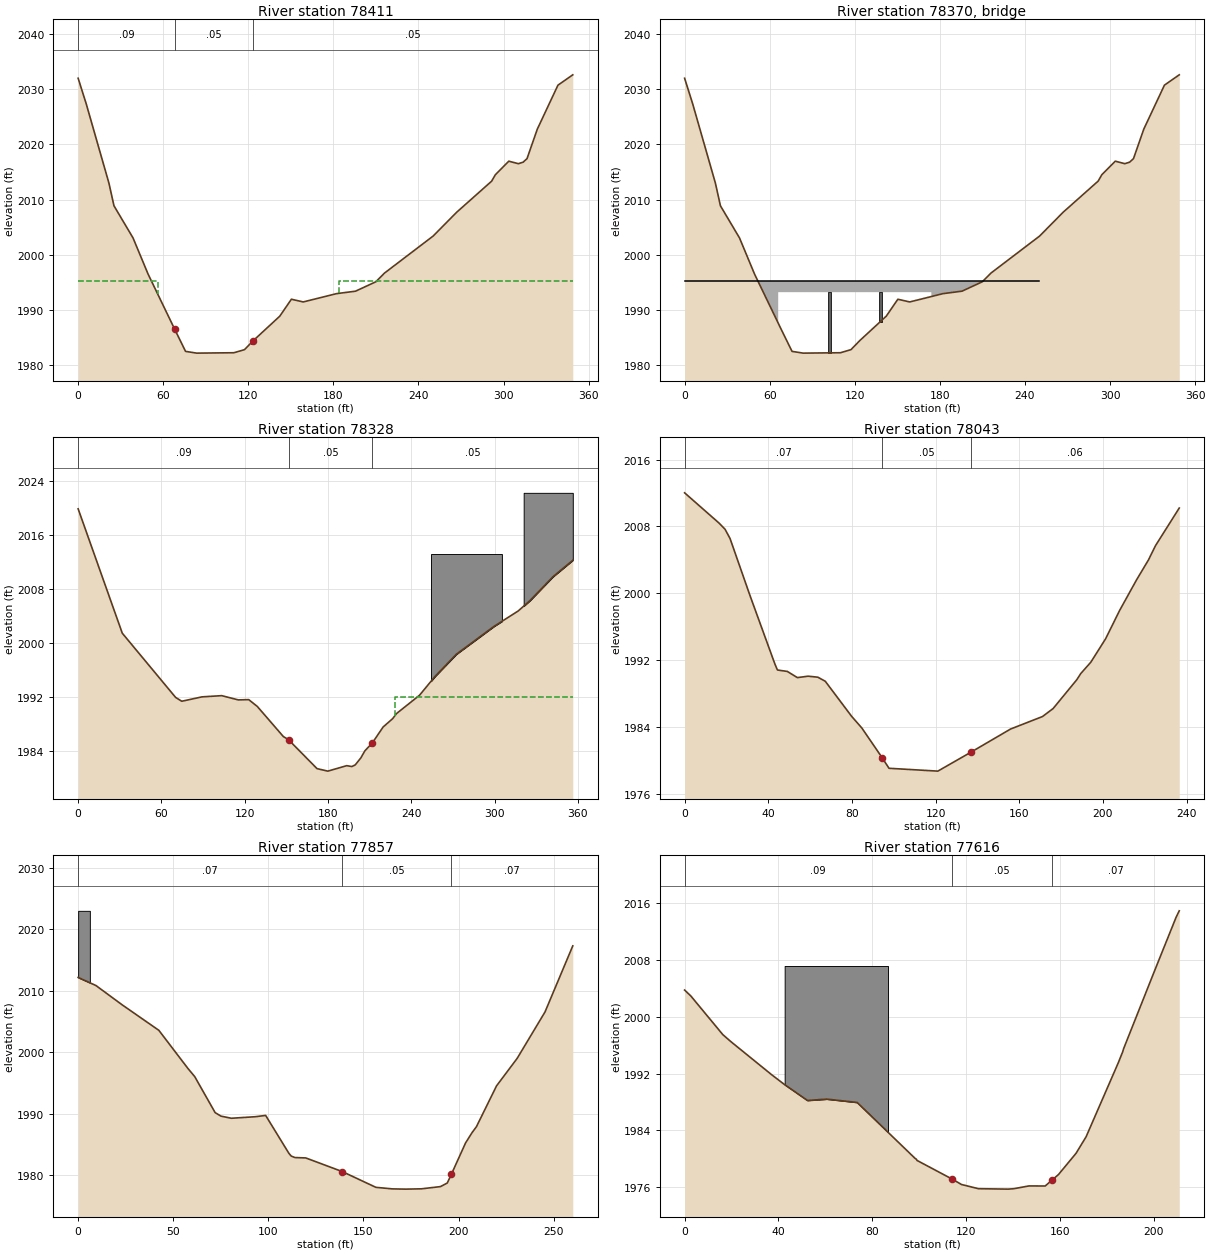
Type RM Length L Ch R = 1 ,78411   ,135.18,82.63,114.6
BEGIN DESCRIPTION:
78332.72
END DESCRIPTION:
XS GIS Cut Line= 6
  915248.6020491  808243.6228236  915285.5829821  808281.1475938
  915292.6528663  808301.8134093  915323.1077523  808323.5668993
  915403.5956652  808326.2860855  915521.6083484  808427.9836512
#Sta/Elev= 30
       0 2031.96    5.68 2027.34    21.7 2012.98   25.27 2008.86    38.7 2003.05
   49.33 1996.49   68.04 1986.53   75.75  1982.5   83.56 1982.18  109.87 1982.25
  117.32 1982.81   123.5 1984.44   142.2 1988.87  150.39 1991.94  158.75 1991.45
  182.19 1992.95  195.64  1993.4  209.95  1995.1  216.07 1996.68  250.35 2003.38
  266.94 2007.69  291.64 2013.33  294.22 2014.48  303.71 2016.94  310.45 2016.49
  313.82 2016.76  316.56  2017.4  323.84 2022.75  338.39 2030.71  348.84 2032.58
#Mann= 3 , 0 , 0
       0     .09       0   68.04     .05       0   123.5     .05       0
#XS Ineff= 2 , 0
       0      56 1995.22     184       0 1995.22
Permanent Ineff=
       F       F
Bank Sta=68.04,123.5
Exp/Cntr=0.5,0.3

Type RM Length L Ch R = 3 ,78370   ,,,
BEGIN DESCRIPTION:
78290  FBSTR_1270
END DESCRIPTION:
Bridge Culvert--1,0,-1,-1, 0
Deck Dist Width WeirC Skew NumUp NumDn MinLoCord MaxHiCord MaxSubmerge Is_Ogee
26,38,2.6,0, 7, 7, , , 0.95, 0, 1,1,,
       0      66      66     120     174     174     250
 1995.22 1995.22 1995.22 1995.22 1995.22 1995.22 1995.22
                 1993.22 1993.22 1993.22
       0     115     115     169     213     213   258.2
 1995.18 1995.22 1995.22 1995.22 1995.22 1995.22 1995.28
                 1993.22 1993.22 1993.22
Pier Skew, UpSta & Num, DnSta & Num=  ,102, 2 ,151, 2 , 0 , 0 , 0 ,,
       2       2
    1980 1993.22
       2       2
    1980 1993.22
Pier Skew, UpSta & Num, DnSta & Num=  ,138, 2 ,187, 2 , 0 , 0 , 0 ,,
       2       2
    1980 1993.22
       2       2
    1980 1993.22
BR Coef=-1 , 0 , 0 ,, 0 ,,,0.8,0,,0,
WSPro=,,,, 1 ,,,, 0 ,,,, 0 ,,,,-1 ,-1 ,-1 , 0 , 0 , 0 , 0 , 0
BC Design=,, 0 ,, 0 ,,,,,,

Type RM Length L Ch R = 1 ,78328   ,215.7,285.47,337.66
BEGIN DESCRIPTION:
78250.10
END DESCRIPTION:
XS GIS Cut Line= 6
  915155.6058794  808287.1298035  915150.1675069  808317.5846895
  915159.9565774  808343.6888775  915197.4813476   808379.582136
  915258.3911196  808381.2136477  915415.0162475  808475.2974919
#Sta/Elev= 30
       0  2019.9   31.79 2001.46    70.2 1991.94   74.63 1991.37   89.22 1992.02
  103.41  1992.2  115.36 1991.57  122.86 1991.61  129.04  1990.6  147.78 1986.14
  151.52 1985.67  172.06 1981.38  179.85 1981.01  193.42 1981.82  197.15 1981.69
  199.54 1981.93  203.58 1982.96  206.49 1984.01  211.96 1985.21  219.64 1987.55
  226.47 1988.78  229.35 1989.55  245.87 1992.26  256.96 1995.03  272.41 1998.34
  299.31 2002.44  316.85 2004.74  325.42 2006.29  341.98 2009.83  356.26 2012.27
#Mann= 3 , 0 , 0
       0     .09       0  151.52     .05       0  211.96     .05       0
#XS Ineff= 2 , 0
       0     100    1992     228       0    1992
Permanent Ineff=
       F       F
#Block Obstruct= 2 ,-1
  254.17  305.212013.197  320.88  356.262022.272
Bank Sta=151.52,211.96
Exp/Cntr=0.5,0.3

Type RM Length L Ch R = 1 ,78043   ,123.77,185.94,259.86
BEGIN DESCRIPTION:
77964.63
END DESCRIPTION:
XS GIS Cut Line= 3
  914964.0983543  808413.5571135  915010.9738479  808502.6194247
  915079.7236841  808619.8076465
#Sta/Elev= 30
       0 2012.02   16.51 2008.39   19.34 2007.66   21.73 2006.55   31.29 1999.71
   43.15 1991.55   44.38 1990.82   49.11 1990.65   53.92 1989.91   59.04 1990.08
   63.69 1989.96   67.27 1989.47   79.85 1985.28   84.77 1983.87   94.391980.349
   97.73 1979.06  121.09 1978.72  136.87 1980.98  155.88 1983.76  171.11 1985.25
  176.21 1986.21   187.5 1989.65  189.44  1990.4  194.22 1991.75  201.31 1994.56
  208.03 1997.96  216.13 2001.62  221.81    2004  225.16  2005.7  236.51  2010.2
#Mann= 3 , 0 , 0
       0     .07       0   94.39     .05       0  136.87     .06       0
Bank Sta=94.39,136.87
Exp/Cntr=0.3,0.1

Type RM Length L Ch R = 1 ,77857   ,224.05,241.01,235.77
BEGIN DESCRIPTION:
77778.68
END DESCRIPTION:
XS GIS Cut Line= 5
  914881.2865869  808426.0571769  914865.6607396  808496.3699051
  914854.7235682  808574.4950449  914853.1606763  808615.1199947
    914821.91103  808676.0574195
#Sta/Elev= 30
       0 2012.18    9.37 2010.86   23.19 2007.71   42.43 2003.57   57.67 1997.38
    61.3 1996.03   72.02 1990.17   75.05  1989.6   80.55 1989.25    93.1  1989.5
   98.58 1989.71  110.84 1983.52  112.05 1983.09     114 1982.85  119.66 1982.79
  138.77 1980.58  156.56    1978  165.23 1977.75  172.21 1977.71  180.49 1977.76
  190.48 1978.12  194.07 1978.71  196.28 1980.16  203.69 1985.24  207.25 1986.98
  209.37 1987.86  219.98 1994.53  230.79 1998.99  245.45 2006.56  260.05 2017.32
#Mann= 3 , 0 , 0
       0     .07       0  138.77     .05       0  196.28     .07       0
#Block Obstruct= 1 ,-1
       0    6.152023.028
Bank Sta=138.77,196.28
Exp/Cntr=0.3,0.1

Type RM Length L Ch R = 1 ,77616   ,249.38,195.92,164.58
BEGIN DESCRIPTION:
77537.67
END DESCRIPTION:
XS GIS Cut Line= 5
  914667.2236423  808376.0569235  914651.5988192      808441.682
  914639.0987559  808494.8070131  914626.5986925   808515.119488
  914615.6615212  808579.1826967
#Sta/Elev= 29
       0 2003.75    2.59 2002.94   16.28 1997.48    19.8 1996.47   37.12 1991.83
   42.63 1990.44   52.36 1988.21   60.65  1988.4   73.55 1987.93   98.28 1980.05
   98.81 1979.94   99.08 1979.77  113.91 1977.17  118.06 1976.38  125.28 1975.79
  137.98 1975.73   140.4 1975.79   146.8 1976.18  153.72 1976.17   156.71977.016
  159.39 1977.78   166.9 1980.78  171.17  1983.1  184.85 1993.48  186.77 1995.06
  187.18 1995.51   200.3 2006.41  209.56 2014.01  210.88  2014.9
#Mann= 3 , 0 , 0
       0     .09       0  113.91     .05       0   156.7     .07       0
#Block Obstruct= 1 ,-1
   42.65    86.72007.136
Bank Sta=113.91,156.7
Exp/Cntr=0.3,0.1

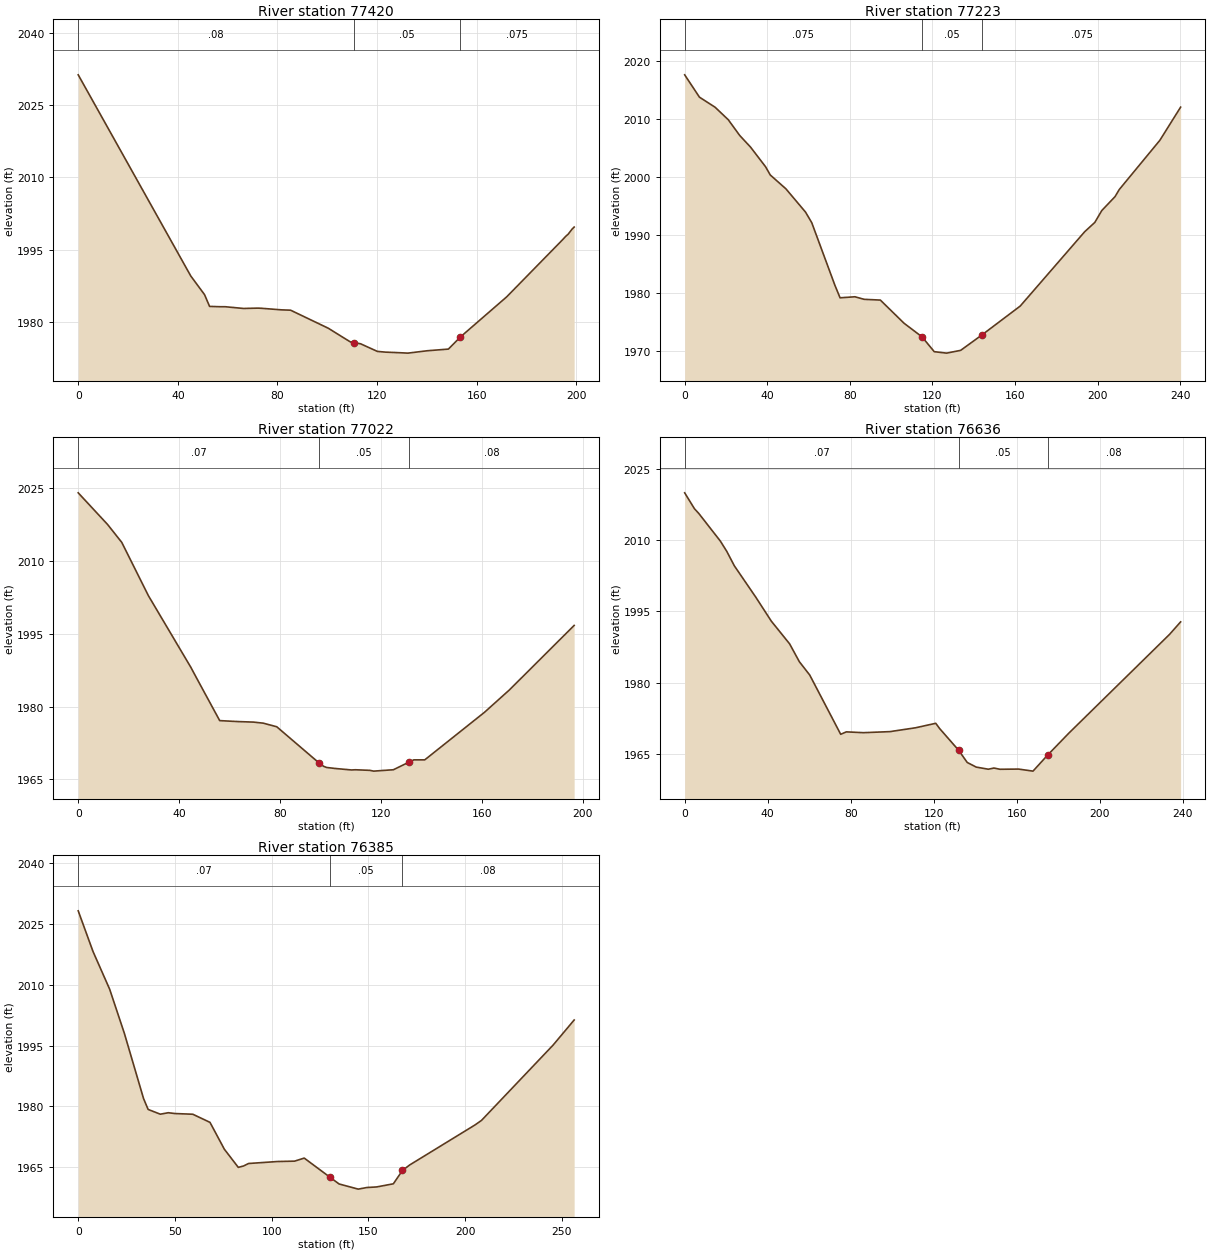
Type RM Length L Ch R = 1 ,77420   ,227.67,197.09,168.88
BEGIN DESCRIPTION:
77341.75
END DESCRIPTION:
XS GIS Cut Line= 4
  914398.4738168   808405.744702    914414.09864  808460.4326071
  914434.4111149  808505.7452087  914468.7865451  808591.6817359
#Sta/Elev= 29
       0 2031.35   45.19 1989.51   50.71 1985.64   52.74 1983.19   56.88 1983.12
   59.01 1983.12   66.35 1982.76   72.18 1982.83   73.46  1982.8   81.63 1982.47
   85.26  1982.4  100.42 1978.64  106.53 1976.67  109.27  1975.8  110.53 1975.68
  113.37 1975.41  120.09 1973.83  123.29 1973.68  129.63 1973.54  132.35 1973.47
  140.07 1973.96  148.61 1974.31  153.45 1976.84     172 1985.17  194.29 1996.97
  195.69 1997.75  196.71 1998.22  198.29 1999.28  199.09 1999.69
#Mann= 3 , 0 , 0
       0     .08       0  110.53     .05       0  153.45    .075       0
Bank Sta=110.53,153.45
Exp/Cntr=0.3,0.1

Type RM Length L Ch R = 1 ,77223   ,236.88,201.05,155.39
BEGIN DESCRIPTION:
77144.66
END DESCRIPTION:
XS GIS Cut Line= 4
   914171.910809  808529.1824434  914220.3481703   808571.369261
  914278.1608352  808624.4942741  914351.5983233  808688.5574828
#Sta/Elev= 30
       0 2017.64    7.16 2013.79   14.72 2012.06   21.12  2009.9   26.66 2007.19
   31.94 2005.17   39.18  2001.8   41.46 2000.38      49 1998.01   58.51    1994
   61.54 1992.17   72.73 1981.41   75.26 1979.22   82.46  1979.4   86.91 1978.96
   94.77 1978.83  106.28 1974.83  114.94  1972.5  120.88 1969.94  126.87 1969.69
  133.68 1970.17  144.22 1972.89  162.52  1977.8  193.72  1990.6  198.64 1992.21
  202.03 1994.26  208.43 1996.65  210.49 1997.88  230.15 2006.36   240.2 2012.07
#Mann= 3 , 0 , 0
       0    .075       0  114.94     .05       0  144.22    .075       0
Bank Sta=114.94,144.22
Exp/Cntr=0.3,0.1

Type RM Length L Ch R = 1 ,77022   ,397.67,385.99,382.54
BEGIN DESCRIPTION:
76943.61
END DESCRIPTION:
XS GIS Cut Line= 4
  914089.0990415   808777.619794  914134.4106189  808790.1198573
  914217.2234105  808804.1817885   914282.848487  808805.7446804
#Sta/Elev= 29
       0    2024   11.64 2017.49   17.27  2013.8   27.81 2002.85   44.69 1988.06
      47 1985.82    56.1 1977.12   56.68  1977.1   63.26 1976.92   69.52 1976.81
   73.39 1976.59   78.73 1975.85   95.46 1968.42   97.31 1967.71   98.52 1967.47
   98.87 1967.45   101.8 1967.27  108.36 1966.96  109.94    1967  115.66 1966.88
  117.15 1966.72  122.88 1966.93  124.95    1967     131 1968.53  133.08 1969.04
  137.42 1969.04  161.08 1978.82  170.99 1983.44  196.65 1996.71
#Mann= 3 , 0 , 0
       0     .07       0   95.46     .05       0     131     .08       0
Bank Sta=95.46,131
Exp/Cntr=0.3,0.1

Type RM Length L Ch R = 1 ,76636   ,226.38,250.53,266.74
BEGIN DESCRIPTION:
76557.62
END DESCRIPTION:
XS GIS Cut Line= 4
  914032.8482444   809185.432184  914107.8486245   809185.432184
  914200.0356954   809185.432184  914271.9113157   809186.995076
#Sta/Elev= 30
       0 2019.93    4.71 2016.59    6.78 2015.61    17.2 2009.79   20.32 2007.61
   23.93  2004.6   34.16 1998.08   41.78 1992.96    50.6 1988.19   55.29 1984.44
   60.29 1981.64   75.21 1969.19   77.93  1969.7   86.17 1969.53   98.94 1969.75
  111.32 1970.56  121.03  1971.5  122.96 1970.37  132.06 1965.84  136.21 1963.27
  140.53  1962.3  146.38 1961.85  149.09  1962.1  151.98 1961.84  160.97 1961.88
  167.92 1961.45  175.05 1964.86  185.27 1969.46  233.78  1990.2  239.08 1992.81
#Mann= 3 , 0 , 0
       0     .07       0  132.06     .05       0  175.05     .08       0
Bank Sta=132.06,175.05
Exp/Cntr=0.3,0.1

Type RM Length L Ch R = 1 ,76385   ,236.46,276.56,298.84
BEGIN DESCRIPTION:
76307.08
END DESCRIPTION:
XS GIS Cut Line= 4
  914021.9110731   809390.119825  914109.4115164  809419.8076035
  914184.4108723  809436.9942944  914267.2236639   809463.557313
#Sta/Elev= 30
       0 2028.17    7.65 2018.16   16.27 2008.85   23.85 1998.01   33.77 1981.95
   36.14 1979.27   42.44  1978.1   46.56 1978.46   49.96 1978.26   59.21 1978.09
    68.1 1976.09   75.54 1969.47   82.73 1965.01   85.47 1965.35   88.02 1965.96
  103.13 1966.45  111.84 1966.54  116.81 1967.29  130.06  1962.6  134.82 1960.92
  144.73 1959.65  149.07 1960.04  154.25 1960.19  162.87 1960.96  167.57 1964.25
  171.22 1965.57   205.1 1975.46  208.43 1976.57  245.41  1995.1  256.31 2001.29
#Mann= 3 , 0 , 0
       0     .07       0  130.06     .05       0  167.57     .08       0
Bank Sta=130.06,167.57
Exp/Cntr=0.3,0.1