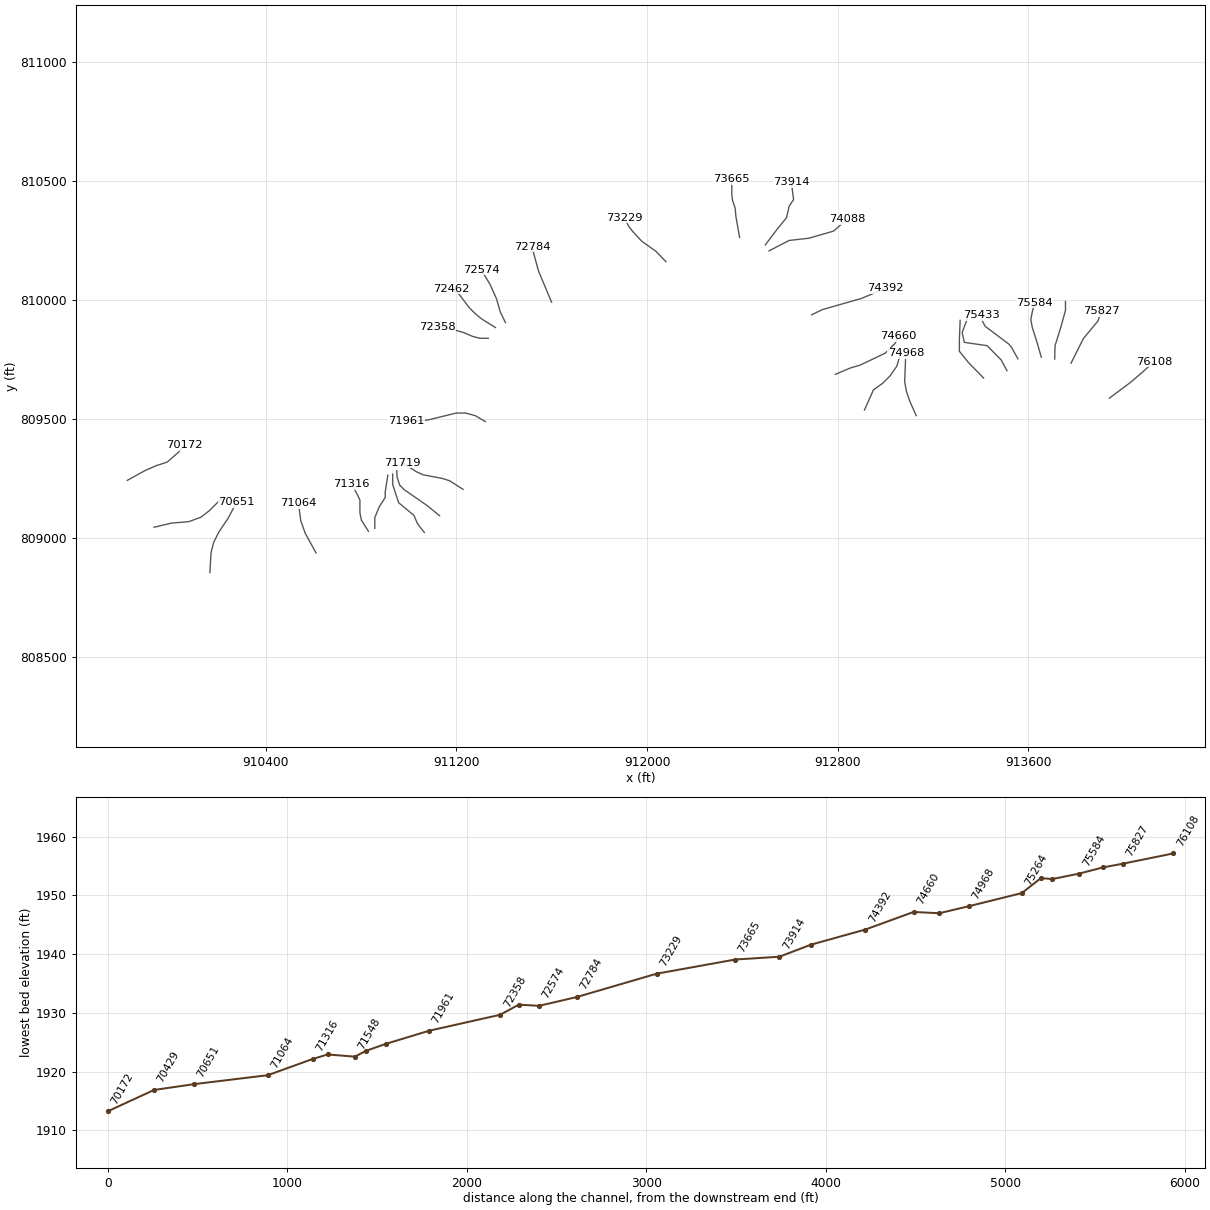
HEC-RAS study lds_big_laurel_crk.prj: lds_big_laurel_crk

--- lds_big_laurel_crk.g20 (geometry) --- (continued)

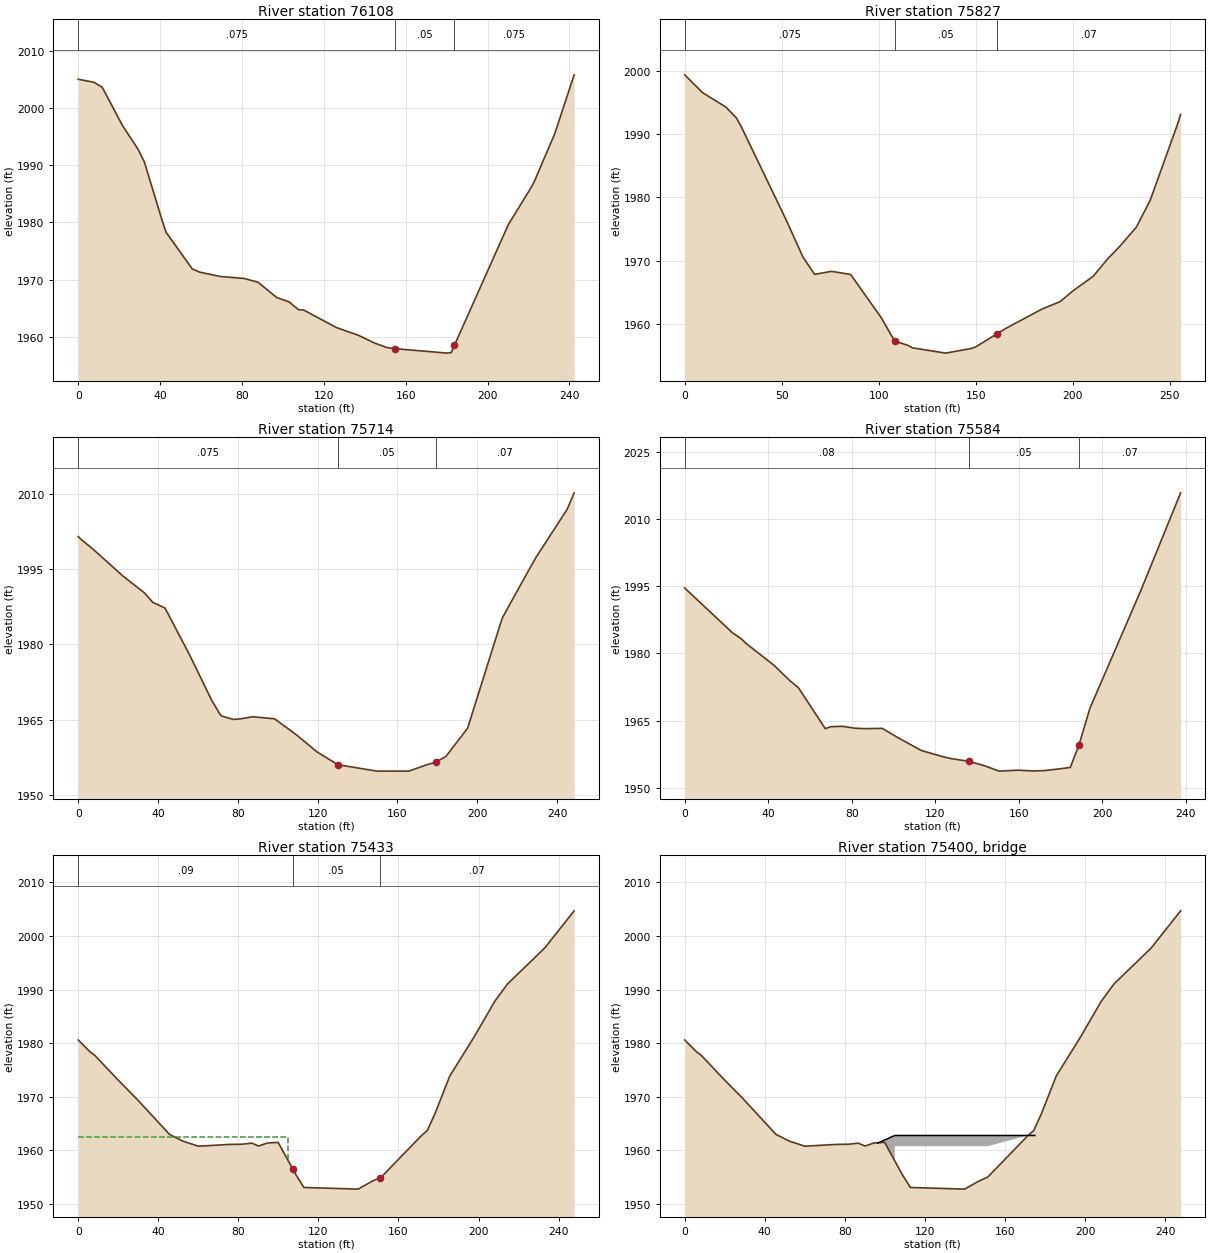
Type RM Length L Ch R = 1 ,76108   ,242.77,281.12,288.79
BEGIN DESCRIPTION:
76030.53
END DESCRIPTION:
XS GIS Cut Line= 4
  913940.6611735  809588.5569222  914026.5987248  809652.6201309
   914078.160846  809696.3698405  914128.1610994  809741.6824421
#Sta/Elev= 30
       0 2005.03    7.65  2004.5   11.72 2003.63   21.61 1996.95   29.17 1992.83
   32.28 1990.61   40.99 1980.36   42.95 1978.27   55.69 1971.89   59.27 1971.32
   69.54 1970.55   81.01 1970.21   87.85 1969.55   97.03 1966.87  102.97 1966.12
  107.69 1964.74   110.1  1964.7  126.14 1961.63  136.99 1960.26  144.62 1958.94
  150.81 1958.14  154.63 1957.94  180.49 1957.16  182.26 1957.26  183.761958.494
  210.16 1979.64  221.32 1986.13  222.84 1987.16   232.8  1995.5  242.29  2005.8
#Mann= 3 , 0 , 0
       0    .075       0  154.63     .05       0  183.76    .075       0
Bank Sta=154.63,183.76
Exp/Cntr=0.3,0.1

Type RM Length L Ch R = 1 ,75827   ,96.57,113.63,145.34
BEGIN DESCRIPTION:
75749.41
END DESCRIPTION:
XS GIS Cut Line= 5
  913779.7232421  809735.4318983  913804.7233687  809785.4321517
  913831.2863874  809838.5571648  913892.2238121  809911.9946529
  913907.8486352  809954.1824947
#Sta/Elev= 30
       0 1999.35    9.22 1996.54   21.25 1994.26   26.71 1992.53   29.18 1991.16
   52.15 1976.56      61 1970.57   67.01 1967.84   75.66 1968.32   85.58 1967.83
  101.56 1960.91  106.82 1958.07  108.49 1957.31   115.3 1956.61  117.38 1956.25
  134.52 1955.41  147.62 1956.13  149.98 1956.38  160.85 1958.43  166.11  1959.4
  184.33 1962.38   193.6 1963.54  200.23 1965.25  210.62 1967.53  218.24 1970.34
  223.95 1972.14  232.91 1975.31  240.07 1979.57  253.65 1991.15  255.71 1993.08
#Mann= 3 , 0 , 0
       0    .075       0  108.49     .05       0  160.85     .07       0
Bank Sta=108.49,160.85
Exp/Cntr=0.3,0.1

Type RM Length L Ch R = 1 ,75714   ,72.58,130.08,137.76
BEGIN DESCRIPTION:
75635.78
END DESCRIPTION:
XS GIS Cut Line= 5
  913710.9734058  809752.6196135  913712.5362978  809808.8693864
  913735.9735325  809883.8697664  913756.2860074  809957.3072545
  913756.2860074  809994.8074445
#Sta/Elev= 30
       0 2001.44    2.02 2000.67    7.28 1998.98   22.44 1993.58    33.1 1990.26
   37.38 1988.35   43.51 1987.21   55.63 1978.04   67.08 1968.72   71.39 1965.88
   72.39 1965.67   77.83 1965.04   81.73 1965.19   87.43 1965.59   98.42 1965.17
  109.32    1962   119.6 1958.61   130.1 1956.04  149.73 1954.76  165.68 1954.76
   174.4 1955.99   179.2 1956.54  184.32  1957.7  195.16 1963.31  211.04 1983.39
  212.53 1985.21  218.45 1989.51  229.22 1997.17  245.05 2006.87  248.54 2010.14
#Mann= 3 , 0 , 0
       0    .075       0   130.1     .05       0   179.2     .07       0
Bank Sta=130.1,179.2
Exp/Cntr=0.3,0.1

Type RM Length L Ch R = 1 ,75584   ,101.7,150.52,205.55
BEGIN DESCRIPTION:
75505.70
END DESCRIPTION:
XS GIS Cut Line= 6
  913654.7236328   809760.432025  913635.9740499  809826.0571015
  913617.2234428  809883.8697664  913610.9739233  809918.2451966
   913615.661575  809944.8071911  913626.5987464  809990.1197927
#Sta/Elev= 28
       0 1994.62   22.93 1984.62      27 1983.33    29.5 1982.22   42.78 1977.36
   50.14 1974.04   54.47 1972.36   67.37  1963.2   69.85 1963.63   75.54 1963.74
   81.46 1963.31    86.2 1963.21   94.65 1963.27  101.95 1961.25  113.36 1958.33
  123.01 1957.03  127.82  1956.5  135.98 1955.93  143.69 1954.92  150.56 1953.72
  159.75 1953.93  166.62 1953.76  172.47 1953.84  184.71 1954.53  188.84 1959.53
  194.13 1967.79  218.45 1994.01  237.55 2015.89
#Mann= 3 , 0 , 0
       0     .08       0  135.98     .05       0  188.84     .07       0
Bank Sta=135.98,188.84
Exp/Cntr=0.5,0.3

Type RM Length L Ch R = 1 ,75433   ,67.33,62.85,115.28
BEGIN DESCRIPTION:
75355.17
END DESCRIPTION:
XS GIS Cut Line= 6
   913556.425306   809753.765666  913530.3528675  809800.8644298
  913519.4187686  809814.7420093  913418.9133434  809890.4367804
  913403.7739795  809919.4526997  913402.0922831  809936.6946961
#Sta/Elev= 30
       0 1980.62    5.99 1978.38    8.36 1977.73    19.3 1973.39   29.27 1969.61
    45.6 1963.01   52.21 1961.76   60.02  1960.8   75.65 1961.13   82.03 1961.17
   86.71 1961.37    90.1 1960.83   94.46 1961.39   99.88 1961.51  107.16 1956.57
  108.93 1955.37  112.77  1953.1  139.87 1952.79  146.91 1954.28  150.62  1954.9
  151.32    1955  171.54  1962.8  174.39 1963.71  178.29 1966.92  185.63 1973.89
  197.67 1981.11  208.18 1987.87  214.54 1991.09  233.03 1997.76  247.77 2004.71
#Mann= 3 , 0 , 0
       0     .09       0  107.16     .05       0  150.62     .07       0
#XS Ineff= 2 , 0
       0     105  1962.5               0
Permanent Ineff=
       F       F
Bank Sta=107.16,150.62
Exp/Cntr=0.5,0.3

Type RM Length L Ch R = 3 ,75400   ,,,
BEGIN DESCRIPTION:
75321  FBSTR_1277  No Photo
END DESCRIPTION:
Bridge Culvert--1,0,-1,-1, 0
Deck Dist Width WeirC Skew NumUp NumDn MinLoCord MaxHiCord MaxSubmerge Is_Ogee
18,32,2.6,0, 4, 5, , , 0.95, 0, 0,0,,
   96.46     105     140     175
 1961.39  1962.8  1962.8  1962.8
          1960.8  1960.8  1960.8
   70.13     106     141     176  184.31
 1961.35  1962.8  1962.8  1962.8 1960.78
          1960.8  1960.8  1960.8
BR Coef=-1 , 0 , 0 ,, 0 ,,,0.8,0,,0,
WSPro=,,,, 1 ,,,, 0 ,,,, 0 ,,,,-1 ,-1 ,-1 , 0 , 0 , 0 , 0 , 0
BC Design=,, 0 ,, 0 ,,,,,,

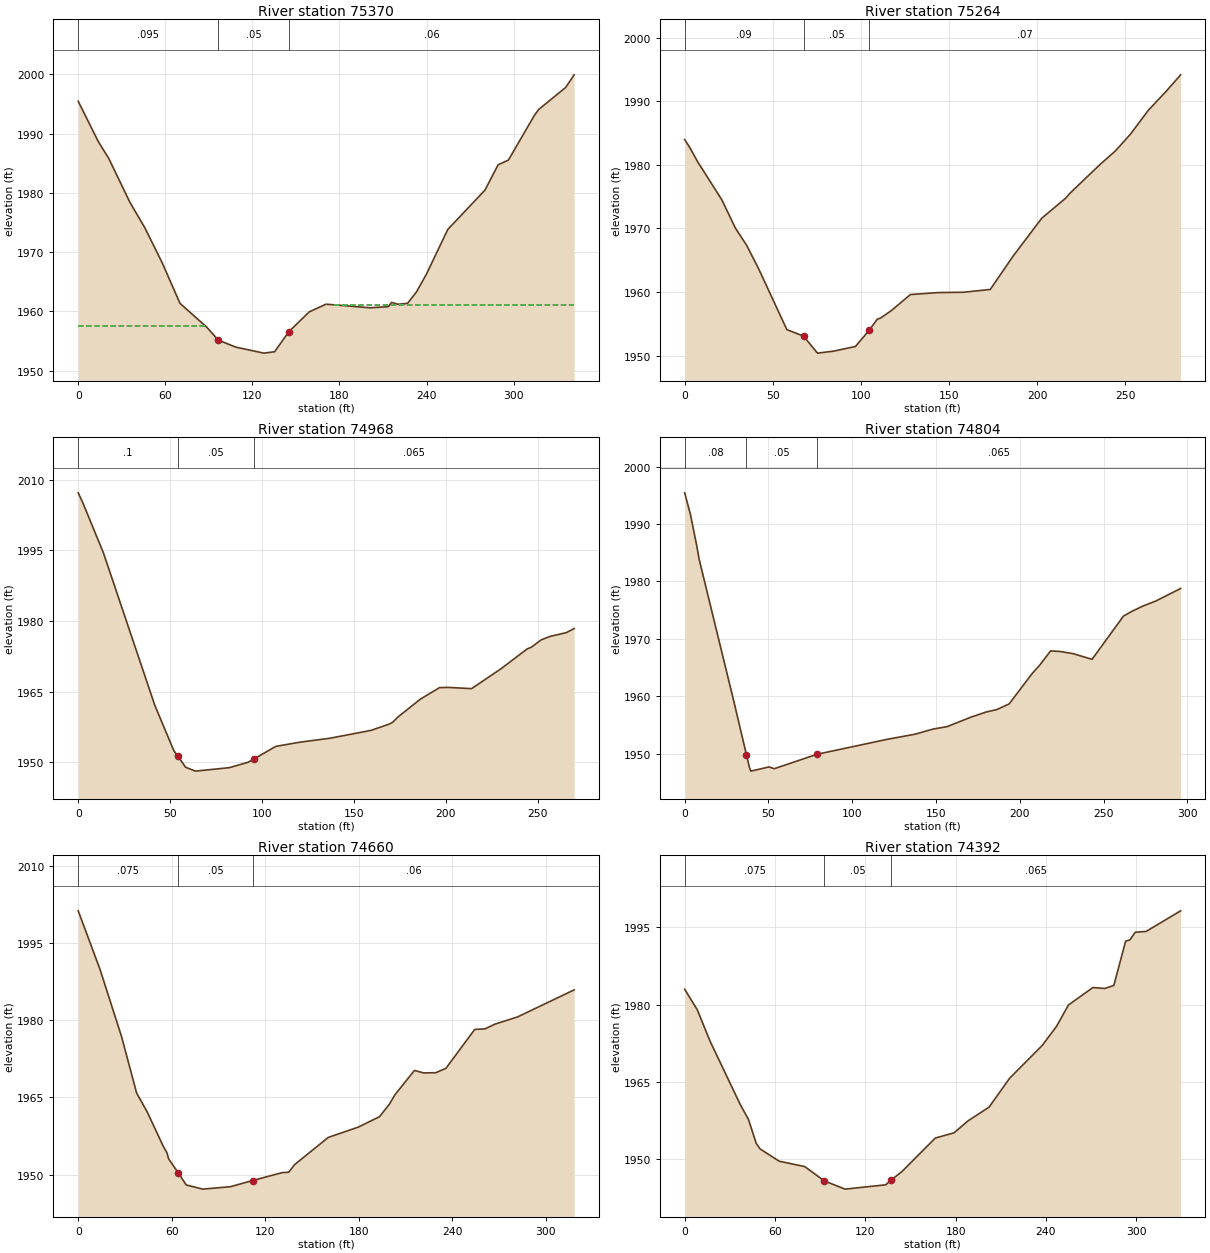
Type RM Length L Ch R = 1 ,75370   ,109.15,106.68,20.85
BEGIN DESCRIPTION:
75292.33
END DESCRIPTION:
XS GIS Cut Line= 6
  913510.5883265  809703.7223972  913486.6185205  809748.7185285
  913427.3238735  809808.8540237  913331.8645614  809822.7316033
   913322.612159  809863.5224695  913345.3212048  809924.9197491
#Sta/Elev= 30
       0 1995.46   13.83 1988.66   21.07  1985.8   35.59 1978.42    45.9 1974.11
   58.07  1968.1   70.13 1961.35   88.67 1957.31   96.49 1955.15  108.68 1953.96
   127.9 1952.95  135.32 1953.18  145.19 1956.58  159.24 1959.92  170.76 1961.21
  201.08  1960.6  213.69 1960.79  215.92 1961.51  220.44  1961.2  226.93 1961.35
   233.1 1963.28  240.07 1966.34  254.68 1973.83  280.31 1980.47  289.32 1984.73
  296.45 1985.54  314.43 1993.11   317.3 1994.07   335.9 1997.79  341.74 1999.92
#Mann= 3 , 0 , 0
       0    .095       0   96.49     .05       0  145.19     .06       0
#XS Ineff= 2 , 0
       0   87.35  1957.6     176       0 1961.14
Permanent Ineff=
       F       F
Bank Sta=96.49,145.19
Exp/Cntr=0.5,0.3

Type RM Length L Ch R = 1 ,75264   ,314.14,295.17,241.64
BEGIN DESCRIPTION:
75185.65
END DESCRIPTION:
XS GIS Cut Line= 6
  913412.5358018  809672.9326058  913348.4736173  809738.5576823
  913329.7240344   809761.994917  913310.9734273  809785.4321517
  913310.9734273   809835.432405  913314.0981871  809915.1194127
#Sta/Elev= 30
       0 1983.98    2.58 1982.88     7.4 1980.48   21.12 1974.49   28.83 1970.04
   35.27 1967.31   42.22 1963.52   57.99  1954.1   67.47 1953.07   75.39  1950.4
   84.45 1950.71   96.88 1951.44  104.73 1953.99  109.34 1955.74  111.23 1955.92
  117.31 1957.09  128.11 1959.61  143.71 1959.92  158.08 1959.97  173.44 1960.41
  186.43 1965.66  202.66 1971.61  216.32 1974.78  218.49 1975.49  235.85 1980.09
  244.45 1982.19  252.95 1984.81  263.15 1988.58  273.52 1991.64  281.49 1994.16
#Mann= 3 , 0 , 0
       0     .09       0   67.47     .05       0  104.73     .07       0
Bank Sta=67.47,104.73
Exp/Cntr=0.3,0.1

Type RM Length L Ch R = 1 ,74968   ,205.85,164.27,31.51
BEGIN DESCRIPTION:
74890.49
END DESCRIPTION:
XS GIS Cut Line= 5
  913129.7240452  809515.1194342  913103.1610265  809574.4949911
  913089.0980712  809615.1199409  913081.2856596  809657.3067585
  913085.9733114  809776.0568481
#Sta/Elev= 30
       0  2007.2    2.42 2005.17   13.71 1994.47   41.72 1962.07      52 1952.52
   54.281951.266   58.42 1948.99   63.74 1948.16   82.28  1948.9   92.32 1950.03
   95.37 1950.68  107.46 1953.41  120.45 1954.29  136.83 1955.13  157.12 1956.64
  159.47 1956.83  169.22 1958.14  171.11 1958.54  173.86 1959.63  186.24 1963.46
  196.57 1965.88  201.22 1965.92  213.98 1965.66  230.01 1969.88   244.3 1974.11
  246.43 1974.42  251.75 1975.99  256.77 1976.75  265.45 1977.53  269.78 1978.41
#Mann= 3 , 0 , 0
       0      .1       0   54.28     .05       0   95.37    .065       0
Bank Sta=54.28,95.37
Exp/Cntr=0.3,0.1

Type RM Length L Ch R = 1 ,74804   ,176.07,143.65,76.19
BEGIN DESCRIPTION:
74726.21
END DESCRIPTION:
XS GIS Cut Line= 6
  912912.5363408  809538.5576931  912950.0365309  809622.9323525
  912989.0985887  809651.0572389  913020.3482349  809682.3068852
  913048.4731214   809722.931835  913065.6608365  809782.3073919
#Sta/Elev= 30
       0 1995.44    3.43 1991.69    7.16  1986.3    8.64 1983.86   29.43 1959.01
   36.831949.856   38.66  1947.6   39.49 1946.97   50.32  1947.7   53.44 1947.39
    78.9  1949.9  120.68  1952.5  137.29 1953.39   148.5 1954.31   156.5 1954.71
  170.86 1956.37  180.09 1957.28  186.28 1957.69  193.64 1958.68  207.52 1964.03
  211.93 1965.45  218.38 1967.91  224.22  1967.8  231.95 1967.42  243.09 1966.44
  261.87 1973.98  267.21 1974.85   273.6 1975.74  281.19  1976.6  295.95 1978.78
#Mann= 3 , 0 , 0
       0     .08       0   36.83     .05       0    78.9    .065       0
Bank Sta=36.83,78.9
Exp/Cntr=0.3,0.1

Type RM Length L Ch R = 1 ,74660   ,272.71,268.09,254.7
BEGIN DESCRIPTION:
74582.57
END DESCRIPTION:
XS GIS Cut Line= 6
  912790.6614914   809688.557429  912853.1607839  809715.1194234
  912895.3486257  809727.6194868    913000.03576  809777.6197401
  913042.2236018  809819.8075819  913054.7236652  809847.9324684
#Sta/Elev= 30
       0  2001.3   14.04 1989.88   27.84 1976.83   37.51 1965.86   44.27 1962.21
    54.7 1955.45   56.96 1954.26   58.05 1953.07   64.35  1950.3   69.36 1947.99
   79.93 1947.18   97.72 1947.65  111.91 1948.85  130.82 1950.38  135.14 1950.47
  138.92 1951.95  160.51 1957.23   179.8 1959.24  193.44 1961.27  199.75 1963.69
  203.28  1965.5  215.84 1970.26   221.7 1969.78  229.64 1969.82  236.12 1970.69
  254.52 1978.23  261.16 1978.35  267.58 1979.27  281.85 1980.64  318.38 1985.93
#Mann= 3 , 0 , 0
       0    .075       0   64.35     .05       0  111.91     .06       0
Bank Sta=64.35,111.91
Exp/Cntr=0.3,0.1

Type RM Length L Ch R = 1 ,74392   ,325.54,304.29,311.15
BEGIN DESCRIPTION:
74314.48
END DESCRIPTION:
XS GIS Cut Line= 4
  912690.6609847  809938.5576715  912735.9735863  809960.4320142
  912900.0362775  810007.3075078    913000.03576  810049.4943254
#Sta/Elev= 30
       0    1983    8.38 1979.02    16.9 1972.89   37.01 1960.57   42.34 1957.75
   47.53 1953.09   50.09    1952    62.8 1949.61   79.76 1948.57   92.81 1945.78
  106.57 1944.19   133.6 1945.03  137.38 1946.02  144.14 1947.55  166.51 1954.11
     179 1955.13  188.21 1957.44  202.21 1960.11  215.86 1965.71  237.59 1972.11
  247.03 1975.79  254.98 1979.95  271.17 1983.33  279.18 1983.16  285.11 1983.75
  292.95 1992.33  295.79 1992.59  299.32 1994.07  306.56 1994.23  329.48 1998.23
#Mann= 3 , 0 , 0
       0    .075       0   92.81     .05       0  137.38    .065       0
Bank Sta=92.81,137.38
Exp/Cntr=0.3,0.1

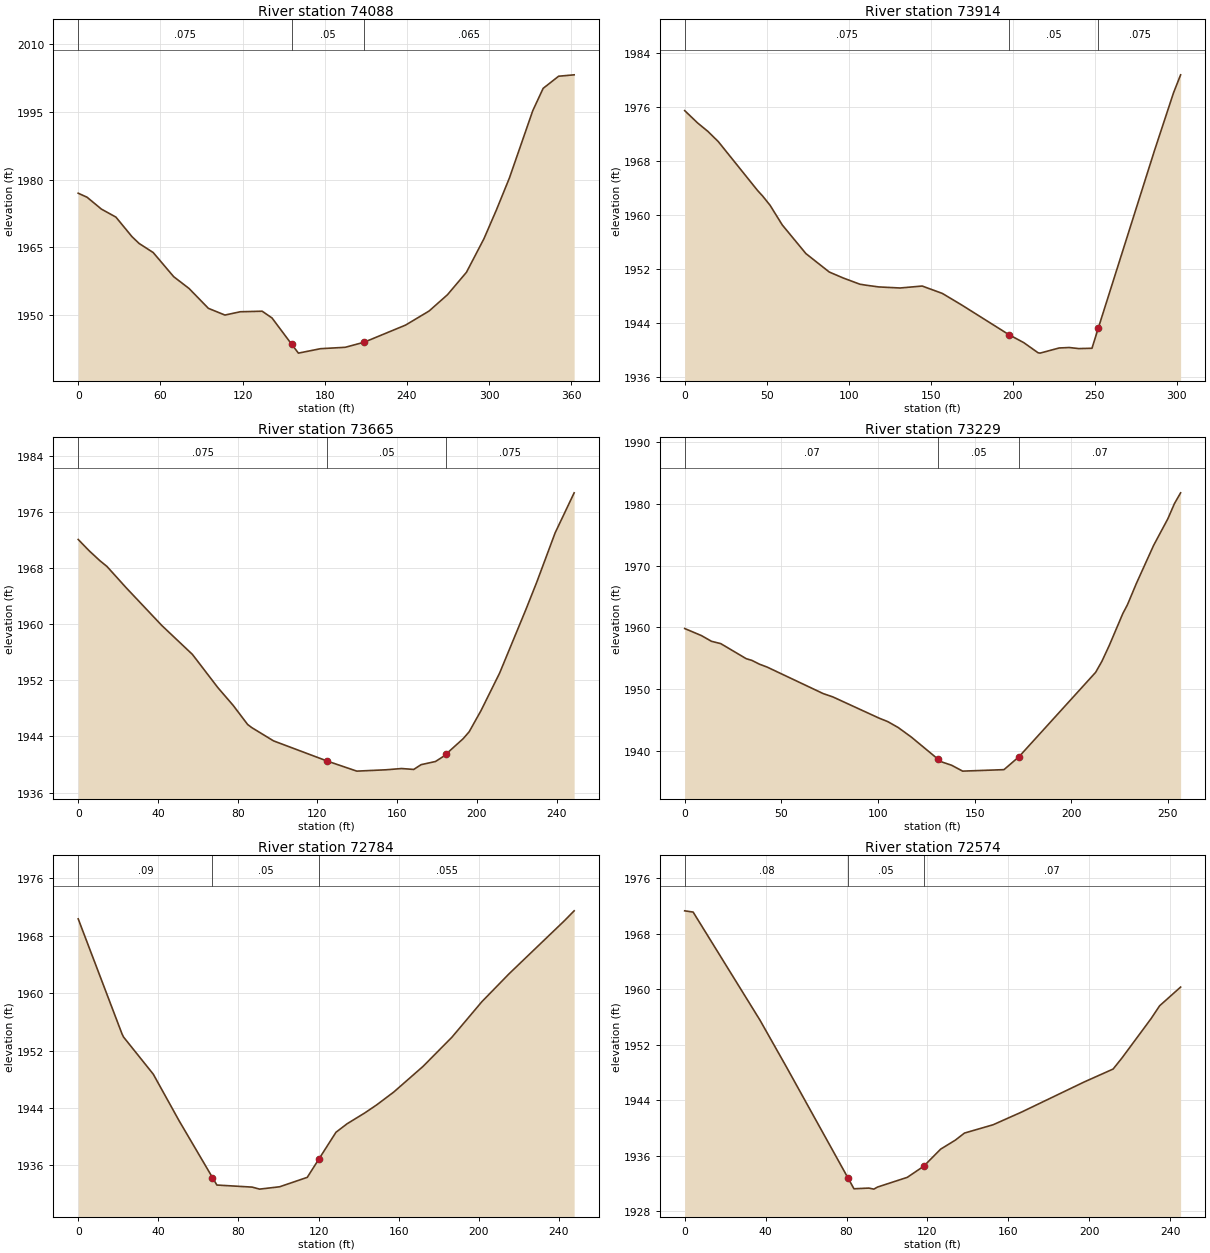
Type RM Length L Ch R = 1 ,74088   ,58.93,174.42,264.08
BEGIN DESCRIPTION:
74010.19
END DESCRIPTION:
XS GIS Cut Line= 5
  912511.9013735  810207.0821784  912596.2760329  810250.8329122
  912679.0888245  810260.2071915   912782.214091    810289.89497
  912840.0267559  810339.8952233
#Sta/Elev= 30
       0 1976.97    6.45 1976.09   16.92 1973.46   27.52 1971.69   39.31 1967.35
   44.51 1965.85   54.76 1963.85   69.71 1958.51   80.94  1955.9   95.04 1951.51
  107.13 1950.02  118.33 1950.75  134.33 1950.87  141.51 1949.38  155.741943.609
  160.79  1941.6  176.93 1942.58  195.01 1942.89  208.84 1944.02   239.1 1947.81
  256.23 1950.92  269.64 1954.52  283.49 1959.48  296.29 1966.92  305.33 1973.25
  314.88 1980.36  331.92 1995.23   339.5 2000.17   350.8 2002.85  362.13 2003.16
#Mann= 3 , 0 , 0
       0    .075       0  155.74     .05       0  208.84    .065       0
Bank Sta=155.74,208.84
Exp/Cntr=0.3,0.1

Type RM Length L Ch R = 1 ,73914   ,163.13,248.31,253.66
BEGIN DESCRIPTION:
73835.76
END DESCRIPTION:
XS GIS Cut Line= 6
  912496.2765504  810232.0823051  912549.4015635  810302.3950333
  912585.3388615  810346.1447429  912596.2760329  810394.5831285
    912615.02664  810422.7080149  912605.6513364   810496.145503
#Sta/Elev= 30
       0 1975.42    7.95 1973.58   14.09 1972.36   20.48 1970.84   44.45  1963.6
   47.55 1962.78   52.07 1961.41   59.46 1958.52   73.87 1954.28   88.13 1951.55
   96.61 1950.67   106.8 1949.75  110.38 1949.61  118.18 1949.35  131.27 1949.19
  144.74 1949.48  157.01 1948.39  168.55 1946.72  197.53  1942.3  206.66 1941.11
  215.33 1939.62   216.6 1939.56   228.2 1940.32  234.37 1940.39  240.19 1940.23
  248.22 1940.28  252.181943.347  286.31 1969.51  297.94 1978.07  302.24 1980.71
#Mann= 3 , 0 , 0
       0    .075       0  197.53     .05       0  252.18    .075       0
Bank Sta=197.53,252.18
Exp/Cntr=0.3,0.1

Type RM Length L Ch R = 1 ,73665   ,366.73,436.46,474.39
BEGIN DESCRIPTION:
73587.46
END DESCRIPTION:
XS GIS Cut Line= 6
  912388.4636321  810263.3329755   912372.838809  810352.3952867
  912369.7140492  810386.7696927  912358.7758536   810419.582231
  912355.6510939  810444.5823577  912355.6510939  810508.6455663
#Sta/Elev= 29
       0 1972.05     5.5 1970.44   10.78 1969.05   14.42 1968.21   24.05 1965.18
   41.95  1959.8   57.31 1955.68   70.02 1950.97   77.79 1948.41   84.99 1945.71
   87.04 1945.27   97.96 1943.38  124.94  1940.5  139.74 1939.07   154.4 1939.26
  162.22 1939.44  168.31 1939.31  171.99 1939.99  179.22 1940.44  183.39  1941.2
  184.72 1941.54  193.08 1943.68  196.11 1944.67  202.03 1947.67  211.41 1953.04
  224.59 1962.09  230.06    1966  239.24 1972.99  248.78 1978.69
#Mann= 3 , 0 , 0
       0    .075       0  124.94     .05       0  184.72    .075       0
Bank Sta=124.94,184.72
Exp/Cntr=0.3,0.1

Type RM Length L Ch R = 1 ,73229   ,488.27,445.16,421.63
BEGIN DESCRIPTION:
73151
END DESCRIPTION:
XS GIS Cut Line= 6
  912079.0888568   810161.770601   912036.901015  810205.5203106
  911977.5264823  810247.7071282  911940.0262923  810288.3331022
  911922.8385772  810310.2074449   911905.650862  810346.1447429
#Sta/Elev= 30
       0 1959.79     8.7 1958.64   13.85 1957.72   18.67 1957.34   31.83  1954.9
   34.79 1954.62   38.73    1954    42.7 1953.53   71.63 1949.24   76.64  1948.7
  100.61 1945.25  105.01  1944.7  110.43 1943.74  117.26 1942.18  131.22 1938.56
  133.19 1938.13  138.12 1937.61   143.8 1936.66  165.18  1936.9  172.96    1939
  212.59 1952.68  215.85 1954.48  219.67 1957.06  226.65 1962.21  229.07 1963.66
   233.7 1967.12   242.6 1973.28  249.97  1977.6  253.36 1980.05  256.56  1981.8
#Mann= 3 , 0 , 0
       0     .07       0  131.22     .05       0  172.96     .07       0
Bank Sta=131.22,172.96
Exp/Cntr=0.3,0.1

Type RM Length L Ch R = 1 ,72784   ,219.32,209.77,219.32
BEGIN DESCRIPTION:
72705.83
END DESCRIPTION:
XS GIS Cut Line= 4
  911599.4008465   809991.457366   911574.401744  810050.8329229
  911544.7139656   810121.144627  911516.5890791  810224.2698935
#Sta/Elev= 23
       0 1970.36   21.86 1954.33   22.65 1953.88    37.5  1948.7   50.32 1942.24
   67.041934.295   69.24 1933.25   86.88 1932.96   90.58 1932.68   100.6 1933.01
  114.36 1934.32  120.13 1936.85  128.72 1940.61  134.25 1941.79  143.08  1943.3
  149.06 1944.43  157.58 1946.22  172.18 1949.79  186.61 1953.86  201.56 1958.81
  215.17 1962.71  242.82 1970.11  247.64 1971.48
#Mann= 3 , 0 , 0
       0     .09       0   67.04     .05       0  120.13    .055       0
Bank Sta=67.04,120.13
Exp/Cntr=0.3,0.1

Type RM Length L Ch R = 1 ,72574   ,84.79,112.49,133.67
BEGIN DESCRIPTION:
72496.06
END DESCRIPTION:
XS GIS Cut Line= 5
  911405.6514011  809905.5198147  911383.7760342  809950.8324162
   911368.151211  810005.5203214  911340.0263246  810068.0206381
  911304.0890265  810127.3951708
#Sta/Elev= 22
       0 1971.31    4.18 1971.13   37.26 1955.53   50.32 1948.79   80.781932.766
   83.68 1931.24      91 1931.34    93.5 1931.19   95.33 1931.49  110.04 1932.89
  118.15 1934.49   126.5 1936.95  133.82 1938.26  138.28 1939.27  152.46 1940.47
  166.46 1942.29  197.48 1946.64  211.76  1948.5   216.1 1950.08  230.58 1955.79
  234.75 1957.62  245.13 1960.32
#Mann= 3 , 0 , 0
       0     .08       0   80.78     .05       0  118.15     .07       0
Bank Sta=80.78,118.15
Exp/Cntr=0.3,0.1

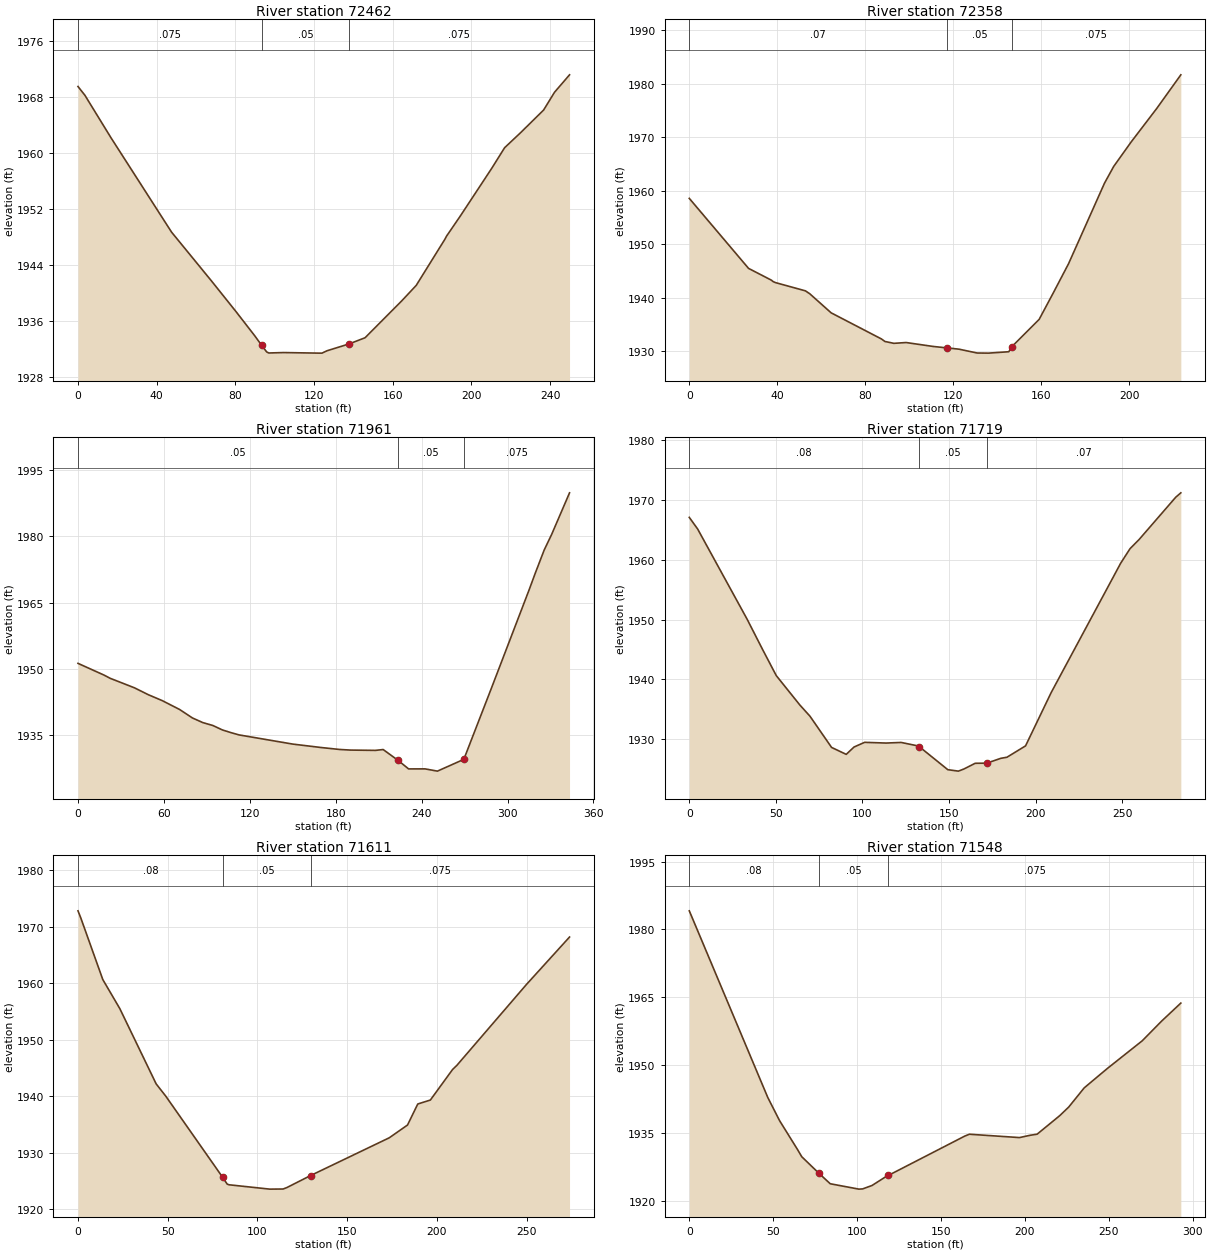
Type RM Length L Ch R = 1 ,72462   ,81.54,103.23,152.88
BEGIN DESCRIPTION:
72383.57
END DESCRIPTION:
XS GIS Cut Line= 6
  911363.4635593  809885.2073398  911305.6508943  809921.1446378
  911279.0888999  809943.0200047  911254.0887732  809968.0201314
  911210.3390636  810025.8327963  911177.5265254   810047.707139
#Sta/Elev= 27
       0  1969.5    3.53 1968.24   16.76 1962.18   47.57 1948.68   68.07 1941.63
   80.55 1937.24   89.83 1933.87    93.31932.525   95.91 1931.56      97 1931.41
   104.4 1931.47   122.5 1931.39  124.01 1931.39  126.59 1931.73  137.84 1932.71
  145.91 1933.59  164.61 1938.88   171.9 1941.07  186.51 1947.68  187.29  1948.1
  194.44 1951.04  210.39 1957.85  216.83 1960.75  225.03 1962.92  236.66 1966.14
   242.2 1968.68  249.83 1971.17
#Mann= 3 , 0 , 0
       0    .075       0    93.3     .05       0  137.84    .075       0
Bank Sta=93.3,137.84
Exp/Cntr=0.3,0.1

Type RM Length L Ch R = 1 ,72358   ,325.51,397.01,415.57
BEGIN DESCRIPTION:
72280.35
END DESCRIPTION:
XS GIS Cut Line= 6
   911333.776805  809839.8947382  911297.8384828  809839.8947382
  911268.1517285  809847.7071497  911227.5267787  809864.8948649
  911141.5892273  809888.3331237  911118.1509685  809888.3331237
#Sta/Elev= 27
       0 1958.59   26.92 1945.51   37.33  1943.3    38.1 1943.04   39.15 1942.85
   52.77 1941.31   54.76 1940.76   64.46  1937.2   87.35 1932.31   88.88 1931.85
   92.96  1931.5   98.53 1931.65  110.75 1930.92  117.02 1930.65  122.53 1930.41
  130.82 1929.69  135.99 1929.67  145.19 1929.93  146.63  1930.9  158.97 1935.97
  165.33 1940.87  172.34 1946.38  188.67 1961.43  192.84 1964.55  200.87 1969.18
  212.33 1975.35  223.36 1981.68
#Mann= 3 , 0 , 0
       0     .07       0  117.02     .05       0  146.63    .075       0
Bank Sta=117.02,146.63
Exp/Cntr=0.3,0.1

Type RM Length L Ch R = 1 ,71961   ,302.02,242.23,213.57
BEGIN DESCRIPTION:
71883.34
END DESCRIPTION:
XS GIS Cut Line= 6
  911321.2767417  809489.8950131  911279.0888999  809514.8951397
  911238.4639501  809525.8323111  911199.4008681  809525.8323111
  911077.5260186  809496.1455568  910990.0265995  809491.4579051
#Sta/Elev= 30
       0 1951.31   18.16 1948.66   22.47 1947.93    39.5 1945.77   49.04 1944.23
   58.74  1942.9   70.97 1940.88   79.93 1938.96   87.13 1937.92   94.17 1937.26
  100.89 1936.25  106.91 1935.64  112.47 1935.13  150.05 1933.05  169.76 1932.28
   182.3 1931.85  190.09  1931.7  207.74 1931.63  213.14 1931.82  223.52 1929.38
  230.89 1927.44  242.36 1927.45  251.02 1926.94  269.46  1929.6  288.58 1945.57
  315.06 1967.93  319.32 1971.67   325.6 1976.95  330.81 1980.47  343.29 1989.87
#Mann= 3 , 0 , 0
       0     .05       0  223.52     .05       0  269.46    .075       0
Bank Sta=223.52,269.46
Exp/Cntr=0.3,0.1

Type RM Length L Ch R = 1 ,71719   ,142.72,107.69,88.07
BEGIN DESCRIPTION:
71641.11
END DESCRIPTION:
XS GIS Cut Line= 6
  911227.5267787  809205.5203644  911171.2759816  809241.4576625
  911141.5892273   809250.832966  911060.3383035  809266.4577891
  911032.2134171  809278.9578525  910971.2759924  809318.0199103
#Sta/Elev= 29
       0 1967.08    4.82 1965.14   33.39 1950.07   42.45 1944.94   50.22 1940.65
   63.86 1935.73    69.7 1933.86   82.16 1928.65   90.61 1927.49   95.15 1928.72
  101.25  1929.5  113.66 1929.38  122.34 1929.48  132.26 1928.89  132.78 1928.78
  149.29 1924.93  155.37 1924.69  158.55 1925.04  165.09    1926   171.8 1926.02
  179.88 1926.83  183.43 1927.01  194.17 1928.91  208.89 1937.77  249.11 1959.43
   254.5 1961.85  259.76 1963.39  280.87 1970.44  283.83 1971.18
#Mann= 3 , 0 , 0
       0     .08       0  132.78     .05       0   171.8     .07       0
Bank Sta=132.78,171.8
Exp/Cntr=0.3,0.1

Type RM Length L Ch R = 1 ,71611   ,86.28,63.07,34.21
BEGIN DESCRIPTION:
71533.42
END DESCRIPTION:
XS GIS Cut Line= 6
   911129.089164  809094.5826864  911077.5260186  809136.7705282
  910980.6512959  809203.9574725   910961.901713  809222.7080795
  910950.9635175  809255.5206178  910949.4016497  809283.6455043
#Sta/Elev= 21
       0  1972.8    1.61  1971.5   13.83 1960.63   23.32 1955.48   43.56 1942.16
   48.89    1940   80.66  1925.6   83.11 1924.43   84.12  1924.3  106.83 1923.53
  114.28 1923.55  116.42 1923.81  129.66 1925.94  173.47 1932.62  183.63 1934.88
  189.34  1938.6  196.35  1939.3  208.74 1944.71  211.15 1945.45  249.84 1959.74
  273.91 1968.16
#Mann= 3 , 0 , 0
       0     .08       0   80.66     .05       0  129.66    .075       0
Bank Sta=80.66,129.66
Exp/Cntr=0.3,0.1

Type RM Length L Ch R = 1 ,71548   ,191.75,151.03,41.16
BEGIN DESCRIPTION:
71470.35
END DESCRIPTION:
XS GIS Cut Line= 6
  911065.0259553  809024.2699581  911036.9010688  809060.2072562
  911021.2762457  809096.1455784  910957.2140612  809149.2705915
  910932.2139345  809225.8328393  910932.2139345  809269.5825489
#Sta/Elev= 24
       0 1984.13   46.79 1942.81   53.81 1937.69   64.53 1931.28   67.04  1929.7
   77.26 1926.04      84 1923.72  101.08 1922.53  103.33 1922.58  108.93 1923.34
  118.53 1925.61  120.88 1925.99  164.25 1934.28  166.94 1934.68   196.8 1933.94
  203.02 1934.44  207.31 1934.69  220.78 1938.79  226.16  1940.7  235.37 1944.94
  249.22 1949.25  269.96 1955.36  281.57 1959.74  292.97 1963.71
#Mann= 3 , 0 , 0
       0     .08       0   77.26     .05       0  118.53    .075       0
Bank Sta=77.26,118.53
Exp/Cntr=0.3,0.1

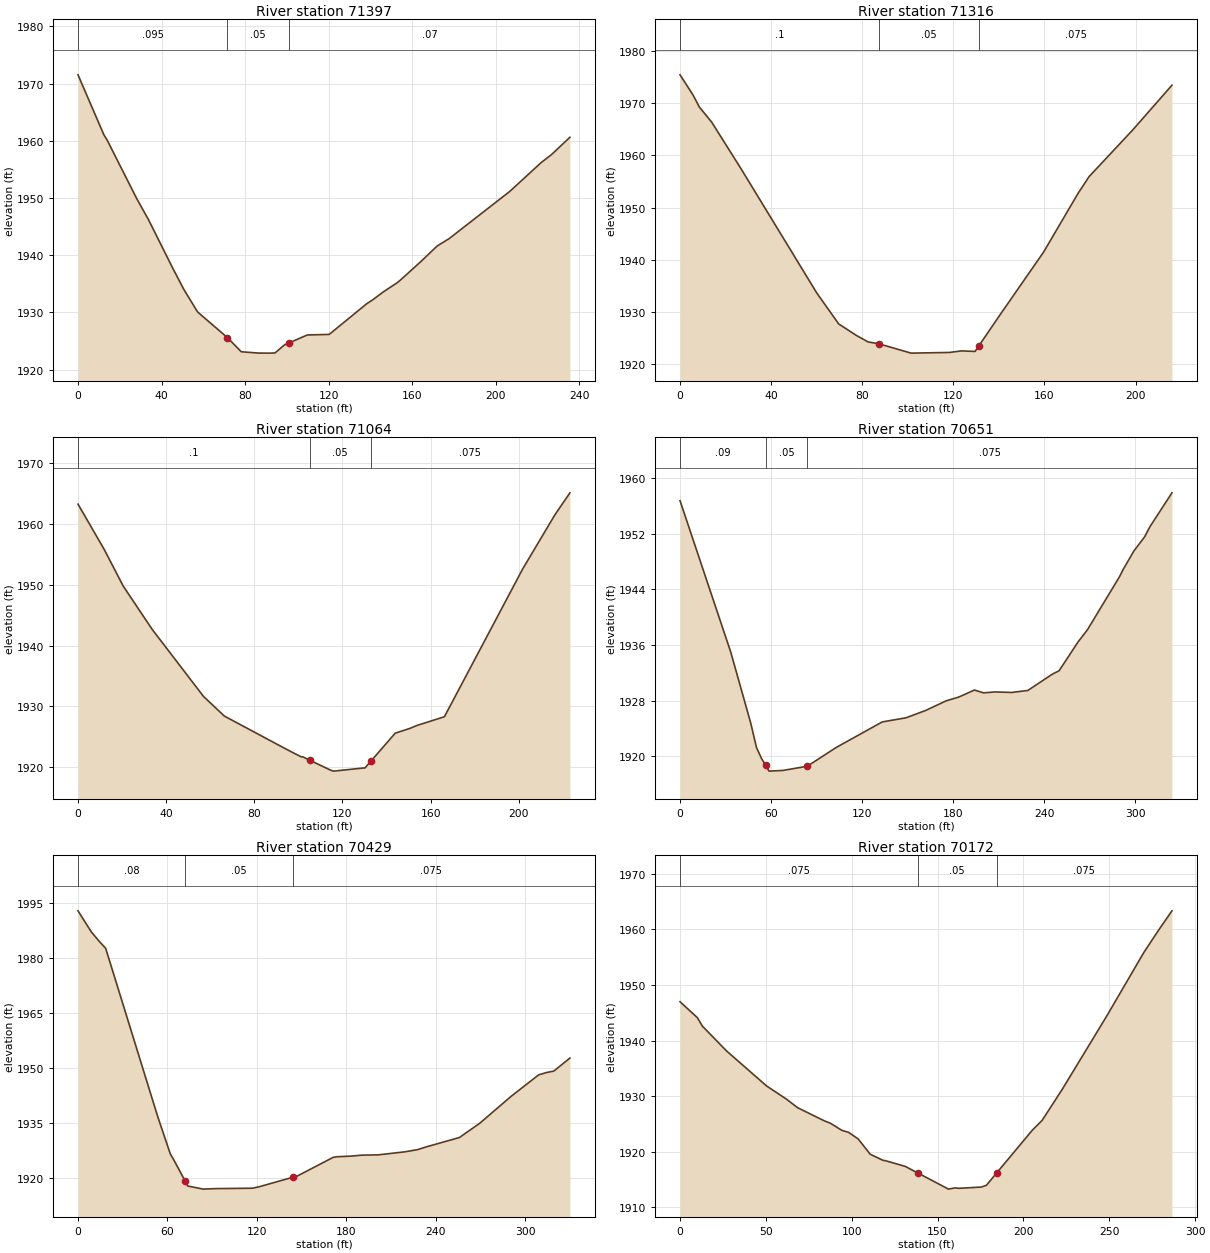
Type RM Length L Ch R = 1 ,71397   ,58.42,81.5,113.7
BEGIN DESCRIPTION:
71319.32
END DESCRIPTION:
XS GIS Cut Line= 6
  910857.2135545  809041.4576732  910857.2135545  809086.7702748
  910875.9641616  809132.0828764  910900.9642883  809171.1449342
  910900.9642883  809194.5821689  910911.9014596  809264.8948972
#Sta/Elev= 29
       0 1971.53   12.39 1961.05   13.91 1960.16   28.16 1949.87    33.7 1946.25
   45.31 1937.78   50.64 1934.05    57.3 1930.08   71.55 1925.61   78.17 1923.14
   86.36 1922.91   92.36  1922.9   94.36 1922.94   98.88 1924.34  100.971924.672
  109.77 1926.07  120.28 1926.17   138.1 1931.49  140.94 1932.17  146.24 1933.61
  152.77 1935.19  154.45 1935.69  164.37 1938.97  171.91  1941.6  177.66  1942.9
  206.71 1951.15  221.63 1956.15  226.74  1957.6  235.53 1960.62
#Mann= 3 , 0 , 0
       0    .095       0   71.55     .05       0  100.97     .07       0
Bank Sta=71.55,100.97
Exp/Cntr=0.3,0.1

Type RM Length L Ch R = 1 ,71316   ,237.49,252.22,258.13
BEGIN DESCRIPTION:
71237.82
END DESCRIPTION:
XS GIS Cut Line= 6
    910830.65156  809028.9576099  910800.9637816  809075.8331035
   910794.714262  809107.0827497   910794.714262  809160.2077629
  910785.3389585  809180.5202378  910760.3388318  809227.3947071
#Sta/Elev= 21
       0 1975.42    5.75 1971.53     8.5 1969.24   13.92 1966.35   26.65 1957.54
   60.07 1933.65   69.66 1927.75   77.48 1925.53   82.57 1924.31   87.35 1923.94
  101.46 1922.16  118.36 1922.29  123.56 1922.59  129.54 1922.48  131.261923.581
   140.4 1929.43  159.63  1941.5  174.81 1952.77  179.62 1955.95  198.76 1964.87
  215.98 1973.43
#Mann= 3 , 0 , 0
       0      .1       0   87.35     .05       0  131.26    .075       0
Bank Sta=87.35,131.26
Exp/Cntr=0.3,0.1

Type RM Length L Ch R = 1 ,71064   ,456.9,412.62,314.09
BEGIN DESCRIPTION:
70985.60
END DESCRIPTION:
XS GIS Cut Line= 4
  910610.3390959  808938.3324067  910565.0264943  809021.1451983
  910546.2758872  809074.2702115  910536.9016079  809146.1448075
#Sta/Elev= 24
       0 1963.26   11.87 1955.83    20.5  1949.8    33.7 1942.65   56.95 1931.65
   66.42 1928.42    94.4    1923   98.49 1922.23  101.44  1921.7  101.91 1921.73
  105.09 1921.18  114.67 1919.52  116.01 1919.37  129.11 1919.87  129.47 1919.89
  130.19 1919.88  132.88    1921  143.95 1925.61  150.74 1926.41  153.83 1926.88
  166.27 1928.31  201.76 1952.59  216.31 1961.45  223.22 1965.12
#Mann= 3 , 0 , 0
       0      .1       0  105.09     .05       0  132.88    .075       0
Bank Sta=105.09,132.88
Exp/Cntr=0.3,0.1

Type RM Length L Ch R = 1 ,70651   ,277.05,221.53,79.59
BEGIN DESCRIPTION:
70572.98
END DESCRIPTION:
XS GIS Cut Line= 6
  910165.0265159  808855.5206393  910169.7141676  808938.3324067
   910180.651339  808982.0831405  910202.5267059  809025.8328501
  910243.1516557  809086.7702748  910277.5260617  809152.3953513
#Sta/Elev= 30
       0 1956.76   33.49 1934.93   46.61 1924.75   50.43 1921.22    53.7 1919.67
   56.34  1918.7    58.7 1917.84    67.9 1917.94   83.95 1918.55  102.76 1921.22
  133.28 1924.92  148.92 1925.51  161.93 1926.57  175.38 1927.95  183.89 1928.51
  194.06 1929.51  200.12  1929.1  207.53 1929.24  218.57 1929.16  229.28 1929.45
  245.55 1931.81  249.88 1932.28  262.38 1936.43   268.6 1938.19  289.64 1945.79
  292.23  1946.9  299.23 1949.53  306.31 1951.57  309.79 1953.02  324.28 1957.89
#Mann= 3 , 0 , 0
       0     .09       0   56.34     .05       0   83.95    .075       0
Bank Sta=56.34,83.95
Exp/Cntr=0.3,0.1

Type RM Length L Ch R = 1 ,70429   ,243.82,256.9,274.66
BEGIN DESCRIPTION:
70351.45
END DESCRIPTION:
XS GIS Cut Line= 6
  909930.6510964   809046.145325  910002.5267166  809063.3330401
  910075.9642047  809069.5825597  910127.5263258  809088.3321426
  910163.4636239  809116.4580533  910221.2762888   809174.269694
#Sta/Elev= 30
       0 1992.97    8.95 1987.19   14.41 1984.55   18.55 1982.72    53.6  1936.5
   61.89 1926.49   64.21 1924.87    71.8 1919.09   73.63  1917.7   84.06 1916.85
   92.15 1916.99  117.03  1917.1  121.22 1917.47  143.92 1920.08  146.43  1920.3
   171.1 1925.54  173.37  1925.7  183.51 1925.89     190 1926.14  201.25 1926.22
  218.96 1927.04   227.7 1927.65  233.13 1928.36  255.74 1930.96  269.41 1934.87
  290.38 1942.21  308.89  1948.1  314.22 1948.75  319.04 1949.13  329.86  1952.7
#Mann= 3 , 0 , 0
       0     .08       0    71.8     .05       0  143.92    .075       0
Bank Sta=71.8,143.92
Exp/Cntr=0.3,0.1

Type RM Length L Ch R = 1 ,70172   ,391.14,376.34,380.67
BEGIN DESCRIPTION:
70094.55
END DESCRIPTION:
XS GIS Cut Line= 6
  909818.1515505  809243.0205545  909894.7137984  809285.2073721
  909941.5892919   809305.519847  909985.3390015  809319.5828023
  910033.7763629  809361.7706441  910057.2135976  809391.4573983
#Sta/Elev= 30
       0 1946.98   10.11 1944.11   13.05 1942.58   27.17  1938.1   50.39 1931.82
   62.08 1929.42   68.53 1927.89   84.33 1925.49   87.64 1925.09   94.25 1923.82
   98.15 1923.46  103.72 1922.28  110.79 1919.51  118.29 1918.41  119.44 1918.37
  131.06 1917.34   138.5 1916.14  156.37 1913.23  160.07 1913.45  162.62 1913.38
  175.43  1913.6  178.46 1913.92  184.46 1916.16  205.12 1923.82  210.87  1925.6
  222.65 1931.22  248.69 1944.49  270.13 1955.85  278.75 1959.88  286.51 1963.36
#Mann= 3 , 0 , 0
       0    .075       0   138.5     .05       0  184.46    .075       0
Bank Sta=138.5,184.46
Exp/Cntr=0.3,0.1