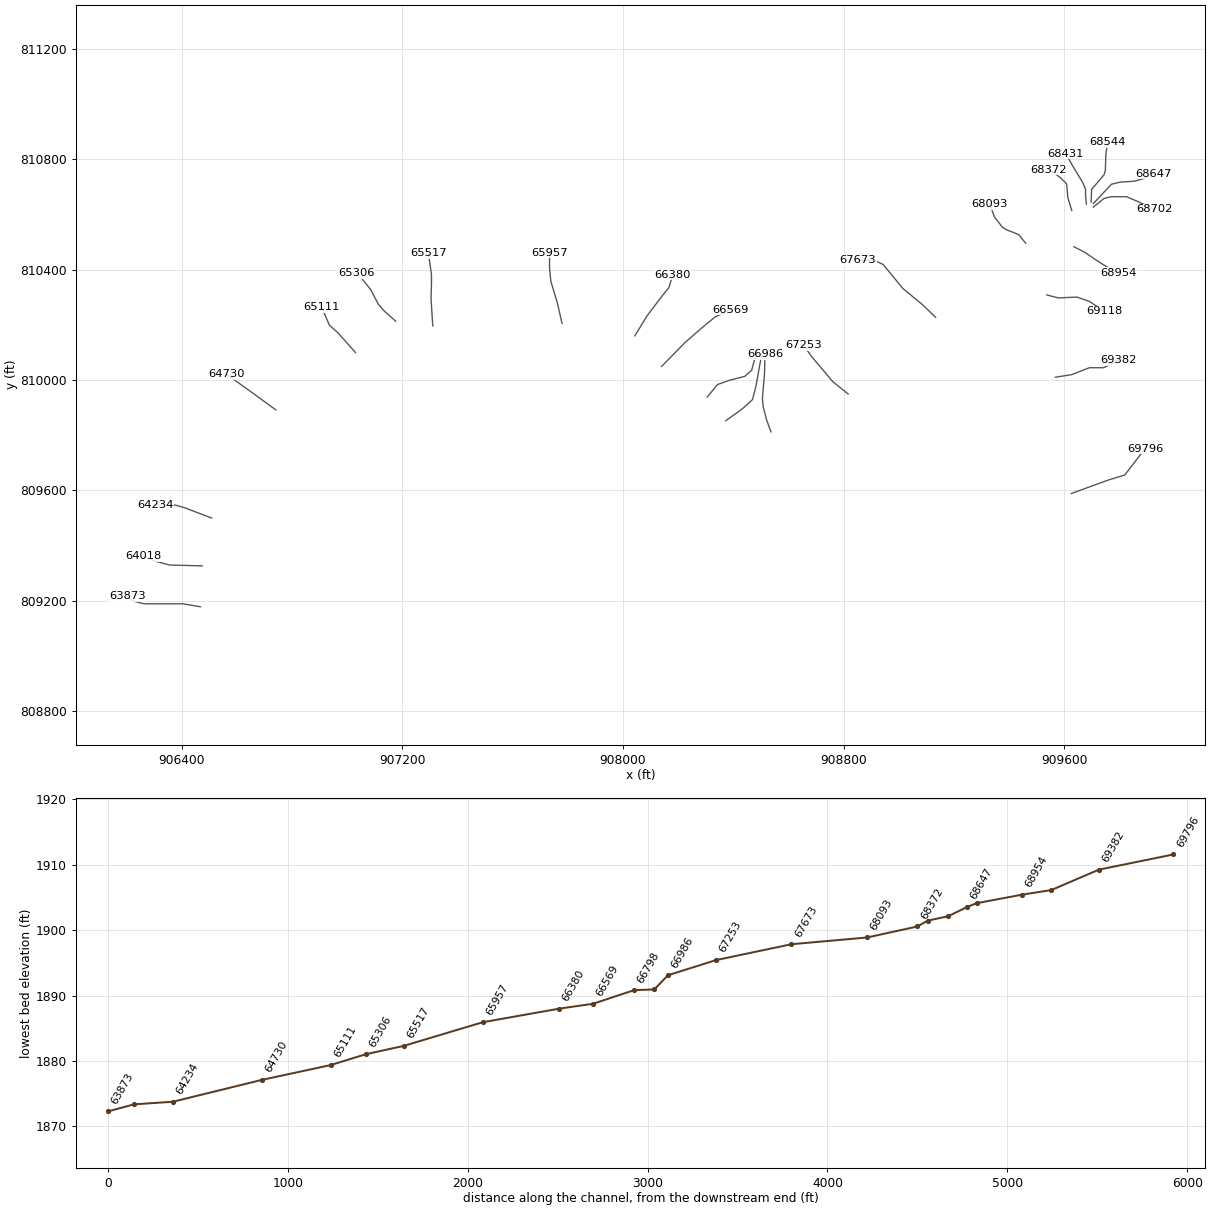
HEC-RAS study lds_big_laurel_crk.prj: lds_big_laurel_crk

--- lds_big_laurel_crk.g20 (geometry) --- (continued)

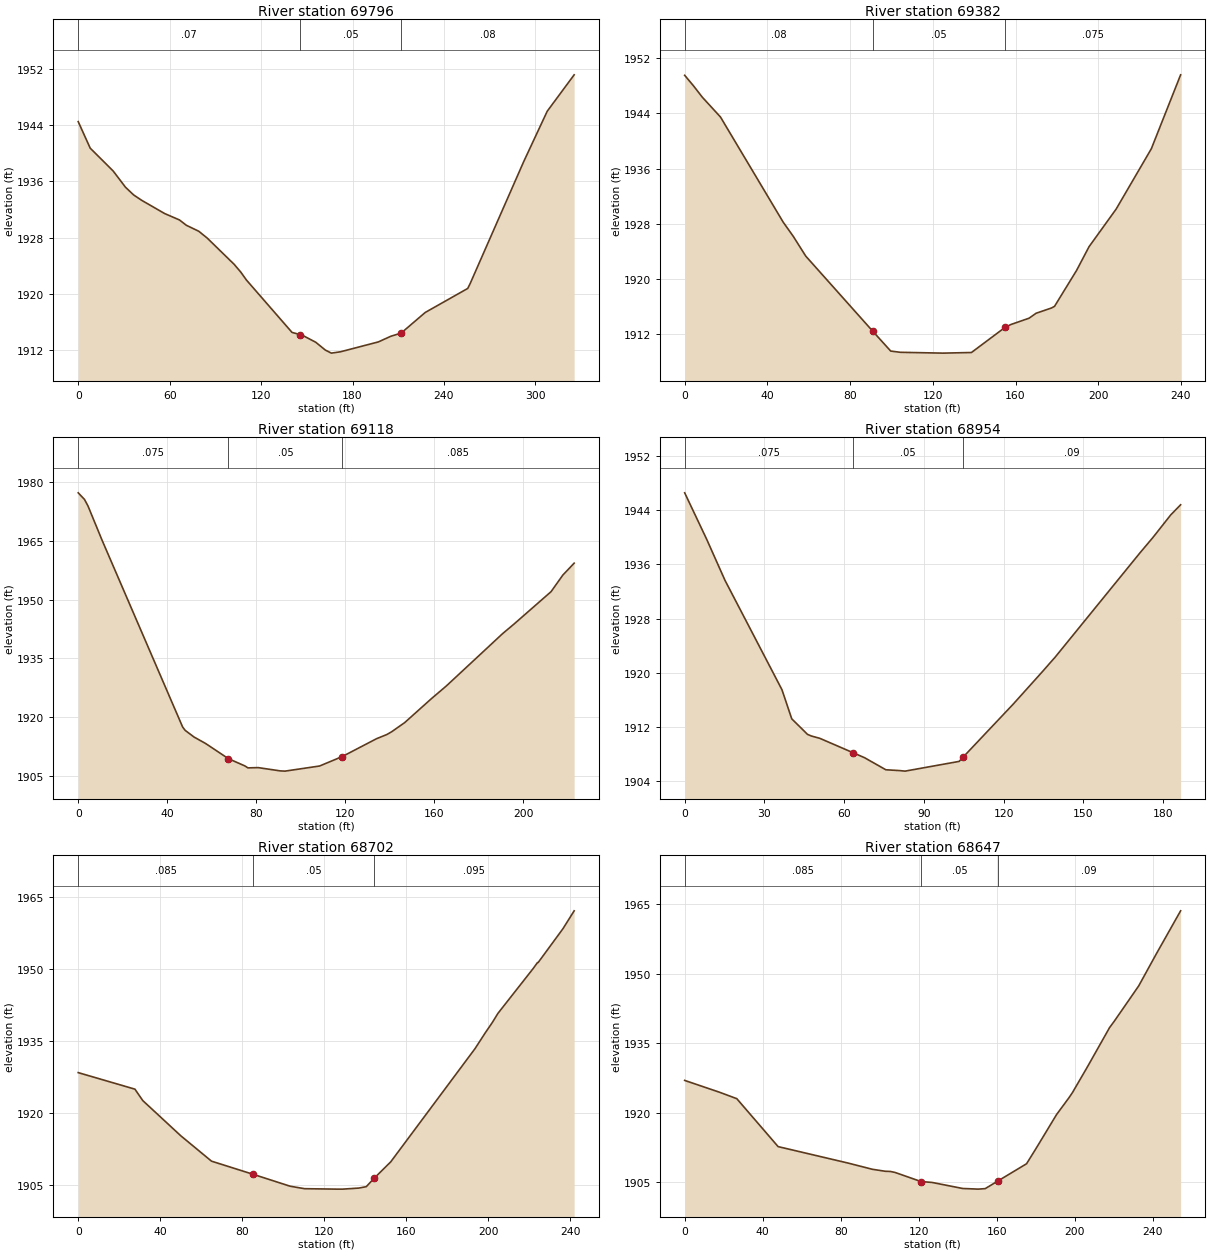
Type RM Length L Ch R = 1 ,69796   ,418.4,414.3,378.44
BEGIN DESCRIPTION:
69718.21
END DESCRIPTION:
XS GIS Cut Line= 4
  909625.9639729  809588.3326278  909758.7759936  809636.7699892
  909819.7134183  809655.5205963  909893.1509064   809750.832427
#Sta/Elev= 30
       0 1944.52    7.87 1940.74   22.93 1937.49   31.06 1935.17   36.38 1934.08
   41.62 1933.32   56.73 1931.43   66.45 1930.52   70.97 1929.76   79.13 1928.91
    84.7 1927.93  102.35  1924.2  106.63 1923.11  110.46 1921.95  140.31 1914.51
  145.35 1914.21  148.13 1913.99  155.86 1913.11   162.2 1911.99  166.13 1911.56
  172.12 1911.75  197.01 1913.16  205.13 1913.96   211.9 1914.41  227.73 1917.35
  255.63 1920.77  257.22 1921.47   292.4 1938.85  307.79    1946  325.45 1951.18
#Mann= 3 , 0 , 0
       0     .07       0  145.35     .05       0   211.9     .08       0
Bank Sta=145.35,211.9
Exp/Cntr=0.3,0.1

Type RM Length L Ch R = 1 ,69382   ,288.24,264.33,244.63
BEGIN DESCRIPTION:
69303.91
END DESCRIPTION:
XS GIS Cut Line= 6
   909568.151308  810010.2079731  909627.5258407  810019.5822525
  909671.2765744  810036.7699676  909691.5890493  810044.5823792
  909743.1511705  810044.5823792  909796.2761837  810071.1453978
#Sta/Elev= 23
       0 1949.51     4.2 1948.01    8.49 1946.35    17.3 1943.47   47.63 1928.23
   52.51 1926.17   58.56  1923.3   90.91 1912.43   99.63 1909.54  104.29 1909.36
  124.91 1909.24  138.68 1909.33  154.88 1912.96  157.77 1913.39  166.53  1914.3
  169.95 1915.02  177.37 1915.78  178.86 1916.02  189.51 1921.22  195.54 1924.66
  208.66 1930.12  225.69 1938.87  239.84 1949.58
#Mann= 3 , 0 , 0
       0     .08       0   90.91     .05       0  154.88    .075       0
Bank Sta=90.91,154.88
Exp/Cntr=0.3,0.1

Type RM Length L Ch R = 1 ,69118   ,194.68,163.8,142.4
BEGIN DESCRIPTION:
69039.58
END DESCRIPTION:
XS GIS Cut Line= 6
  909536.9016617  810308.6455771  909579.0884793  810297.7073816
  909608.7762578  810299.2702735  909646.2764478  810300.8321414
  909691.5890493  810285.2073182  909744.7140625  810249.2700202
#Sta/Elev= 27
       0 1977.33    2.81 1975.65    4.38 1973.99    10.7 1965.24   46.95 1917.39
   48.09 1916.54    52.1 1914.83   57.21 1913.21    67.5 1909.31   74.95 1907.44
   76.29 1906.95   80.89 1907.02   90.83 1906.18   92.95 1906.12   108.5 1907.43
  118.72 1909.86   134.1 1914.42  138.74 1915.49  140.93 1916.21  146.73 1918.53
  158.77 1924.67   165.5 1927.93  190.75  1941.3  195.96 1943.79  212.53 1952.04
  217.82 1956.28  222.91 1959.33
#Mann= 3 , 0 , 0
       0    .075       0    67.5     .05       0  118.72    .085       0
Bank Sta=67.5,118.72
Exp/Cntr=0.3,0.1

Type RM Length L Ch R = 1 ,68954   ,208.25,252.17,262.67
BEGIN DESCRIPTION:
68875.78
END DESCRIPTION:
XS GIS Cut Line= 5
  909635.3392764  810483.6454396  909674.4013342  810463.3329647
  909722.8386956  810430.5204265  909752.5264741  810411.7698194
  909796.2761837  810389.8954767
#Sta/Elev= 26
       0 1946.61    8.33 1939.69   15.16 1933.66    36.6 1917.46   40.28 1913.15
   44.03  1911.7   46.17 1910.86   47.65 1910.61   50.81 1910.27    63.5 1908.11
   67.65  1907.4   75.68 1905.61   80.82 1905.49   82.92 1905.41  102.53  1906.8
  103.19 1906.85  103.26 1906.86  104.691907.459  123.52  1915.3  134.62 1920.16
  137.65 1921.52  139.36 1922.28  171.28 1937.73  176.17 1940.01  182.86 1943.35
  186.56 1944.84
#Mann= 3 , 0 , 0
       0    .075       0    63.5     .05       0  104.69     .09       0
Bank Sta=63.5,104.69
Exp/Cntr=0.3,0.1

Type RM Length L Ch R = 1 ,68702   ,15.94,54.3,80.28
BEGIN DESCRIPTION:
68623.60
END DESCRIPTION:
XS GIS Cut Line= 6
  909705.6509805  810627.3946318  909744.7140625  810658.6453022
  909769.7141892  810664.8948218  909825.9639621  810664.8948218
  909866.5889119  810647.7081308  909925.9634446  810619.5822202
#Sta/Elev= 23
       0  1928.4   27.66 1924.95   31.49 1922.57   50.03 1915.23      65 1909.94
   85.45 1907.18  103.32 1904.72  110.37  1904.2  125.96 1904.11     129 1904.11
  136.84 1904.33  140.47 1904.62  144.39 1906.41  152.41  1909.8  193.49 1933.39
  198.51  1936.7   201.8 1938.75   204.7 1940.76  221.99 1950.17  223.94 1951.33
  224.28 1951.34   236.4 1958.41  241.85 1962.13
#Mann= 3 , 0 , 0
       0    .085       0   85.45     .05       0  144.39    .095       0
Bank Sta=85.45,144.39
Exp/Cntr=0.3,0.1

Type RM Length L Ch R = 1 ,68647   ,33.09,102.96,164.12
BEGIN DESCRIPTION:
68569.30
END DESCRIPTION:
XS GIS Cut Line= 6
  909705.6509805  810639.8946951   909771.276057  810710.2074234
  909804.0885952  810718.0198349  909854.0888486  810721.1456189
  909893.1509064  810732.0827902  909922.8386848  810747.7076134
#Sta/Elev= 26
       0 1926.98    17.7 1924.45    26.7 1923.04   47.88 1912.69    83.4 1909.17
   96.22 1907.79  102.74 1907.37  105.46 1907.32  107.75 1907.12  121.18 1905.14
  126.68 1904.96  142.47 1903.65  150.39 1903.51  154.03 1903.62  160.421905.241
  175.21 1908.99  180.05 1912.27  190.59 1919.61   196.8 1923.16  198.68 1924.32
   206.3 1929.83  217.72 1938.36  220.28 1939.83  232.71  1947.4  241.63 1954.24
  254.16 1963.59
#Mann= 3 , 0 , 0
       0    .085       0  121.18     .05       0  160.42     .09       0
Bank Sta=121.18,160.42
Exp/Cntr=0.3,0.1

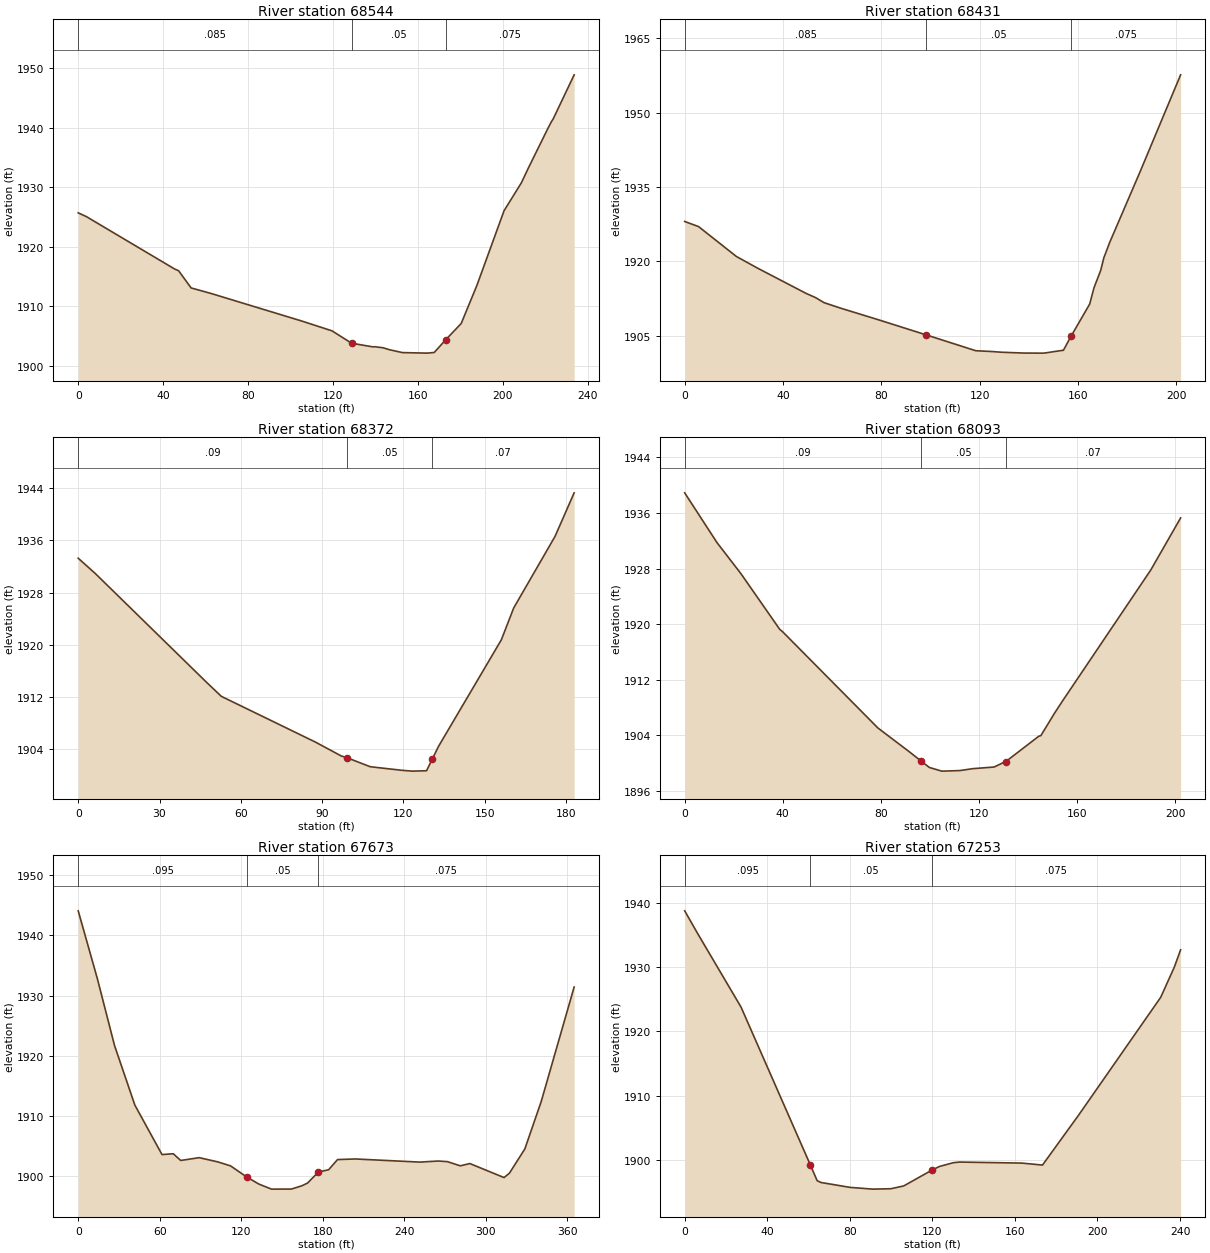
Type RM Length L Ch R = 1 ,68544   ,21.93,113.59,138.92
BEGIN DESCRIPTION:
68466.34
END DESCRIPTION:
XS GIS Cut Line= 6
  909697.8385689  810646.1452389  909699.4014609  810691.4578404
  909744.7140625  810744.5828536  909749.4017143  810760.2076767
  909750.9635821  810816.4574496  909757.2141258  810861.7700512
#Sta/Elev= 26
       0 1925.69    3.86 1925.05   45.36 1916.26   47.29 1915.96   53.17 1913.07
   62.49 1912.15  105.28 1907.51  119.54 1905.86  128.76 1903.78  138.79 1903.17
  139.58  1903.2  143.69 1903.01  146.41 1902.71  152.65 1902.21  164.31 1902.12
  167.66 1902.23  173.13 1904.39  180.37  1907.1   187.8 1913.54  200.54 1926.04
  208.66 1930.71  212.04 1933.25  221.35 1939.98  222.77 1940.95  223.74 1941.51
  233.55 1948.87
#Mann= 3 , 0 , 0
       0    .085       0  128.76     .05       0  173.13    .075       0
Bank Sta=128.76,173.13
Exp/Cntr=0.3,0.1

Type RM Length L Ch R = 1 ,68431   ,66.16,58.22,75.96
BEGIN DESCRIPTION:
68352.75
END DESCRIPTION:
XS GIS Cut Line= 6
  909680.6508538  810638.3328273   909677.526094  810668.0206058
   909677.526094  810691.4578404  909668.1518147  810714.8950751
  909632.2134924   810774.270632   909605.651498  810821.1451014
#Sta/Elev= 30
       0 1928.02    5.66 1926.98   21.05 1920.95   29.85 1918.55   49.47 1913.49
   53.29 1912.65   56.69 1911.64   63.62  1910.5   78.53 1908.23   98.29 1905.13
  118.49 1901.93  124.87 1901.78  127.57 1901.68  128.98 1901.63  138.25 1901.46
  146.08 1901.45  147.45 1901.54  147.94 1901.58  154.06 1902.03  154.14 1902.02
  154.35 1902.24  154.66 1902.51  157.18 1904.81  164.81 1911.35  166.58 1914.65
  169.31 1918.17   170.6 1920.72  172.99 1923.82  185.37  1938.1  201.82 1957.61
#Mann= 3 , 0 , 0
       0    .085       0   98.29     .05       0  157.18    .075       0
Bank Sta=98.29,157.18
Exp/Cntr=0.3,0.1

Type RM Length L Ch R = 1 ,68372   ,222.51,279.73,264.83
BEGIN DESCRIPTION:
68294.53
END DESCRIPTION:
XS GIS Cut Line= 6
  909627.5258407  810614.8955926  909613.4639095    810660.20717
  909608.7762578  810711.7703153  909588.4637829  810732.0827902
  909574.4008275  810743.0199616  909543.1511813  810763.3324365
#Sta/Elev= 20
       0 1933.27    6.28 1930.93   47.44 1914.17   52.83 1912.04   87.61    1905
   97.08 1902.88   99.22 1902.61  107.67 1901.24   107.8 1901.23  110.86 1901.08
  119.39 1900.68  123.32 1900.55  127.95  1900.6  128.56 1900.61  130.65 1902.38
     133 1904.37  156.16 1920.73  160.73 1925.63  175.98 1936.63  183.03 1943.32
#Mann= 3 , 0 , 0
       0     .09       0   99.22     .05       0  130.65     .07       0
Bank Sta=99.22,130.65
Exp/Cntr=0.3,0.1

Type RM Length L Ch R = 1 ,68093   ,428.68,420.16,446.53
BEGIN DESCRIPTION:
68014.81
END DESCRIPTION:
XS GIS Cut Line= 6
  909460.3383897   810496.145503  909435.3392872  810527.3951492
  909388.4637936  810546.1447322  909375.9637303  810553.9571437
  909346.2759518  810593.0202257  909330.6511287  810638.3328273
#Sta/Elev= 24
       0  1938.9    13.2 1931.73   22.97 1927.26   38.75 1919.27   40.02 1918.89
   78.79 1905.08    90.5 1901.95   90.71  1901.9   96.531900.292   99.76  1899.4
  104.64 1898.89  104.81 1898.87  105.25 1898.87  112.23 1898.95  117.37 1899.22
  126.19 1899.46  130.87 1900.25   131.2 1900.31   144.4 1903.89  145.26 1903.98
  150.82  1907.2  154.31 1909.08  190.07  1927.8  202.24 1935.29
#Mann= 3 , 0 , 0
       0     .09       0   96.53     .05       0  130.87     .07       0
Bank Sta=96.53,130.87
Exp/Cntr=0.3,0.1

Type RM Length L Ch R = 1 ,67673   ,427.5,419.82,428.58
BEGIN DESCRIPTION:
67594.64
END DESCRIPTION:
XS GIS Cut Line= 6
  909133.7758993  810227.3946533  909086.9014299  810272.7072549
  909015.0258096  810332.0828118  908943.1512136   810419.582231
  908915.0263271  810432.0822943  908852.5260104  810435.2080783
#Sta/Elev= 30
       0 1944.08   14.16 1932.76   26.74  1921.7   41.71  1911.8    61.7 1903.58
   69.98 1903.72   75.47  1902.6   89.06 1903.07  102.71 1902.37  112.17  1901.7
  124.32 1899.82     133 1898.68  142.29 1897.84  156.95 1897.85  164.57 1898.39
  168.87 1898.85  176.76 1900.67  184.35 1901.06  190.93 1902.75  203.95 1902.85
  251.58 1902.33  265.14 1902.51  271.76 1902.41   281.3 1901.71  288.33 1902.09
  313.51 1899.76  317.48 1900.49  328.81 1904.51  340.86 1912.39  365.12 1931.42
#Mann= 3 , 0 , 0
       0    .095       0  124.32     .05       0  176.76    .075       0
Bank Sta=124.32,176.76
Exp/Cntr=0.3,0.1

Type RM Length L Ch R = 1 ,67253   ,298.15,266.6,172.65
BEGIN DESCRIPTION:
67174.83
END DESCRIPTION:
XS GIS Cut Line= 5
  908816.5887124  809949.2705484  908760.3389395  809994.5821258
  908729.0892932  810032.0823158  908683.7766916   810085.207329
  908655.6518052  810125.8322788
#Sta/Elev= 20
       0  1938.8    6.36 1935.22   27.31 1923.79   60.93 1899.15    64.2 1896.72
    66.1 1896.44   80.21 1895.68   91.12 1895.41   99.89 1895.47  106.15 1895.91
  119.65 1898.35  123.41 1898.94  130.14 1899.53  133.19 1899.63   163.3 1899.47
  173.36 1899.16  190.87 1906.95  230.64 1925.32   237.2    1930  240.28 1932.72
#Mann= 3 , 0 , 0
       0    .095       0   60.93     .05       0  119.65    .075       0
Bank Sta=60.93,119.65
Exp/Cntr=0.3,0.1

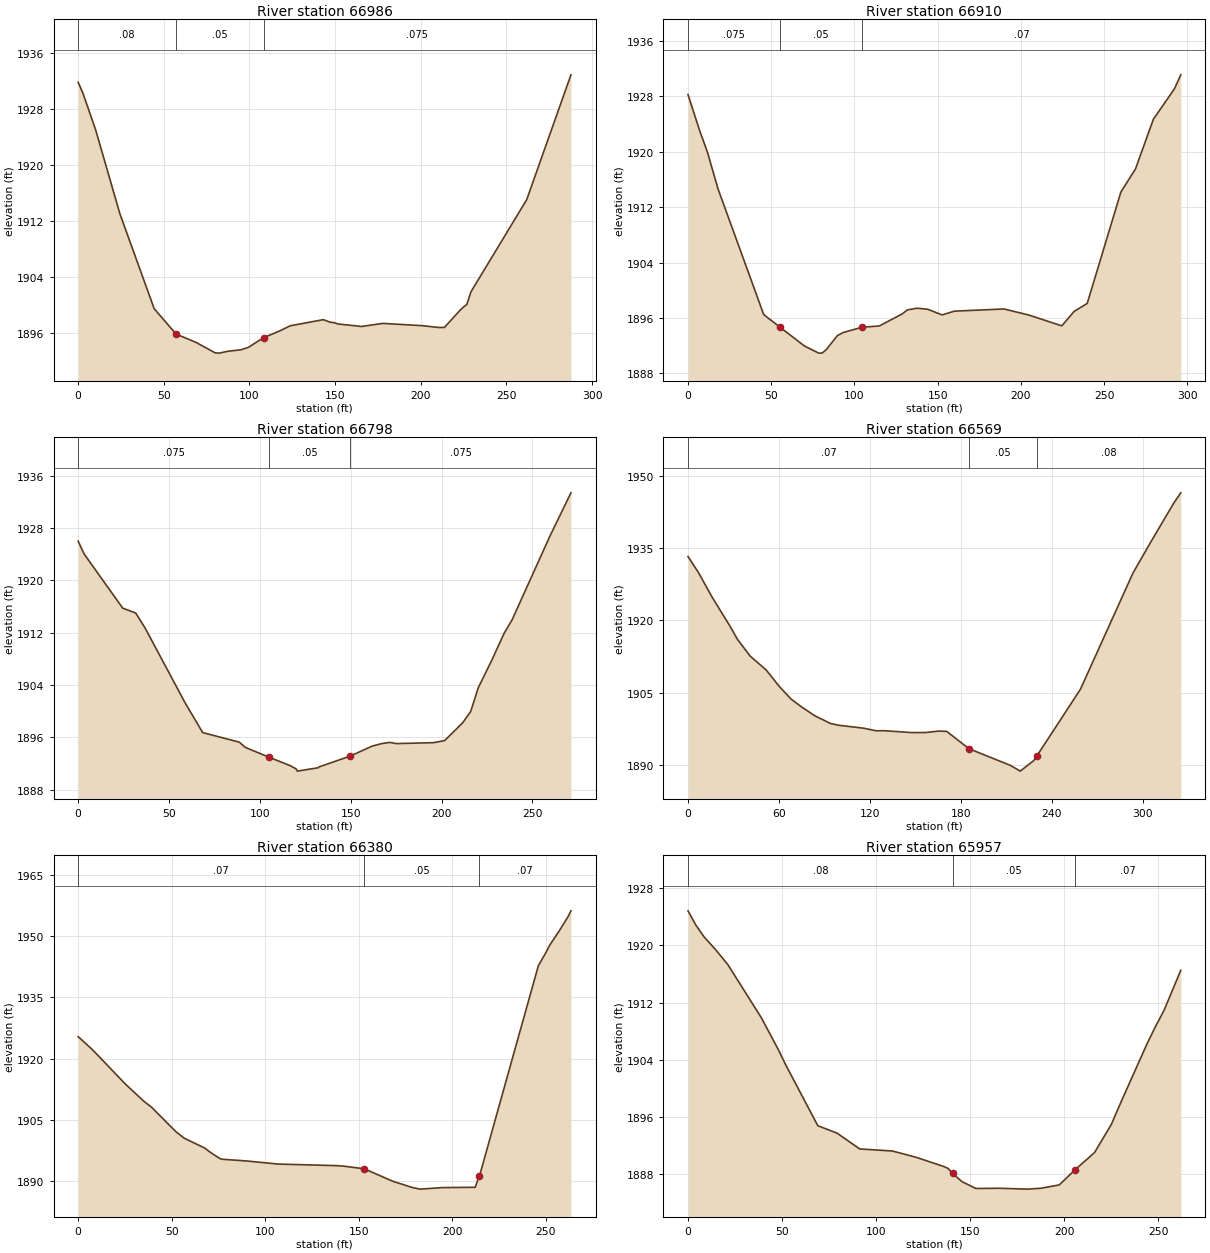
Type RM Length L Ch R = 1 ,66986   ,122.08,75.95,17.5
BEGIN DESCRIPTION:
66908.23
END DESCRIPTION:
XS GIS Cut Line= 6
  908536.9017155  809811.7698517  908521.2758682  809853.9576935
  908508.7758049  809902.3950549  908505.6510451  809932.0828333
  908513.4634567  810025.8327963  908515.0263487  810094.5826325
#Sta/Elev= 30
       0  1931.8    2.79 1930.23   10.22 1924.98   24.36 1913.01   44.37 1899.45
   57.16 1895.83   68.84 1894.63   79.97 1893.14   82.28  1893.1   87.55 1893.37
   94.92 1893.57   99.36 1893.92  108.21  1895.3  117.83 1896.29  123.82 1897.01
  143.12 1897.88   147.3 1897.51  149.24 1897.47  151.81 1897.26  165.49 1896.91
  177.82 1897.35  200.99 1897.02  210.24 1896.77  213.82 1896.77  223.22 1899.29
  226.03  1899.9  226.82    1900  229.34 1901.86  261.89 1915.03  287.71 1932.86
#Mann= 3 , 0 , 0
       0     .08       0   57.16     .05       0  108.21    .075       0
Bank Sta=57.16,108.21
Exp/Cntr=0.3,0.1

Type RM Length L Ch R = 1 ,66910   ,125.25,112.34,23.37
BEGIN DESCRIPTION:
66832.28
END DESCRIPTION:
XS GIS Cut Line= 6
  908372.8390243  809852.3948015   908433.776449  809896.1455353
  908469.7137471  809928.9580735  908482.2138104  809977.3954349
  908496.2767657  810055.5205747  908504.0891773  810097.7073923
#Sta/Elev= 30
       0 1928.28    7.04 1923.04   11.66 1919.97   18.05 1914.64   45.49 1896.49
   55.251894.681   69.93 1891.96   78.54 1890.93   80.56 1890.94   83.04 1891.43
   89.69 1893.45   93.11  1893.9  104.54 1894.67   114.9 1894.85  128.84 1896.62
  131.72 1897.17   137.6 1897.42   144.1 1897.26  152.58 1896.45  159.98 1896.99
  189.74 1897.31  204.46 1896.45  224.52 1894.87  231.91 1896.95  239.79 1898.11
     260 1914.19  268.82 1917.55  279.52 1924.71  292.19 1929.11  295.99 1931.13
#Mann= 3 , 0 , 0
       0    .075       0   55.25     .05       0  104.54     .07       0
Bank Sta=55.25,104.54
Exp/Cntr=0.3,0.1

Type RM Length L Ch R = 1 ,66798   ,195.03,228.69,210.59
BEGIN DESCRIPTION:
66719.94
END DESCRIPTION:
XS GIS Cut Line= 6
  908305.6510559  809938.3323529  908343.1512459  809983.6449545
  908386.9009555  809999.2697776  908441.5888606  810013.3327329
  908466.5889873  810035.2080998  908486.9014622  810108.6455879
#Sta/Elev= 30
       0 1925.97    3.28 1924.01   24.53 1915.73   31.66 1914.99   36.86 1912.68
   58.82 1901.27   68.52 1896.71   88.62 1895.25   92.06 1894.44  105.27 1892.92
  116.88 1891.63   119.9 1891.16  120.61 1890.82  132.16 1891.34  132.48 1891.46
  149.82 1893.13  161.74 1894.64   167.2 1895.04  171.48 1895.21  175.04 1895.03
  195.53 1895.17  201.67 1895.49  211.56  1898.2  216.01 1899.94  220.14 1903.55
  227.54 1907.73  234.34 1911.86  238.79 1913.95  259.78 1926.85  271.17 1933.36
#Mann= 3 , 0 , 0
       0    .075       0  105.27     .05       0  149.82    .075       0
Bank Sta=105.27,149.82
Exp/Cntr=0.3,0.1

Type RM Length L Ch R = 1 ,66569   ,169.58,188.71,207.65
BEGIN DESCRIPTION:
66491.25
END DESCRIPTION:
XS GIS Cut Line= 5
  908140.0264969   810049.270031  908224.4011563  810135.2075823
  908275.9643016  810180.5201839  908332.2140745  810227.3946533
  908388.4638475  810255.5205639
#Sta/Elev= 30
       0 1933.22    6.88 1929.91   15.93 1924.79   27.83 1918.73   32.56 1916.09
   41.09 1912.56   51.58 1909.71   60.07 1906.35   67.89 1903.71   74.81 1902.08
   83.58 1900.23   94.13  1898.6   99.82 1898.23  116.08 1897.63   124.2  1897.1
  129.19 1897.12  147.52 1896.73  156.65 1896.74  165.71 1897.04  170.76 1896.97
  185.38 1893.39  212.92 1889.91  219.21 1888.74  228.27 1890.95  230.17 1891.86
  258.97 1905.71   293.7 1929.83  305.56 1936.31  320.41 1944.21  325.19 1946.42
#Mann= 3 , 0 , 0
       0     .07       0  185.38     .05       0  230.17     .08       0
Bank Sta=185.38,230.17
Exp/Cntr=0.3,0.1

Type RM Length L Ch R = 1 ,66380   ,332.39,423.79,452.28
BEGIN DESCRIPTION:
66302.53
END DESCRIPTION:
XS GIS Cut Line= 5
  908043.1517741   810160.207709  908086.9014837  810232.0823051
  908140.0264969  810302.3950333  908166.5884913  810335.2075716
  908180.6514467  810382.0830651
#Sta/Elev= 30
       0 1925.39    6.71 1922.59    9.15 1921.48    25.1 1913.82   35.31 1909.47
   39.11 1908.13   52.22 1902.09    56.7 1900.48   67.73 1898.05   70.39  1897.1
   75.88 1895.45    77.5  1895.3   89.99  1894.9  106.72 1894.14  137.53 1893.76
  141.51 1893.65  152.81 1892.99  168.16 1889.93  178.35 1888.42  182.78 1887.99
  194.97 1888.37  212.25 1888.44  214.48 1891.33  214.78 1891.62     246  1942.8
   249.7 1945.75  252.12 1947.88  257.28 1951.42  261.91 1954.86  263.42 1956.26
#Mann= 3 , 0 , 0
       0     .07       0  152.81     .05       0  214.48     .07       0
Bank Sta=152.81,214.48
Exp/Cntr=0.3,0.1

Type RM Length L Ch R = 1 ,65957   ,463.97,440.02,435.11
BEGIN DESCRIPTION:
65878.75
END DESCRIPTION:
XS GIS Cut Line= 5
  907779.0885762  810205.5203106  907761.9008611  810280.5196664
  907738.4636264  810358.6448063  907733.7759746  810405.5202998
  907733.7759746  810461.7700728
#Sta/Elev= 30
       0 1924.84    4.16 1922.85    8.61 1921.17   14.75 1919.39   21.15 1917.33
   38.99 1909.88    48.1 1905.38   51.76 1903.39   68.98 1894.79   79.27 1893.74
   91.27 1891.54  108.63 1891.25   121.1 1890.38   135.9 1889.09   138.1 1888.83
  140.66 1888.11  145.57 1886.97  153.01 1886.01   165.4 1886.04  180.34 1885.92
  187.51 1886.04   197.3 1886.51  205.62 1888.61  216.04 1891.03  224.94 1894.96
  230.51 1898.34  243.92 1906.23  248.36 1908.62  252.97 1910.92  261.87 1916.52
#Mann= 3 , 0 , 0
       0     .08       0  140.66     .05       0  205.62     .07       0
Bank Sta=140.66,205.62
Exp/Cntr=0.3,0.1

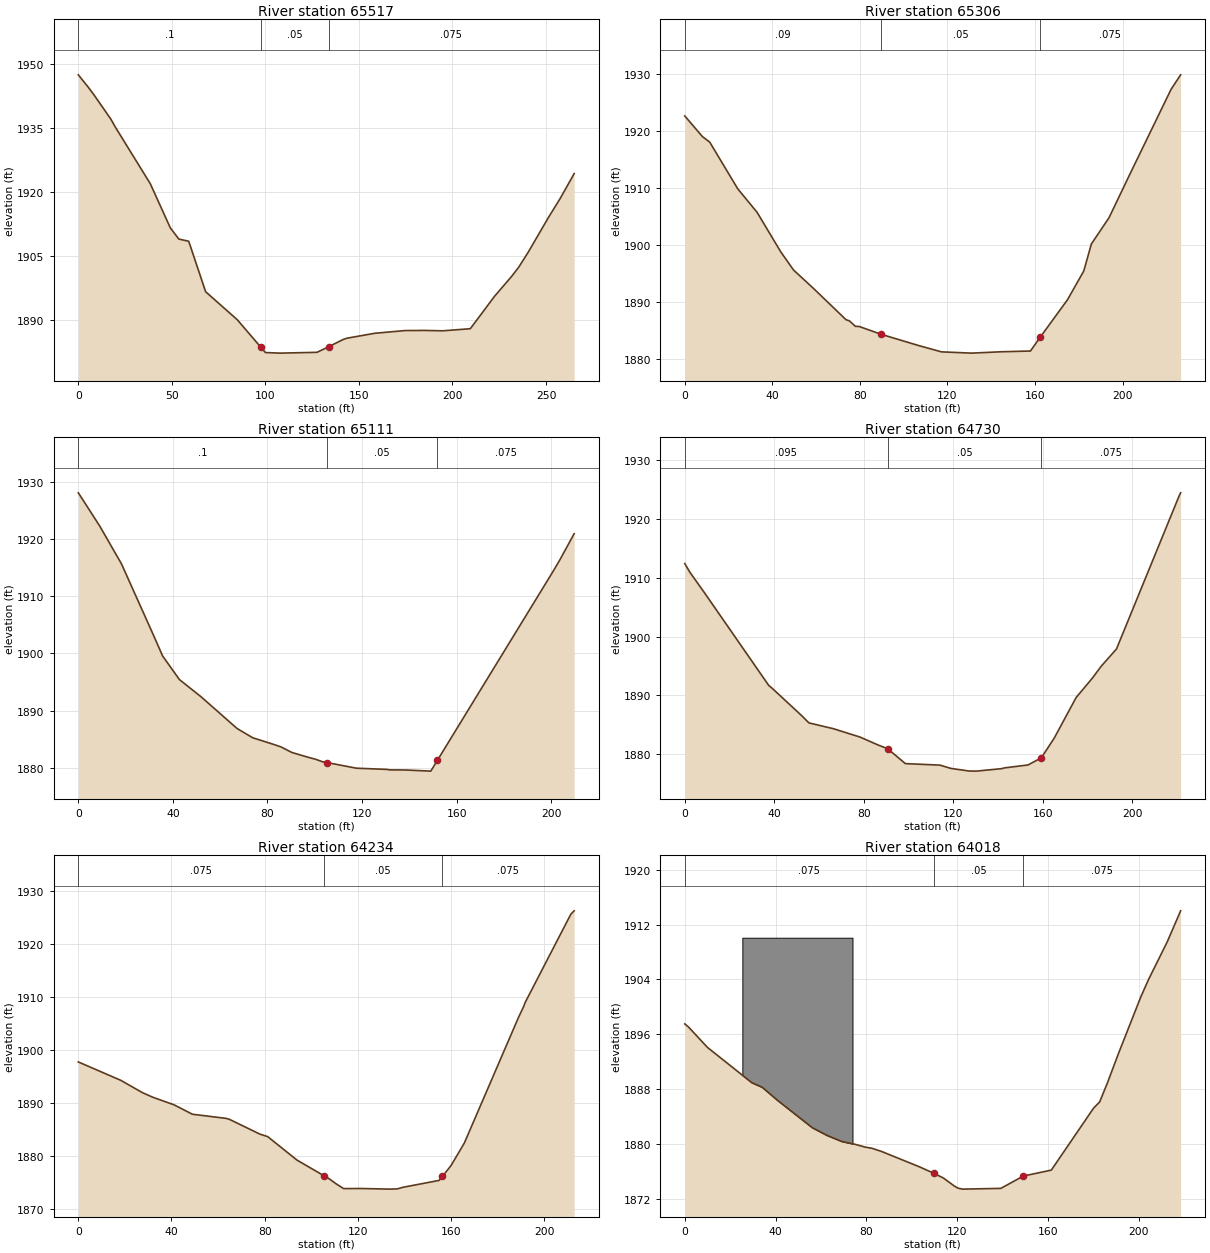
Type RM Length L Ch R = 1 ,65517   ,179.14,210.27,249.75
BEGIN DESCRIPTION:
65438.73
END DESCRIPTION:
XS GIS Cut Line= 5
  907310.3387615   810196.145007  907304.0892419  810294.5826218
  907305.6511097  810347.7076349  907305.6511097  810382.0830651
  907294.7139384  810460.2071808
#Sta/Elev= 30
       0 1947.52    5.34  1944.6    8.43 1942.79   17.46 1937.09   19.65 1935.37
   38.49 1921.99   49.17 1911.66   53.73 1909.03   59.01 1908.52   68.06 1896.69
   84.96 1890.13   97.421883.755  100.02 1882.43  107.76  1882.3   127.6 1882.49
  133.761883.785  141.34 1885.45  143.51 1885.79  158.43 1886.95  174.75 1887.59
  185.18 1887.62  194.78 1887.53  209.54 1888.02  222.62 1895.69  231.68 1900.31
  235.42 1902.44  240.64 1906.06  251.18    1914  257.59 1918.55  265.05 1924.37
#Mann= 3 , 0 , 0
       0      .1       0   97.42     .05       0  133.76    .075       0
Bank Sta=97.42,133.76
Exp/Cntr=0.3,0.1

Type RM Length L Ch R = 1 ,65306   ,178.6,195.6,187.44
BEGIN DESCRIPTION:
65228.46
END DESCRIPTION:
XS GIS Cut Line= 6
  907175.9638487  810213.3327222  907132.2141391    810252.39478
   907113.463532  810274.2701469  907085.3386456    810327.39516
  907050.9642395  810371.1448696  907033.7765244  810386.7696927
#Sta/Elev= 26
       0 1922.62    8.03 1919.01   11.39 1918.03    24.2 1909.84   33.03 1905.72
   43.86 1898.78   49.69  1895.6   58.65 1892.43   73.63  1886.9   75.19 1886.69
   77.96 1885.73    79.7  1885.7   89.73 1884.33  106.83 1882.36   117.3 1881.25
   131.1 1881.03  144.64 1881.27  157.92  1881.4  162.32 1883.79  174.86  1890.4
  182.29 1895.44  185.75 1900.17  193.83 1904.78   203.3 1912.37  222.16 1927.28
  226.53 1929.83
#Mann= 3 , 0 , 0
       0     .09       0   89.73     .05       0  162.32    .075       0
Bank Sta=89.73,162.32
Exp/Cntr=0.3,0.1

Type RM Length L Ch R = 1 ,65111   ,365.17,380.63,408.9
BEGIN DESCRIPTION:
65032.85
END DESCRIPTION:
XS GIS Cut Line= 4
  907030.6517646  810099.2702843   906966.588556  810171.1448804
  906935.3389097  810199.2697668  906907.2140232  810264.8948433
#Sta/Elev= 29
       0 1928.17    2.34 1926.67    9.12  1922.3   18.28 1915.69   31.87 1903.13
   35.63 1899.58   42.75 1895.43   51.76 1892.46    67.1 1886.86   73.76 1885.22
   82.29  1884.1    85.7 1883.62   90.32 1882.64   96.28 1881.91  100.59 1881.42
  103.27 1881.01  105.22 1880.87  117.66 1879.88  118.39 1879.88  118.45 1879.87
  130.71 1879.67  131.54 1879.59  138.32 1879.57  149.08 1879.37  151.861881.253
  200.88 1914.45  203.68 1916.42  209.61 1920.92  209.72    1921
#Mann= 3 , 0 , 0
       0      .1       0  105.22     .05       0  151.86    .075       0
Bank Sta=105.22,151.86
Exp/Cntr=0.3,0.1

Type RM Length L Ch R = 1 ,64730   ,470.99,496.19,530.95
BEGIN DESCRIPTION:
64652.22
END DESCRIPTION:
XS GIS Cut Line= 3
    906741.58844  809891.4578835  906649.4013691  809958.6448278
  906561.9009257  810021.1451445
#Sta/Elev= 27
       0 1912.44    2.25 1910.98    8.64 1907.56   37.58 1891.67   38.91 1891.27
   52.21 1886.57   55.46 1885.33   66.51 1884.33   78.29 1882.92   86.55 1881.54
   90.63 1880.94   98.58  1878.4  114.07 1878.14  118.85 1877.59  126.99 1877.14
  130.25 1877.12  141.59 1877.54  142.87 1877.67   153.4 1878.17  159.31 1879.37
  165.11 1882.74  174.89 1889.64  181.97 1892.86   186.2 1895.01  192.94 1897.91
  220.85 1923.88   221.6 1924.48
#Mann= 3 , 0 , 0
       0    .095       0   90.63     .05       0  159.31    .075       0
Bank Sta=90.63,159.31
Exp/Cntr=0.3,0.1

Type RM Length L Ch R = 1 ,64234   ,191.05,216.15,202.6
BEGIN DESCRIPTION:
64156.03
END DESCRIPTION:
XS GIS Cut Line= 4
  906508.7759126  809499.2703166   906410.339322  809536.7705066
  906377.5267838   809546.144786  906304.0892957   809547.707678
#Sta/Elev= 28
       0 1897.78   18.24 1894.31   27.59 1891.97   32.09  1891.1   41.09 1889.69
   48.98 1887.91   63.44 1887.13   64.81 1886.96      78 1884.15   81.33 1883.68
   93.84 1879.27  105.34 1876.33  107.58 1875.77  110.64 1874.79  113.93 1873.87
  121.43 1873.89  133.76 1873.77  136.99 1873.82  139.46 1874.12  154.96 1875.42
   156.31876.155  160.01 1878.19  165.77 1882.48  189.09 1906.26  191.16 1908.17
  191.88 1909.01  211.49 1925.67  212.92 1926.31
#Mann= 3 , 0 , 0
       0    .075       0  105.34     .05       0   156.3    .075       0
Bank Sta=105.34,156.3
Exp/Cntr=0.3,0.1

Type RM Length L Ch R = 1 ,64018   ,143.83,145.11,162.58
BEGIN DESCRIPTION:
63939.88
END DESCRIPTION:
XS GIS Cut Line= 4
  906474.4015065  809325.8323219  906355.6514169  809328.9581058
   906297.838752   809344.582929   906261.901454  809361.7706441
#Sta/Elev= 30
       0 1897.51    1.66 1897.05    9.97 1894.08    29.5 1888.93   34.12 1888.25
   40.72 1886.38    56.2 1882.34   62.75 1881.21   69.28 1880.33   75.02 1879.92
   79.45 1879.51   82.42 1879.34   86.51  1878.9  103.19 1876.66  109.71 1875.69
  113.99 1874.99  118.75 1873.83  120.41 1873.51  122.47 1873.37  139.28 1873.48
  149.18 1875.28  161.53 1876.15  180.19 1885.22  182.82  1886.1   186.3 1888.93
  191.12 1893.18  200.97 1901.46  204.38    1904   212.6 1909.49  218.51 1914.03
#Mann= 3 , 0 , 0
       0    .075       0  109.71     .05       0  149.18    .075       0
#Block Obstruct= 1 ,-1
   25.36    73.91910.102
Bank Sta=109.71,149.18
Exp/Cntr=0.5,0.3

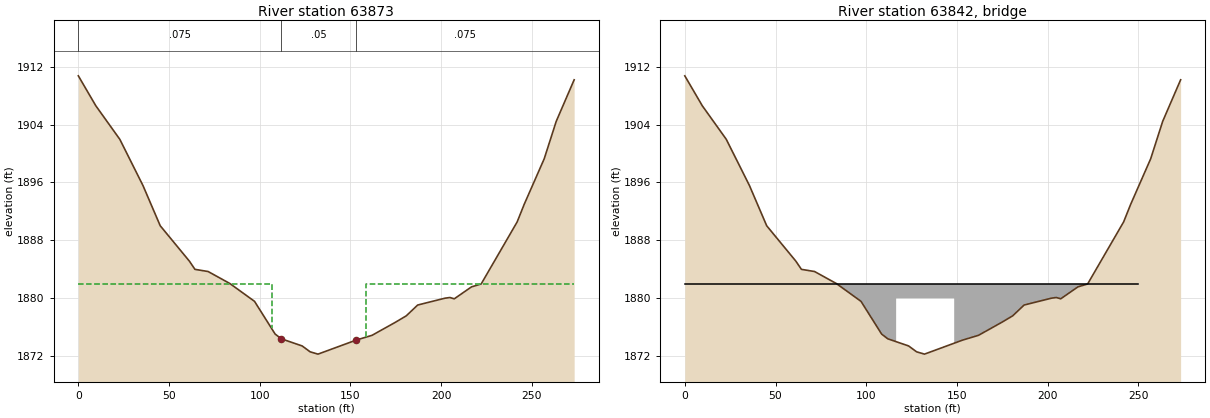
Type RM Length L Ch R = 1 ,63873   ,45.24,54.7,32.02
BEGIN DESCRIPTION:
63794.76
END DESCRIPTION:
XS GIS Cut Line= 5
  906468.1509628   809177.395478  906404.0887783  809188.3326493
  906263.4633218  809188.3326493  906225.9641559  809197.7079529
  906202.5258971  809214.8946438
#Sta/Elev= 30
       0 1910.73    9.63  1906.6   22.87 1901.96   35.65 1895.57   45.15 1890.02
   61.26 1885.12   64.28    1884   71.54  1883.7   83.55 1882.04   97.13 1879.58
   108.5 1875.06  111.86 1874.41  123.39 1873.42  127.78 1872.61  132.12 1872.29
  153.07 1874.22  161.93 1874.89  174.87  1876.7  180.78 1877.58  187.06 1879.07
  202.19 1880.02  204.84 1880.11  207.24 1879.93  216.74 1881.58  222.07 1881.98
  241.91 1890.55  245.74 1892.95  256.82 1899.27  263.44 1904.44  273.33 1910.18
#Mann= 3 , 0 , 0
       0    .075       0  111.86     .05       0  153.07    .075       0
#XS Ineff= 2 , 0
       0   106.5    1882   158.5       0    1882
Permanent Ineff=
       F       F
Bank Sta=111.86,153.07
Exp/Cntr=0.5,0.3

Type RM Length L Ch R = 3 ,63842   ,,,
BEGIN DESCRIPTION:
63765  FBSTR_5034
END DESCRIPTION:
Bridge Culvert--1,0,-1,-1, 0
Deck Dist Width WeirC Skew NumUp NumDn MinLoCord MaxHiCord MaxSubmerge Is_Ogee
22,12,2.6,0, 6, 6, , , 0.95, 0, 1,1,,
       0   116.5   116.5   148.5   148.5     250
    1882    1882    1882    1882    1882    1882
                    1880    1880
       0     132     132     164     164     250
    1882    1882    1882    1882    1882    1882
                    1880    1880
BR Coef=-1 , 0 , 0 ,, 0 ,,,0.8,0,,0,
WSPro=,,,, 1 ,,,, 0 ,,,, 0 ,,,,-1 ,-1 ,-1 , 0 , 0 , 0 , 0 , 0
BC Design=,, 0 ,, 0 ,,,,,,