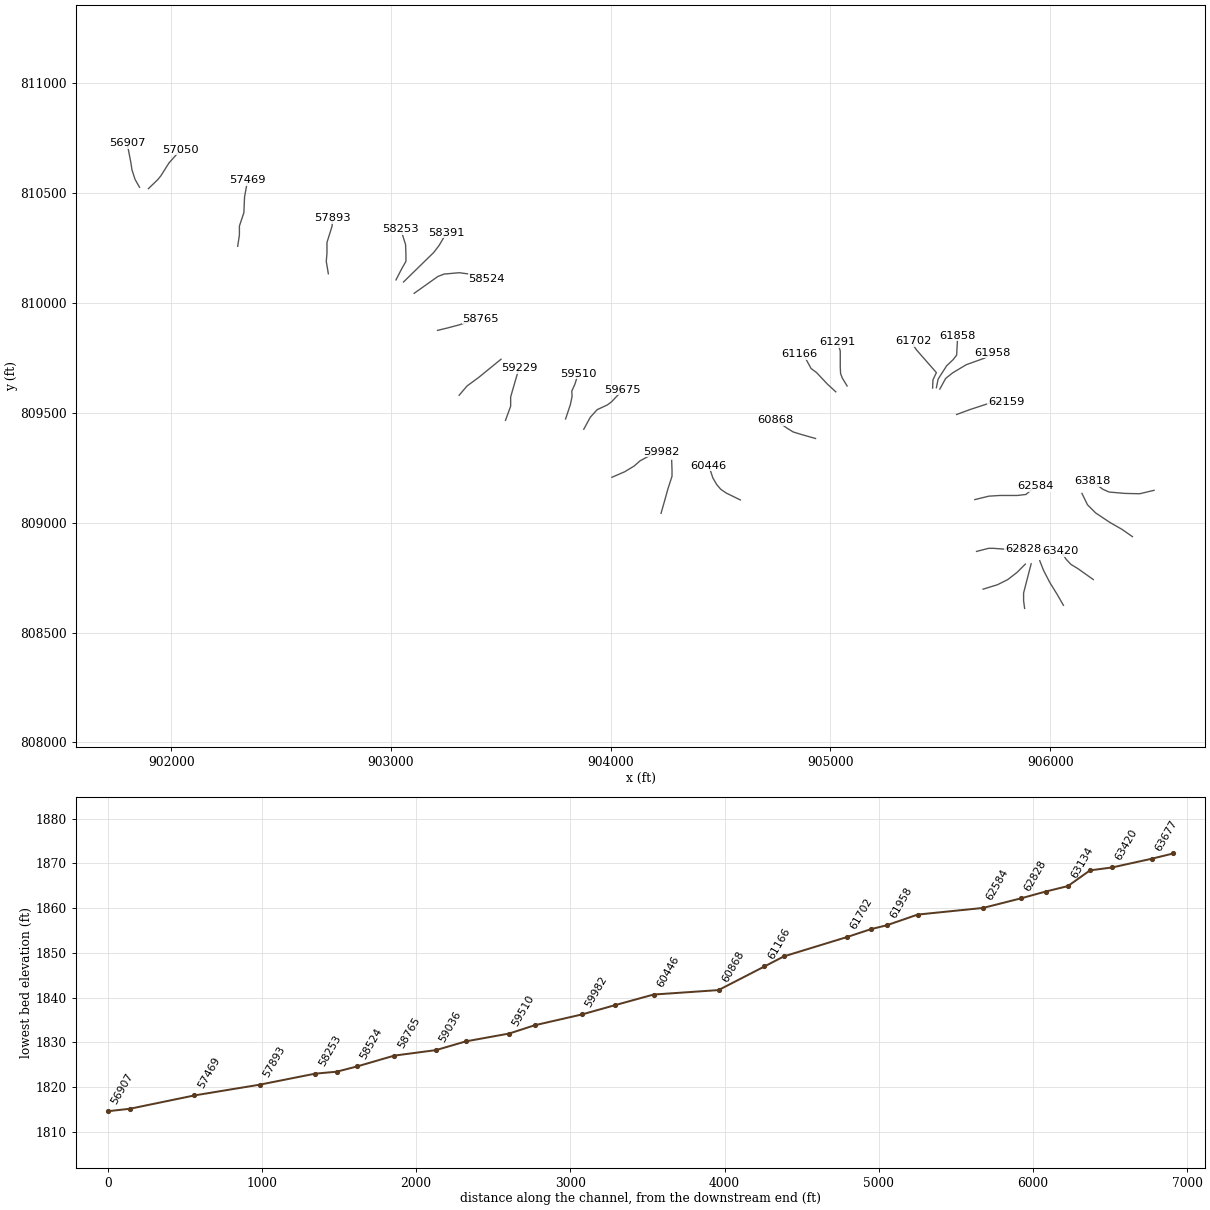
HEC-RAS study lds_big_laurel_crk.prj: lds_big_laurel_crk

--- lds_big_laurel_crk.g20 (geometry) --- (continued)

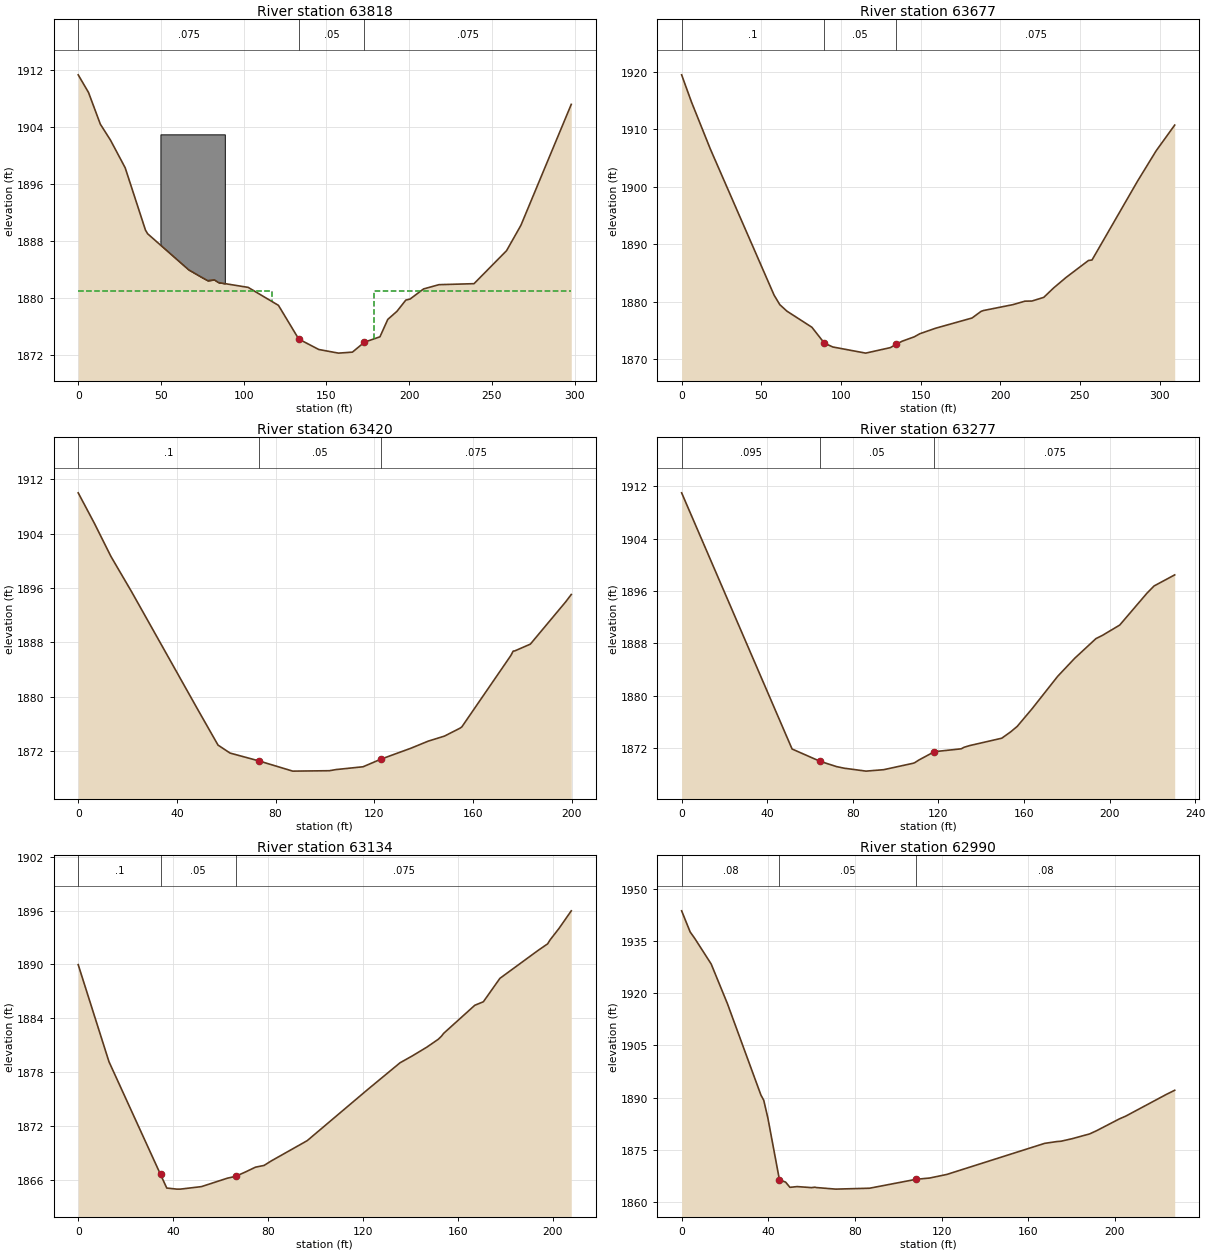
Type RM Length L Ch R = 1 ,63818   ,243.75,140.93,101.58
BEGIN DESCRIPTION:
63740.07
END DESCRIPTION:
XS GIS Cut Line= 6
  906472.8386145  809147.7076995  906407.2135381  809132.0828764
  906340.0265938  809133.6447442  906268.1509735   809139.895288
  906240.0260871  809152.3953513  906191.5887257  809188.3326493
#Sta/Elev= 30
       0 1911.28    6.25  1908.8   13.36 1904.37   19.51 1902.12   28.38 1898.25
   40.67 1889.49   41.96 1888.99   66.77 1883.93   75.21  1882.8   78.32 1882.41
   82.19 1882.53   84.88 1882.14   102.7 1881.47     121 1878.95  133.28 1874.22
  145.37 1872.76  157.29 1872.25   165.7 1872.39  172.93 1873.78  182.34 1874.54
  187.06 1876.98  192.59 1878.11  197.97 1879.69   200.5 1879.83  208.68 1881.25
  217.97 1881.85  239.17 1881.99  258.84 1886.62  267.51 1890.18  297.93 1907.14
#Mann= 3 , 0 , 0
       0    .075       0  133.28     .05       0  172.93    .075       0
#XS Ineff= 2 , 0
       0     117    1881     179       0    1881
Permanent Ineff=
       F       F
#Block Obstruct= 1 ,-1
   49.69   88.591902.933
Bank Sta=133.28,172.93
Exp/Cntr=0.5,0.3

Type RM Length L Ch R = 1 ,63677   ,262.28,256.88,246.31
BEGIN DESCRIPTION:
63599.14
END DESCRIPTION:
XS GIS Cut Line= 6
  906374.4009998  808936.7705389  906327.5265304  808969.5830772
  906272.8386253  809000.8327234  906207.2135488   809044.582433
  906169.7133588   809082.082623  906144.7142563  809133.6447442
#Sta/Elev= 30
       0 1919.47    6.17 1914.75   17.96  1906.6   57.99 1881.17   61.61 1879.49
   66.09 1878.36   81.76 1875.56   89.53 1872.81   94.87 1872.13  115.51 1871.06
  131.03 1872.02  134.73 1872.61  138.36 1873.13  146.04  1873.9  149.46 1874.43
  159.38 1875.39  182.25 1877.17  187.97 1878.33  189.45 1878.47  207.88 1879.49
  215.44  1880.1  219.83 1880.12  227.27 1880.76  233.47  1882.4  241.25 1884.22
  255.31 1887.17  257.56 1887.26  286.11 1900.97  297.79 1906.25  309.45 1910.73
#Mann= 3 , 0 , 0
       0      .1       0   89.53     .05       0  134.73    .075       0
Bank Sta=89.53,134.73
Exp/Cntr=0.3,0.1

Type RM Length L Ch R = 1 ,63420   ,169.46,143.39,117.51
BEGIN DESCRIPTION:
63342.25
END DESCRIPTION:
XS GIS Cut Line= 5
  906196.2763775  808741.4571773  906125.9636492  808791.4574307
   906094.714003  808810.2080377  906072.8386361  808833.6452724
  906047.8385094  808871.1454625
#Sta/Elev= 24
       0 1909.98    6.61 1905.47   13.25 1900.65   21.62 1895.47   48.48 1878.15
   56.68 1872.93   61.57 1871.76   73.16 1870.62   86.95 1869.11  101.81 1869.17
  104.54 1869.34  115.46 1869.75  122.72 1870.87  134.84 1872.47  141.91 1873.52
  148.43 1874.25  154.78 1875.42   155.5 1875.61  175.35 1886.08  176.31 1886.74
  176.92 1886.76  183.27 1887.76  197.61 1893.98  199.85 1895.05
#Mann= 3 , 0 , 0
       0      .1       0   73.16     .05       0  122.72    .075       0
Bank Sta=73.16,122.72
Exp/Cntr=0.3,0.1

Type RM Length L Ch R = 1 ,63277   ,169.01,143.21,67.54
BEGIN DESCRIPTION:
63198.87
END DESCRIPTION:
XS GIS Cut Line= 5
  906060.3385727  808624.2699797  906030.6518185   808675.833125
  905997.8392802  808728.9581381  905969.7133696  808783.6450191
  905952.5266787  808827.3947287
#Sta/Elev= 26
       0 1910.99   51.62 1871.84   64.63 1869.97   72.42 1869.15    75.9 1868.91
   86.18 1868.46   94.43 1868.68  108.06 1869.65  108.89 1869.74  110.73 1870.13
  118.11 1871.43  130.69 1871.87  131.96  1872.1   134.7 1872.37  149.62 1873.49
  153.85 1874.48  156.82 1875.29  163.85 1878.02  175.75 1882.95  183.69  1885.7
  193.63 1888.71  196.68 1889.21  204.74 1890.78  217.44 1895.64  220.81 1896.76
  230.44 1898.45
#Mann= 3 , 0 , 0
       0    .095       0   64.63     .05       0  118.11    .075       0
Bank Sta=64.63,118.11
Exp/Cntr=0.3,0.1

Type RM Length L Ch R = 1 ,63134   ,180.59,144.06,41.65
BEGIN DESCRIPTION:
63055.65
END DESCRIPTION:
XS GIS Cut Line= 4
  905883.7758182  808610.2080485  905879.0891906  808644.5824546
  905879.0891906  808680.5197526  905913.4635967  808813.3327975
#Sta/Elev= 30
       0 1889.98   12.97 1879.16   34.69 1866.59   37.33 1865.07   41.59 1864.95
   43.05 1864.95   51.96 1865.23   62.88 1866.17   66.43 1866.38   66.52 1866.39
   70.63 1866.88   74.75  1867.4   78.33 1867.59   81.48 1868.11    96.5 1870.35
  121.99 1876.05  135.67 1879.04   140.6 1879.77  146.95 1880.78  151.82 1881.67
   153.1    1882  154.08 1882.33  167.16 1885.45  170.77 1885.84  177.74 1888.45
   193.7 1891.54  197.87  1892.3  198.87 1892.73  202.69 1894.03  207.82 1895.98
#Mann= 3 , 0 , 0
       0      .1       0   34.69     .05       0   66.52    .075       0
Bank Sta=34.69,66.52
Exp/Cntr=0.3,0.1

Type RM Length L Ch R = 1 ,62990   ,174.92,161.51,102.5
BEGIN DESCRIPTION:
62911.59
END DESCRIPTION:
XS GIS Cut Line= 5
  905694.7140245  808697.7074677   905760.339101  808718.0199426
  905807.2135704  808741.4571773  905849.4014122  808774.2697155
  905886.9016022  808811.7699056
#Sta/Elev= 30
       0 1943.63    3.93 1937.57    6.09 1935.68   13.63 1928.37   21.12    1917
   36.61 1890.72   37.89 1889.26   39.81 1884.14   45.15  1866.4      48 1865.74
   49.98 1864.24   53.33 1864.46   59.99 1864.16   61.56 1864.29    62.1 1864.19
   71.13 1863.73   86.75 1863.99   108.2 1866.55  114.42 1866.91  122.37 1867.94
  167.56 1876.87  173.01 1877.37   175.1 1877.48  180.26 1878.21  188.35 1879.59
  191.58 1880.52  201.96 1883.87  204.99 1884.69  223.62 1890.89  227.58 1892.11
#Mann= 3 , 0 , 0
       0     .08       0   45.15     .05       0   108.2     .08       0
Bank Sta=45.15,108.2
Exp/Cntr=0.3,0.1

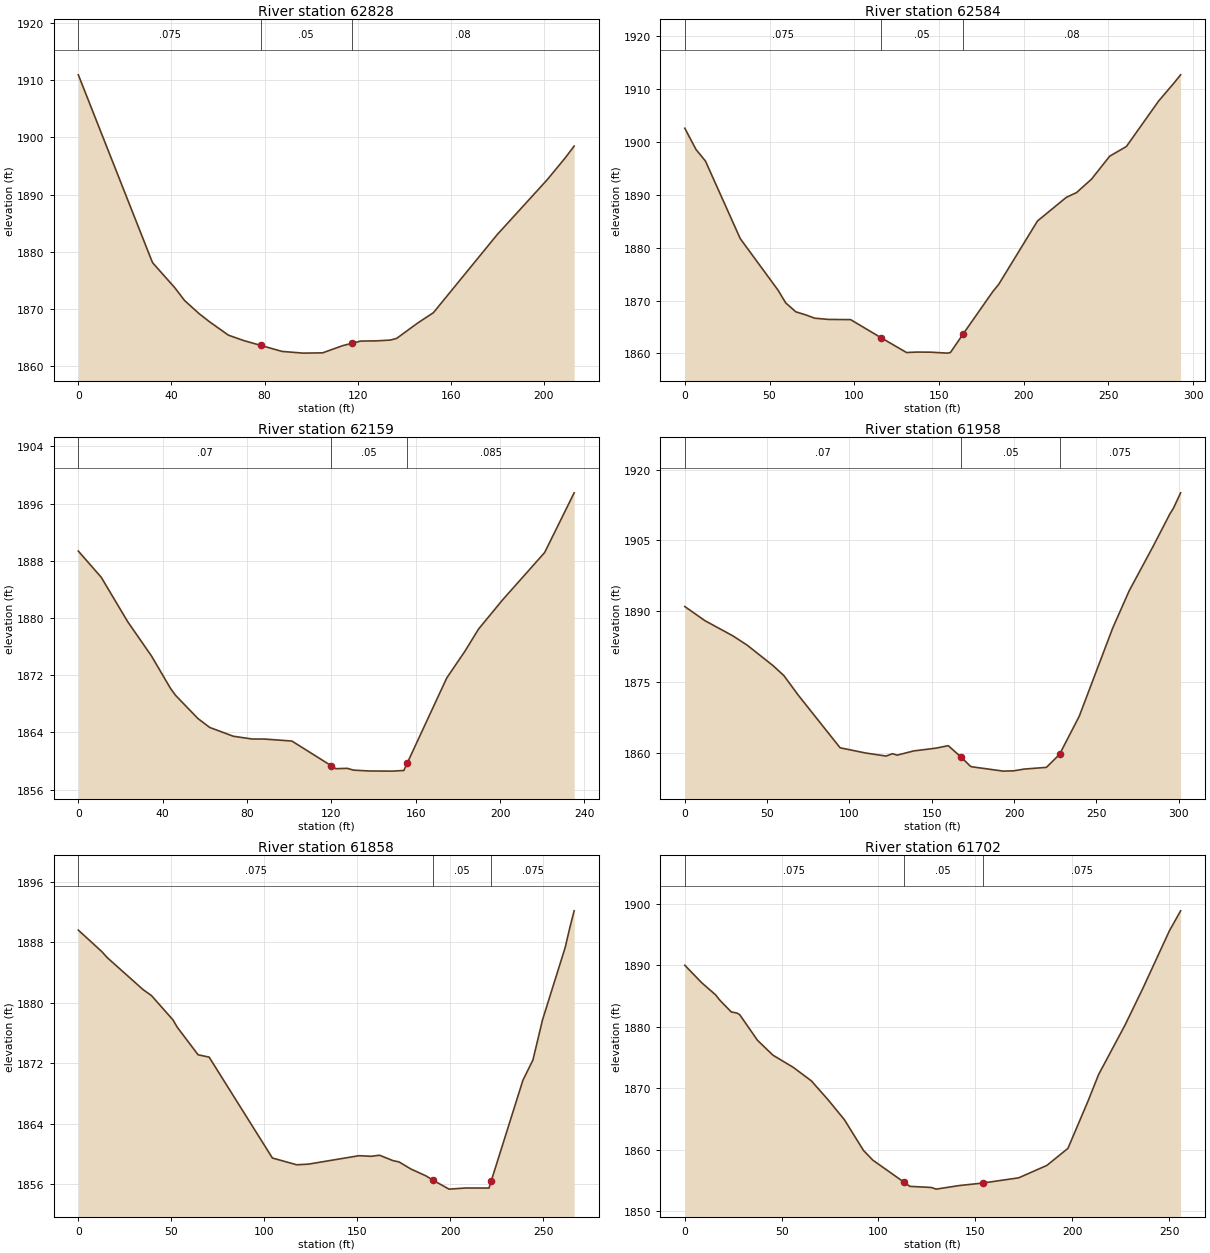
Type RM Length L Ch R = 1 ,62828   ,236.64,244.11,245.37
BEGIN DESCRIPTION:
62750.08
END DESCRIPTION:
XS GIS Cut Line= 5
  905665.0262461  808869.5825705  905719.7141512  808883.6455258
  905741.5884939  808883.6455258  905805.6517026   808878.957874
  905875.9634066  808882.0826338
#Sta/Elev= 25
       0 1910.98   31.55 1878.38      32    1878   41.34 1873.71   45.64 1871.42
    51.9 1869.11   56.47 1867.66   64.47 1865.35   70.96 1864.41   78.34 1863.56
   87.49  1862.5   96.59  1862.2  104.93 1862.25  113.76 1863.54  117.49 1863.92
  121.25 1864.31  128.14 1864.35     134 1864.49  136.71 1864.78  145.94 1867.53
  152.49 1869.28  179.79 1882.92  201.31 1892.56   209.2 1896.46  212.96 1898.49
#Mann= 3 , 0 , 0
       0    .075       0   78.34     .05       0  117.49     .08       0
Bank Sta=78.34,117.49
Exp/Cntr=0.3,0.1

Type RM Length L Ch R = 1 ,62584   ,401.65,424.79,439.93
BEGIN DESCRIPTION:
62505.97
END DESCRIPTION:
XS GIS Cut Line= 6
  905657.2138345  809105.5198577   905721.276019  809121.1446809
  905771.2762723  809124.2704648  905850.9643041  809124.2704648
   905890.026362  809128.9581166  905933.7760716  809166.4572824
#Sta/Elev= 29
       0 1902.56    6.65 1898.53   12.18 1896.37   32.75  1881.7    55.1 1871.94
    59.6 1869.55   65.56 1867.87   71.36  1867.3   76.68 1866.67    84.7 1866.44
   97.89  1866.4  116.04 1862.94  130.93 1860.18  136.77 1860.27  145.18 1860.25
  154.94 1860.07  156.77 1860.17  164.29 1863.68  181.78 1871.68  185.29 1873.06
  208.21 1885.04  225.21  1889.5  231.23  1890.4  240.12 1892.95  250.78 1897.27
  260.68 1899.11  279.68 1907.69  288.37 1910.95  292.69 1912.65
#Mann= 3 , 0 , 0
       0    .075       0  116.04     .05       0  164.29     .08       0
Bank Sta=116.04,164.29
Exp/Cntr=0.3,0.1

Type RM Length L Ch R = 1 ,62159   ,177.34,200.97,204.86
BEGIN DESCRIPTION:
62081.18
END DESCRIPTION:
XS GIS Cut Line= 4
  905574.4010429  809493.0197729  905638.4642516  809516.4580317
  905747.8390376  809552.3953298  905799.4011588   809547.707678
#Sta/Elev= 26
       0 1889.36   10.85  1885.7    23.4 1879.49   34.64 1874.71   43.72 1870.15
   46.08 1869.19   56.75 1865.93    62.3 1864.69   73.49 1863.46   82.47 1863.07
   88.07 1863.07  101.27 1862.79     120 1859.32   122.1 1858.92  127.57 1858.97
  130.47 1858.72  137.78  1858.6  148.94 1858.58  154.35 1858.67   155.91859.658
   174.7 1871.61  183.34 1875.36  189.78 1878.45  201.16 1882.53  221.13 1889.16
  235.12 1897.51
#Mann= 3 , 0 , 0
       0     .07       0     120     .05       0   155.9    .085       0
Bank Sta=120,155.9
Exp/Cntr=0.3,0.1

Type RM Length L Ch R = 1 ,61958   ,31.8,99.74,154.05
BEGIN DESCRIPTION:
61880.21
END DESCRIPTION:
XS GIS Cut Line= 6
  905497.8387951  809608.6451027  905524.4018137  809657.0824641
    905555.65146  809682.0825907  905618.1517767  809719.5827808
  905700.9635441  809749.2705592  905738.4637341  809774.2696617
#Sta/Elev= 30
       0 1891.02   12.23 1888.03   29.18 1884.82   37.88 1882.85   53.71 1878.48
   60.15 1876.42   69.02 1872.22   94.35 1861.12  109.77 1860.02  122.27 1859.37
   126.2 1859.87  128.97 1859.56  139.09 1860.46  152.49 1861.04  160.04 1861.57
     168  1859.1  173.54  1857.2  174.36  1857.1  193.43 1856.18  199.96 1856.25
  206.06 1856.61  219.68 1856.98  227.65 1859.73  239.66 1867.84  259.91 1886.45
  269.96 1894.36  284.67 1903.89  294.64 1910.61  296.85 1911.85  301.19 1915.09
#Mann= 3 , 0 , 0
       0     .07       0     168     .05       0  227.65    .075       0
Bank Sta=168,227.65
Exp/Cntr=0.3,0.1

Type RM Length L Ch R = 1 ,61858   ,26.83,156.52,198.76
BEGIN DESCRIPTION:
61780.47
END DESCRIPTION:
XS GIS Cut Line= 6
  905482.2139719  809614.8956464  905490.0263835  809653.9577043
  905529.0884413   809714.895129  905558.7762198  809743.0200154
  905574.4010429  809763.3324903  905579.0886947  809850.8329337
#Sta/Elev= 30
       0 1889.59   12.66 1886.74   15.47 1885.97   34.83 1881.72   39.35 1880.93
    50.9 1877.71   53.21 1876.74   64.38 1873.11    70.3  1872.8  104.32 1859.46
  117.39 1858.57  123.59 1858.65  150.85 1859.77  157.41 1859.69  161.91 1859.83
  169.21 1859.11  172.37 1858.95  178.74 1858.01  186.79 1857.11  190.79 1856.51
  199.27 1855.35  208.27  1855.5  220.73 1855.49  221.97 1856.46  238.97 1869.75
  244.33 1872.41  249.49 1877.72  261.71 1887.32  264.23 1889.98   266.5 1892.14
#Mann= 3 , 0 , 0
       0    .075       0  190.79     .05       0  221.97    .075       0
Bank Sta=190.79,221.97
Exp/Cntr=0.3,0.1

Type RM Length L Ch R = 1 ,61702   ,425.59,410.51,347.47
BEGIN DESCRIPTION:
61623.95
END DESCRIPTION:
XS GIS Cut Line= 6
  905465.0262568  809613.3327545  905466.5891488  809650.8329445
  905482.2139719  809683.6454827  905393.1516608  809785.2078572
  905380.6515974  809802.3955723  905375.9639457  809827.3946748
#Sta/Elev= 30
       0 1889.99     8.8 1887.12   15.85 1885.19   18.02 1884.33   23.99 1882.39
   26.97 1882.21   28.37 1881.94   37.53 1877.78   45.51 1875.36   55.95 1873.39
   65.35 1871.18   73.88 1868.14   82.41 1864.86   92.27 1859.86   97.06 1858.29
  112.921854.758  116.22 1854.02  127.28 1853.84  129.76 1853.57  141.66 1854.15
  153.88 1854.56  172.41 1855.41  186.95 1857.43  197.82  1860.2  208.27 1867.95
  213.65 1872.21  227.27 1880.24  236.52 1886.24  250.18 1895.57     256 1898.84
#Mann= 3 , 0 , 0
       0    .075       0  112.92     .05       0  153.88    .075       0
Bank Sta=112.92,153.88
Exp/Cntr=0.3,0.1

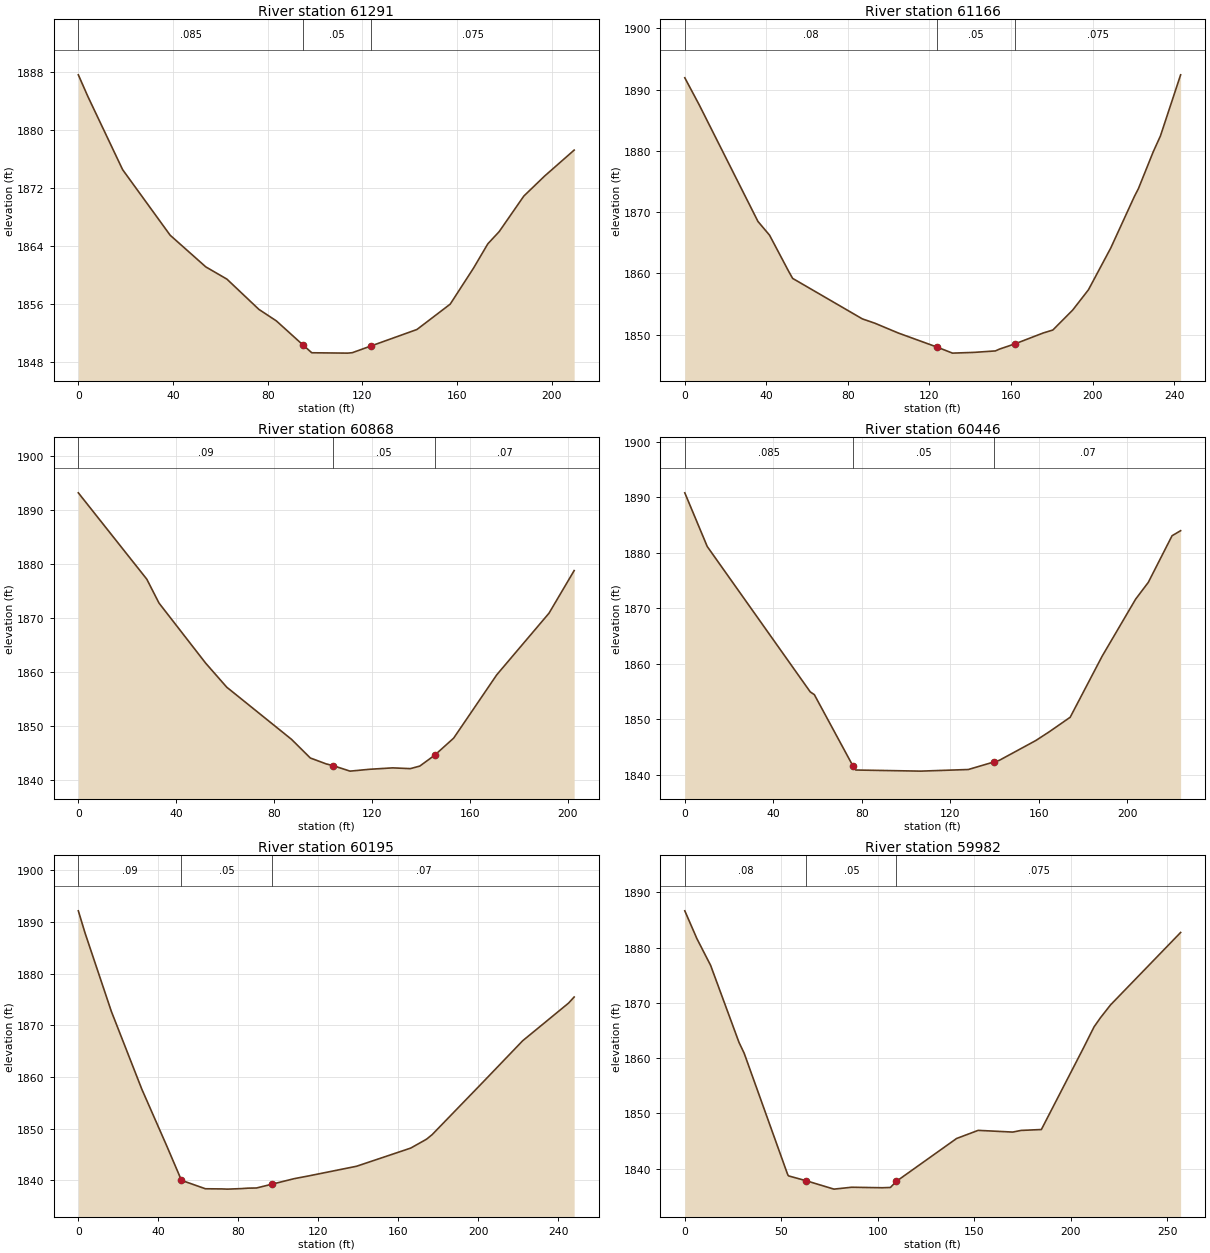
Type RM Length L Ch R = 1 ,61291   ,73.24,125.64,165.77
BEGIN DESCRIPTION:
61213.44
END DESCRIPTION:
XS GIS Cut Line= 6
  905075.9634497   809622.708058   905054.089107   809658.645356
  905046.2766954  809678.9578309  905044.7138035  809708.6456094
  905044.7138035  809782.0830974  905032.2137401  809822.7080472
#Sta/Elev= 21
       0 1887.65    4.03 1884.66   18.72 1874.56   38.81 1865.51   53.87 1861.14
    62.8 1859.45   76.29 1855.28   83.67 1853.69   94.911850.371   98.64 1849.29
  113.85 1849.24  115.77  1849.3  123.591850.218  143.07  1852.5  157.13    1856
     167 1860.98  173.04 1864.33  177.83 1866.01  188.25 1870.92  196.96 1873.66
  209.51 1877.26
#Mann= 3 , 0 , 0
       0    .085       0   94.91     .05       0  123.59    .075       0
Bank Sta=94.91,123.59
Exp/Cntr=0.3,0.1

Type RM Length L Ch R = 1 ,61166   ,259.71,297.91,321.96
BEGIN DESCRIPTION:
61087.80
END DESCRIPTION:
XS GIS Cut Line= 6
  905024.4013286  809596.1450394  904986.9011385  809630.5204696
  904936.9008852  809683.6454827  904911.9017827  809702.3950656
   904883.775872  809753.9571868  904857.2138776  809766.4572501
#Sta/Elev= 25
       0 1891.94    7.16 1887.46   35.87 1868.49   41.58 1866.24   50.87 1860.39
    52.9 1859.19   87.09 1852.58   93.18 1851.88  104.82 1850.26  123.85 1847.96
   131.3 1846.99  141.85 1847.11  152.34 1847.35  154.46 1847.66  162.01 1848.51
  175.81 1850.28  180.52 1850.76  190.26 1854.02  197.97 1857.32  208.94 1864.16
  220.53 1872.57  222.47 1873.82   229.8 1879.88  233.28 1882.43   243.2 1892.42
#Mann= 3 , 0 , 0
       0     .08       0  123.85     .05       0  162.01    .075       0
Bank Sta=123.85,162.01
Exp/Cntr=0.3,0.1

Type RM Length L Ch R = 1 ,60868   ,440.8,421.56,391.82
BEGIN DESCRIPTION:
60789.89
END DESCRIPTION:
XS GIS Cut Line= 5
  904932.2142576  809383.6449868  904871.2758087  809400.8327019
  904830.6508589  809413.3327652  904802.5259724  809430.5204803
  904750.9638513  809468.0196462
#Sta/Elev= 25
       0 1893.17   27.97  1877.2   32.95 1872.79   51.99 1861.69   60.62 1857.23
   63.32 1856.25    87.1 1847.58   94.76 1844.14   101.4 1843.02   101.7    1843
  103.88 1842.72  105.82 1842.47   110.7 1841.75  111.05 1841.71  118.94 1842.05
  127.98  1842.3  128.45 1842.31  135.63 1842.17  138.78 1842.56  139.47 1842.64
  145.56 1844.65  153.32 1847.81  170.92 1859.52  192.28 1870.92  202.54 1878.79
#Mann= 3 , 0 , 0
       0     .09       0  103.88     .05       0  145.56     .07       0
Bank Sta=103.88,145.56
Exp/Cntr=0.3,0.1

Type RM Length L Ch R = 1 ,60446   ,344.22,250.98,181.32
BEGIN DESCRIPTION:
60368.33
END DESCRIPTION:
XS GIS Cut Line= 6
  904590.0259199  809103.9579899  904525.9637354  809135.2076362
  904500.9636087  809152.3953513  904482.2140258   809174.269694
  904465.0263107  809203.9574725  904446.2767277  809260.2072454
#Sta/Elev= 18
       0 1890.77   10.15 1881.11   56.69 1854.96   58.53 1854.47      76 1841.62
   77.22 1840.91  106.57 1840.71   128.1    1841  139.84 1842.38  142.06 1842.64
  158.58 1846.21  164.73  1847.8  174.13  1850.4  188.55 1861.37  203.71 1871.65
  209.42 1874.66  220.16 1883.05  224.03 1883.96
#Mann= 3 , 0 , 0
       0    .085       0      76     .05       0  139.84     .07       0
Bank Sta=76,139.84
Exp/Cntr=0.3,0.1

Type RM Length L Ch R = 1 ,60195   ,249.96,212.9,125.81
BEGIN DESCRIPTION:
60117.34
END DESCRIPTION:
XS GIS Cut Line= 6
  904229.0890234  809043.0205652  904244.7138465  809097.7074462
  904260.3386697  809153.9572191  904279.0892768   809211.769884
  904279.0892768  809238.3329027  904277.5263848  809283.6455043
#Sta/Elev= 28
       0 1892.13    3.37 1887.83   16.52 1872.68   31.77 1857.63   44.24 1846.66
   51.57 1840.03   56.67 1839.34   56.88 1839.31   63.55  1838.4   71.77 1838.37
   74.49 1838.33   76.15 1838.35   81.36 1838.43      85 1838.52   89.09 1838.55
   97.09 1839.31  108.01 1840.36  115.25 1840.89  139.12 1842.75  166.19 1846.26
  173.42 1847.83  174.27 1848.03  176.03 1848.59  176.89 1848.85   202.6 1859.12
  222.18 1867.01  245.13 1874.29  247.93 1875.47
#Mann= 3 , 0 , 0
       0     .09       0   51.57     .05       0   97.09     .07       0
Bank Sta=51.57,97.09
Exp/Cntr=0.3,0.1

Type RM Length L Ch R = 1 ,59982   ,296.18,307.85,313.51
BEGIN DESCRIPTION:
59904.44
END DESCRIPTION:
XS GIS Cut Line= 6
  904005.6517995  809207.0822322  904063.4634402  809232.0823589
   904107.214174  809258.6453776  904133.7761685  809282.0826123
  904171.2763585  809302.3950872  904232.2137832  809324.2704541
#Sta/Elev= 24
       0 1886.66    6.28 1881.62   13.38 1876.79   28.06 1862.87   30.79 1860.86
   53.18 1839.05   53.52 1838.78   53.83 1838.66   62.99 1837.78   77.31 1836.27
   86.48 1836.61  102.27 1836.52  106.57 1836.57  109.62 1837.67  140.88 1845.44
  152.07 1846.91  169.96  1846.6  174.32  1846.9  184.81 1847.06  206.53 1861.76
  212.12 1865.65  215.44  1867.3  220.68 1869.63  256.99 1882.74
#Mann= 3 , 0 , 0
       0     .08       0   62.99     .05       0  109.62    .075       0
Bank Sta=62.99,109.62
Exp/Cntr=0.3,0.1

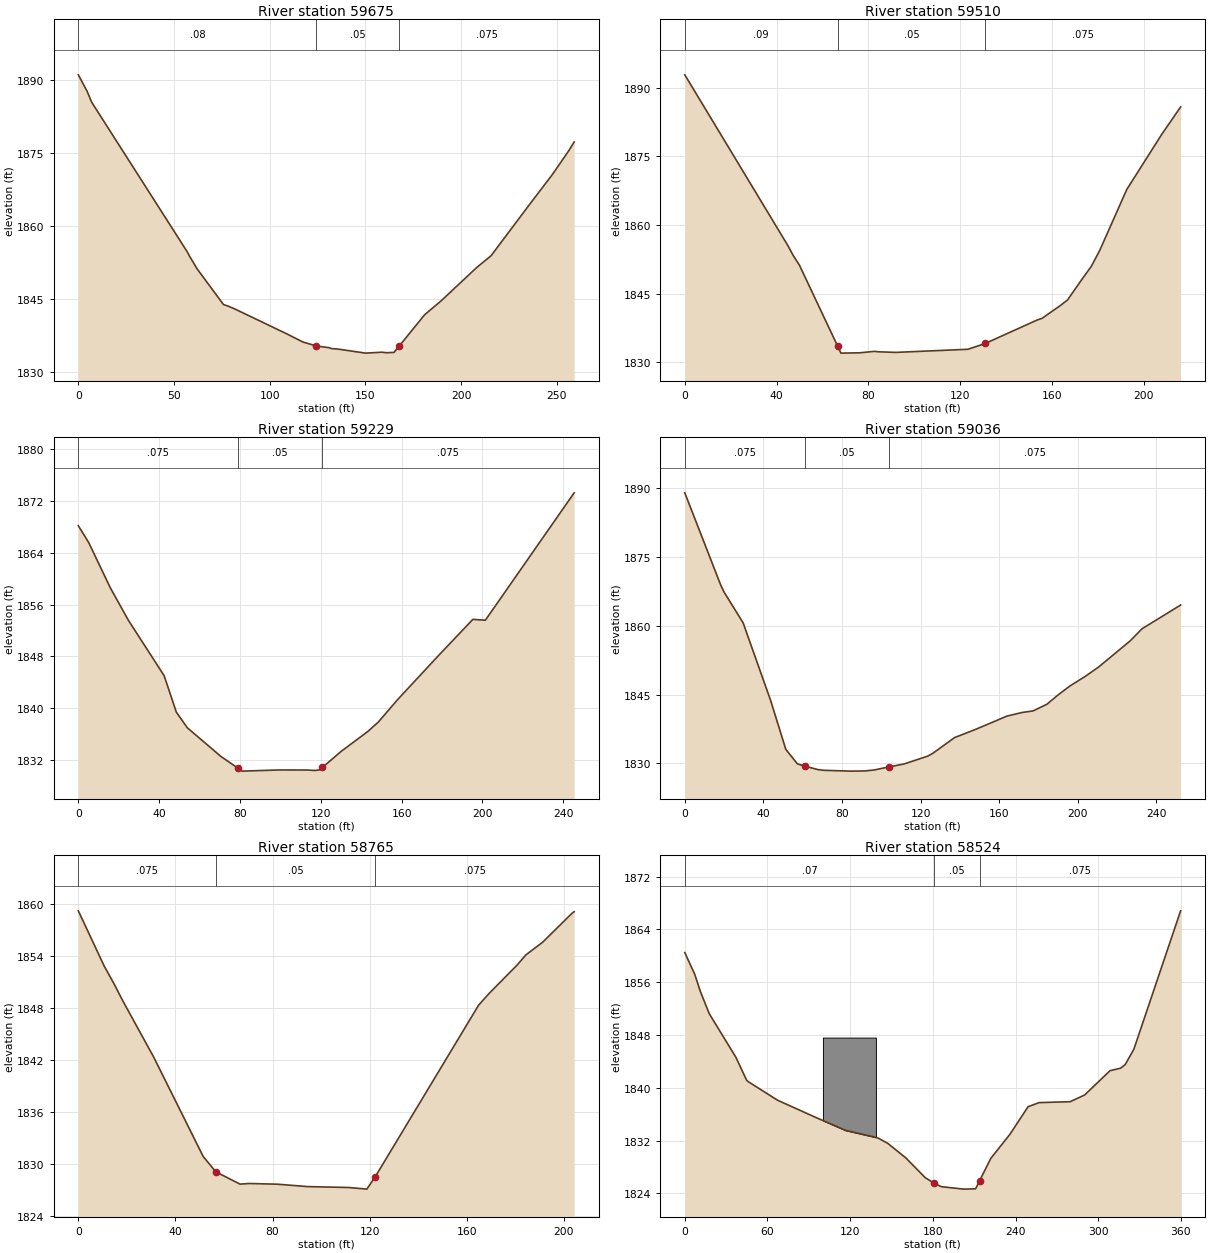
Type RM Length L Ch R = 1 ,59675   ,106.18,164.08,203.25
BEGIN DESCRIPTION:
59596.59
END DESCRIPTION:
XS GIS Cut Line= 6
  903877.5264063  809425.8328286  903907.2141848  809480.5197095
   903938.463831  809514.8951397  903985.3393246  809536.7705066
  904004.0889075  809550.8324378  904055.6510287  809605.5203429
#Sta/Elev= 28
       0 1891.01    4.55 1887.66    6.98 1885.38   56.83 1854.69   58.22 1853.67
   62.06 1851.15   75.84 1843.81   78.22  1843.5   81.91 1842.88  108.68 1837.84
  117.28 1836.13  124.35 1835.31  131.03 1834.95  132.35 1834.76  135.11  1834.7
  150.14 1833.84  158.57 1834.03  161.07 1833.92  164.92 1833.99  167.69 1835.33
  180.92 1841.73  189.57  1844.6  208.18 1851.46  215.57 1853.83  235.35 1864.19
   247.8 1870.62   256.2 1875.42  259.01 1877.22
#Mann= 3 , 0 , 0
       0     .08       0  124.35     .05       0  167.69    .075       0
Bank Sta=124.35,167.69
Exp/Cntr=0.3,0.1

Type RM Length L Ch R = 1 ,59510   ,288.5,281.41,273.47
BEGIN DESCRIPTION:
59432.51
END DESCRIPTION:
XS GIS Cut Line= 6
  903794.7136147   809472.707298  903816.5889816  809538.3323744
  903824.4013932  809575.8325645  903822.8385012  809599.2697991
  903836.9014565  809630.5204696  903852.5262796  809678.9578309
#Sta/Elev= 22
       0 1892.77   45.07 1855.37   47.17 1853.39   50.03 1851.15   66.641833.508
   68.06    1832   76.25 1832.07   82.74 1832.39   84.42 1832.29   91.94 1832.16
  123.41 1832.84  130.97 1834.11  153.68 1839.25  155.72 1839.59   163.8 1842.43
  166.84 1843.61  172.82 1847.91  177.26    1851  180.89 1854.45  192.65 1867.73
  207.82 1879.71  216.13 1885.76
#Mann= 3 , 0 , 0
       0     .09       0   66.64     .05       0  130.97    .075       0
Bank Sta=66.64,130.97
Exp/Cntr=0.3,0.1

Type RM Length L Ch R = 1 ,59229   ,232.85,192.82,125.13
BEGIN DESCRIPTION:
59151.10
END DESCRIPTION:
XS GIS Cut Line= 5
  903521.2761374  809466.4577784  903544.7133721  809530.5199629
  903544.7133721  809572.7078047   903568.151631  809653.9577043
  903582.2135621  809702.3950656
#Sta/Elev= 23
       0  1868.2    5.17 1865.58   15.81 1858.61   24.79 1853.57   42.47 1845.01
   48.49 1839.38   53.93 1836.96    70.5 1832.54   79.161830.666   81.08 1830.25
   99.25 1830.43  113.37 1830.42  117.16 1830.35  119.36 1830.44  120.761830.814
   130.1 1833.31  143.26 1836.38  148.54 1837.86  157.82 1841.24  177.95 1848.02
  195.26 1853.72  201.46 1853.59   245.4 1873.29
#Mann= 3 , 0 , 0
       0    .075       0   79.16     .05       0  120.76    .075       0
Bank Sta=79.16,120.76
Exp/Cntr=0.3,0.1

Type RM Length L Ch R = 1 ,59036   ,292.42,270.86,232.51
BEGIN DESCRIPTION:
58958.28
END DESCRIPTION:
XS GIS Cut Line= 4
  903310.3389769  809580.5202162  903346.2762749   809622.708058
   903399.401288  809661.7701158  903500.9636625  809744.5829074
#Sta/Elev= 30
       0 1889.05   18.33 1868.87   20.07 1867.32   29.69 1860.67   43.66 1843.77
   51.43 1833.04   57.33 1829.89   60.99  1829.4   67.75 1828.64   70.72 1828.48
   84.47  1828.3   91.67 1828.34   96.35 1828.55  104.14 1829.23   111.7 1829.87
  123.69 1831.58  126.33 1832.21  137.36 1835.63  147.74 1837.36  164.05 1840.32
  171.79 1841.11  177.28 1841.44   184.3 1842.89  189.89 1844.89  196.02 1846.88
  203.96 1849.01  210.73 1851.05  226.74 1856.74  232.71 1859.36   252.4 1864.56
#Mann= 3 , 0 , 0
       0    .075       0   60.99     .05       0  104.14    .075       0
Bank Sta=60.99,104.14
Exp/Cntr=0.3,0.1

Type RM Length L Ch R = 1 ,58765   ,223.74,241.51,216
BEGIN DESCRIPTION:
58687.42
END DESCRIPTION:
XS GIS Cut Line= 5
  903211.9013621  809875.8330604  903257.2139637  809886.7702317
  903310.3389769  809900.8321629  903374.4011614  809922.7075298
  903408.7765916  809928.9580735
#Sta/Elev= 21
       0 1859.26   10.64 1852.88   14.89 1850.72   18.27 1848.87   31.02 1842.35
   51.43 1830.84   56.64 1829.07   66.59 1827.65   70.47 1827.72   82.09 1827.64
   94.51 1827.36  111.27 1827.26  118.81 1827.07  122.11 1828.42  164.88 1848.36
  169.26 1849.73  180.65 1852.97  184.31 1854.16  191.23 1855.63  203.43 1859.01
   204.2 1859.16
#Mann= 3 , 0 , 0
       0    .075       0   56.64     .05       0  122.11    .075       0
Bank Sta=56.64,122.11
Exp/Cntr=0.3,0.1

Type RM Length L Ch R = 1 ,58524   ,82.94,132.4,191.93
BEGIN DESCRIPTION:
58445.91
END DESCRIPTION:
XS GIS Cut Line= 6
  903105.6513358  810044.5823792  903213.4642541   810121.144627
  903241.5891406  810132.0828226  903310.3389769  810138.3323421
  903382.2135729  810128.9580628  903435.3385861  810111.7703477
#Sta/Elev= 30
       0  1860.5     7.2 1857.22   11.31  1854.6   17.77 1851.23   37.06 1844.64
   44.81 1841.18   45.78 1840.97   67.44 1838.11   95.97 1835.43  116.62 1833.56
  139.91 1832.43  147.28 1831.59   160.5 1829.36  174.35 1826.41   180.9 1825.54
  186.12 1825.02  202.45 1824.65  211.01  1824.7  213.891825.903  222.09 1829.33
  235.89 1832.95  249.09 1837.14  257.03 1837.76  279.61  1837.9  290.21 1838.93
  308.53  1842.6  316.21 1842.98  319.55 1843.53  325.85 1845.86  359.77 1866.83
#Mann= 3 , 0 , 0
       0     .07       0   180.9     .05       0  213.89    .075       0
#Block Obstruct= 1 ,-1
  100.22  138.661847.621
Bank Sta=180.9,213.89
Exp/Cntr=0.3,0.1

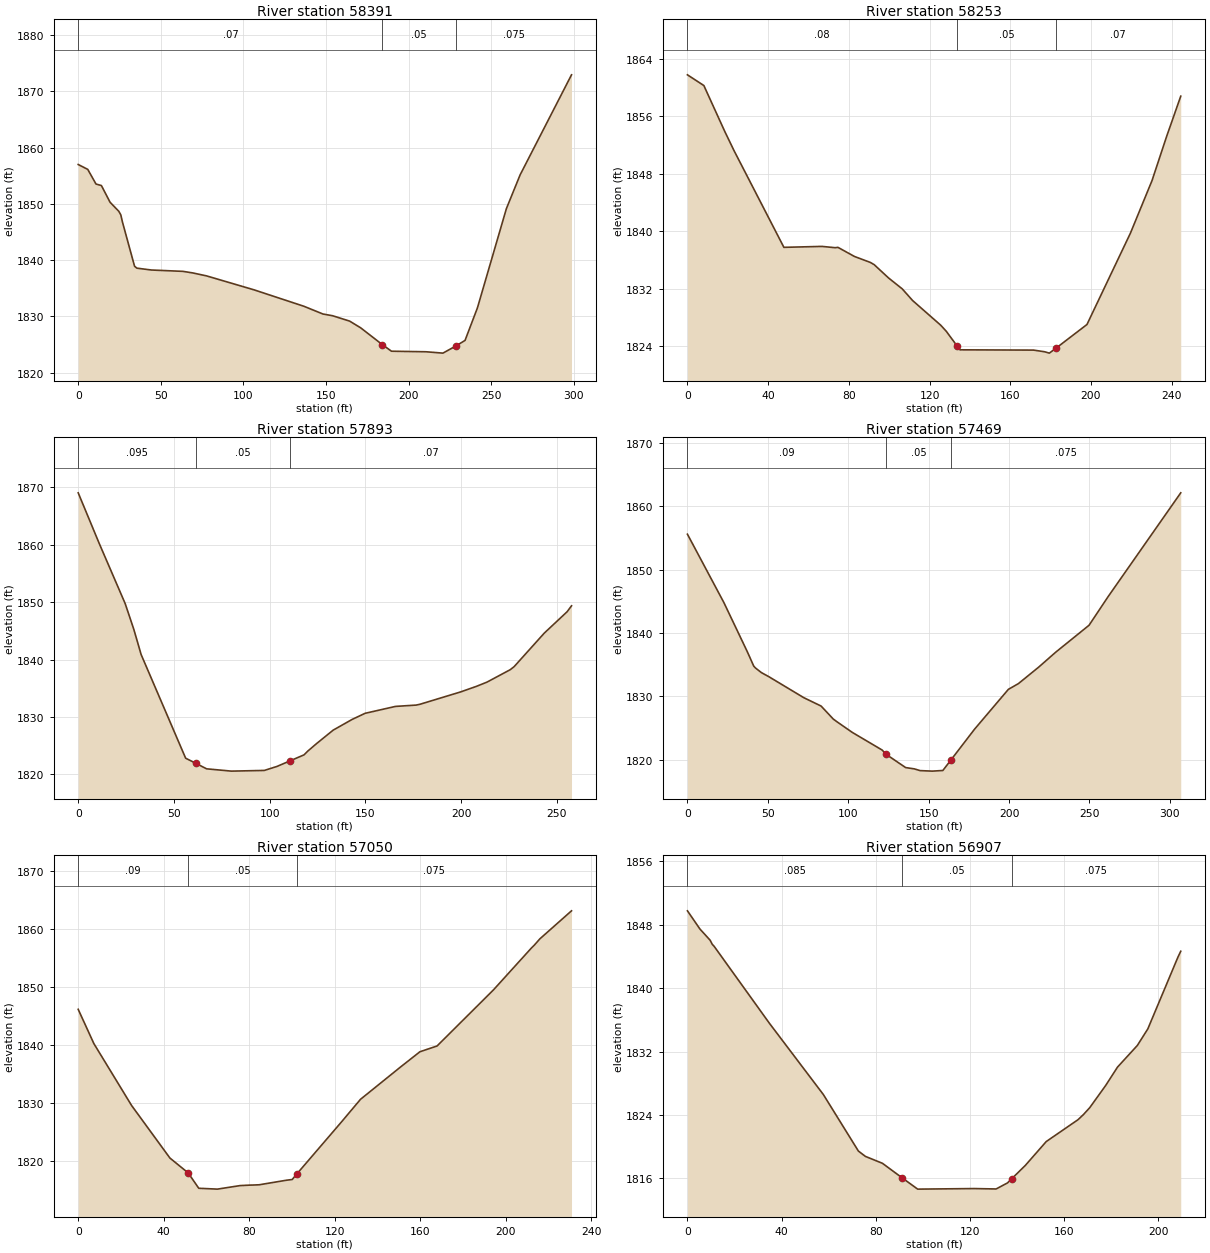
Type RM Length L Ch R = 1 ,58391   ,55.83,138.88,184.88
BEGIN DESCRIPTION:
58313.51
END DESCRIPTION:
XS GIS Cut Line= 4
  903057.2139745  810096.1455245   903194.713647  810230.5204373
  903219.7137737  810263.3329755  903252.5263119  810319.5827484
#Sta/Elev= 30
       0 1856.99    5.77 1856.13   10.78 1853.52   14.05 1853.25    19.3 1850.28
   24.57 1848.68   25.79 1848.05   26.78 1846.78   34.12 1838.91   35.53 1838.57
   44.38 1838.24   63.48    1838   69.39 1837.72   77.66  1837.2  106.42 1834.72
  136.61  1831.8  148.19 1830.42  154.07 1830.11  164.31 1829.16  170.98 1827.97
  184.16 1824.97  189.64 1823.81  210.61 1823.71  220.79 1823.47  228.761824.759
  234.18 1825.73  241.66  1831.5  259.21 1849.15  267.52 1855.15  298.63 1872.93
#Mann= 3 , 0 , 0
       0     .07       0  184.16     .05       0  228.76    .075       0
Bank Sta=184.16,228.76
Exp/Cntr=0.3,0.1

Type RM Length L Ch R = 1 ,58253   ,346.95,359.31,326.7
BEGIN DESCRIPTION:
58174.63
END DESCRIPTION:
XS GIS Cut Line= 6
  903022.8385443  810105.5198039  903049.4015629  810157.0829492
  903068.1511458  810189.8954875  903068.1511458  810221.1451337
   903066.589278  810266.4577353  903044.7139111  810335.2075716
#Sta/Elev= 27
       0 1861.74    8.14 1860.25   18.48 1853.88   23.13 1851.18   47.81 1837.75
    66.7 1837.88   73.28  1837.7    74.6 1837.75    82.8 1836.48   90.69 1835.65
   92.58 1835.34    99.7 1833.49  106.49 1831.97  111.59 1830.36  125.56 1826.92
   128.3 1826.08  133.68 1824.03  135.07  1823.5  171.57 1823.46  177.04 1823.23
   179.4 1823.04  182.551823.696  198.04 1827.02  219.61 1839.74   230.3 1847.04
  237.49 1853.14  244.53 1858.77
#Mann= 3 , 0 , 0
       0     .08       0  133.68     .05       0  182.55     .07       0
Bank Sta=133.68,182.55
Exp/Cntr=0.3,0.1

Type RM Length L Ch R = 1 ,57893   ,440.17,424.62,427.86
BEGIN DESCRIPTION:
57815.32
END DESCRIPTION:
XS GIS Cut Line= 6
  902715.0266609  810133.6446904  902705.6513574  810189.8954875
  902708.7761172  810227.3946533  902708.7761172  810275.8330389
  902732.2133519  810350.8323947  902733.7762439  810386.7696927
#Sta/Elev= 29
       0    1869   10.98 1860.19   24.52 1849.74   29.06 1845.23   32.87 1840.86
   56.11 1822.83   61.551821.919   67.06 1820.98   79.98 1820.58    97.2  1820.7
  103.76 1821.39  110.58 1822.36  117.94 1823.41  119.96 1824.08  124.45 1825.36
  133.16 1827.71  143.09 1829.58  149.85 1830.64  165.71 1831.84  176.48 1832.07
  178.48 1832.21  199.81 1834.37  207.98 1835.33  213.53 1836.07  225.64 1838.23
  227.65 1838.75  243.44  1844.6  255.34 1848.31  257.64 1849.34
#Mann= 3 , 0 , 0
       0    .095       0   61.55     .05       0  110.58     .07       0
Bank Sta=61.55,110.58
Exp/Cntr=0.3,0.1

Type RM Length L Ch R = 1 ,57469   ,456.05,418.29,371.89
BEGIN DESCRIPTION:
57390.70
END DESCRIPTION:
XS GIS Cut Line= 6
  902302.5266191  810258.6453237  902310.3390307  810310.2074449
  902310.3390307  810350.8323947  902330.6515056  810411.7698194
  902333.7762654  810483.6454396  902347.8392207  810560.2076875
#Sta/Elev= 28
       0 1855.61   22.68  1844.8    37.2 1837.06   41.23 1834.77   42.37 1834.46
   45.94 1833.75   50.73 1833.08   72.35 1829.78   83.15 1828.45   90.66 1826.41
   92.78 1826.01  102.53 1824.29  121.11  1821.5  123.55 1820.83  135.72 1818.73
  141.04 1818.53  144.74 1818.25  152.32 1818.17  158.86 1818.27  163.971819.962
  178.61 1824.81   199.6 1831.09  205.86    1832  218.45  1834.6  228.98 1836.95
  249.78 1841.22  261.74 1845.78  306.82 1862.15
#Mann= 3 , 0 , 0
       0     .09       0  123.55     .05       0  163.97    .075       0
Bank Sta=123.55,163.97
Exp/Cntr=0.3,0.1

Type RM Length L Ch R = 1 ,57050   ,88.05,143.28,203.44
BEGIN DESCRIPTION:
56972.41
END DESCRIPTION:
XS GIS Cut Line= 5
  901896.2760969  810521.1456297  901938.4639387  810561.7705795
  901952.5258698  810578.9572704  901990.0260599  810638.3328273
   902043.151073    810697.70736
#Sta/Elev= 28
       0 1846.21    7.32  1840.3   24.98 1829.61   42.89 1820.55   51.42 1817.99
   56.37 1815.34   57.21 1815.32   58.57  1815.3   65.08 1815.19   75.37 1815.78
   75.67  1815.8   80.77 1815.89   81.38 1815.89   84.64 1815.94   92.081816.399
   97.45 1816.73  100.06 1816.85  102.33 1817.85  123.01 1826.74  132.02 1830.69
     151 1836.34  159.79 1838.89  167.79 1839.88  194.12 1849.54  211.96  1856.8
  213.25 1857.27  215.89 1858.37  230.67  1863.2
#Mann= 3 , 0 , 0
       0     .09       0   51.42     .05       0  102.33    .075       0
Bank Sta=51.42,102.33
Exp/Cntr=0.3,0.1

Type RM Length L Ch R = 1 ,56907   ,59.29,125.09,193
BEGIN DESCRIPTION:
56829.14
END DESCRIPTION:
XS GIS Cut Line= 5
  901855.6511471  810527.3951492  901835.3386722  810563.3324473
  901821.2767411  810607.0821569  901816.5890893  810638.3328273
  901799.4013742  810727.3951385
#Sta/Elev= 27
       0 1849.75    5.32 1847.45    9.64 1846.04   10.51 1845.54   11.37 1845.26
   34.78 1835.58   57.74 1826.57   72.62 1819.44   75.59 1818.77   82.82  1817.9
   91.281816.046   97.79 1814.64  121.78 1814.71  131.12 1814.66  135.93 1815.42
  137.721815.941  143.52 1817.63   152.4 1820.64  165.95 1823.41  168.22 1824.05
  170.86 1824.91  177.57 1827.68   182.7 1830.04  191.09 1832.76  195.55 1834.85
  208.35 1843.91  209.54 1844.65
#Mann= 3 , 0 , 0
       0    .085       0   91.28     .05       0  137.72    .075       0
Bank Sta=91.28,137.72
Exp/Cntr=0.3,0.1