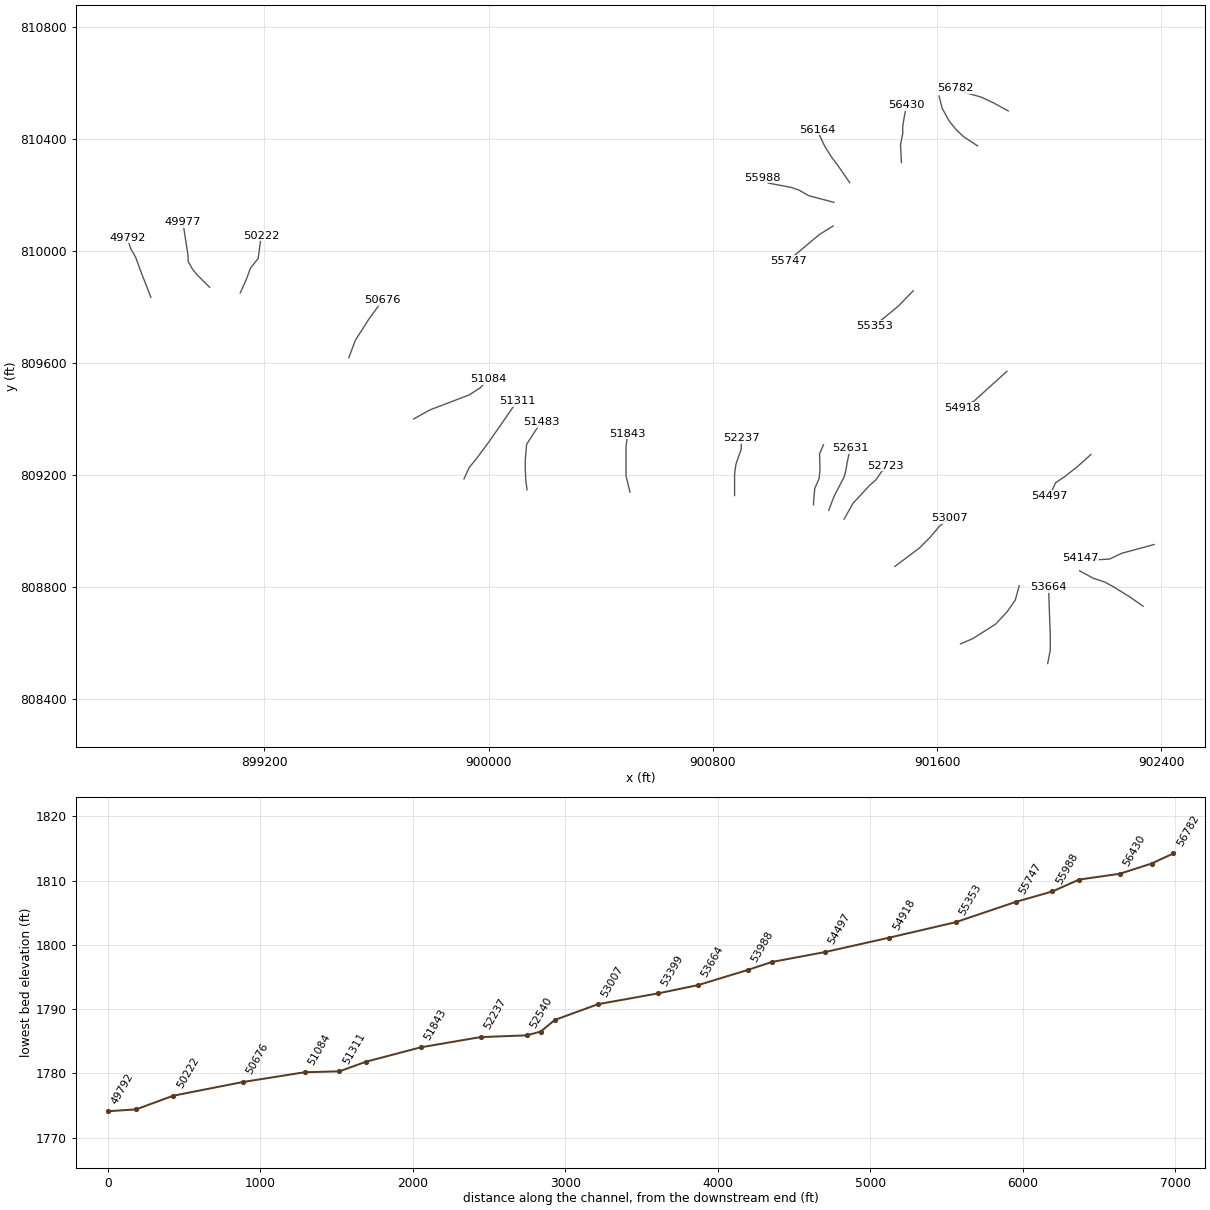
HEC-RAS study lds_big_laurel_crk.prj: lds_big_laurel_crk

--- lds_big_laurel_crk.g20 (geometry) --- (continued)

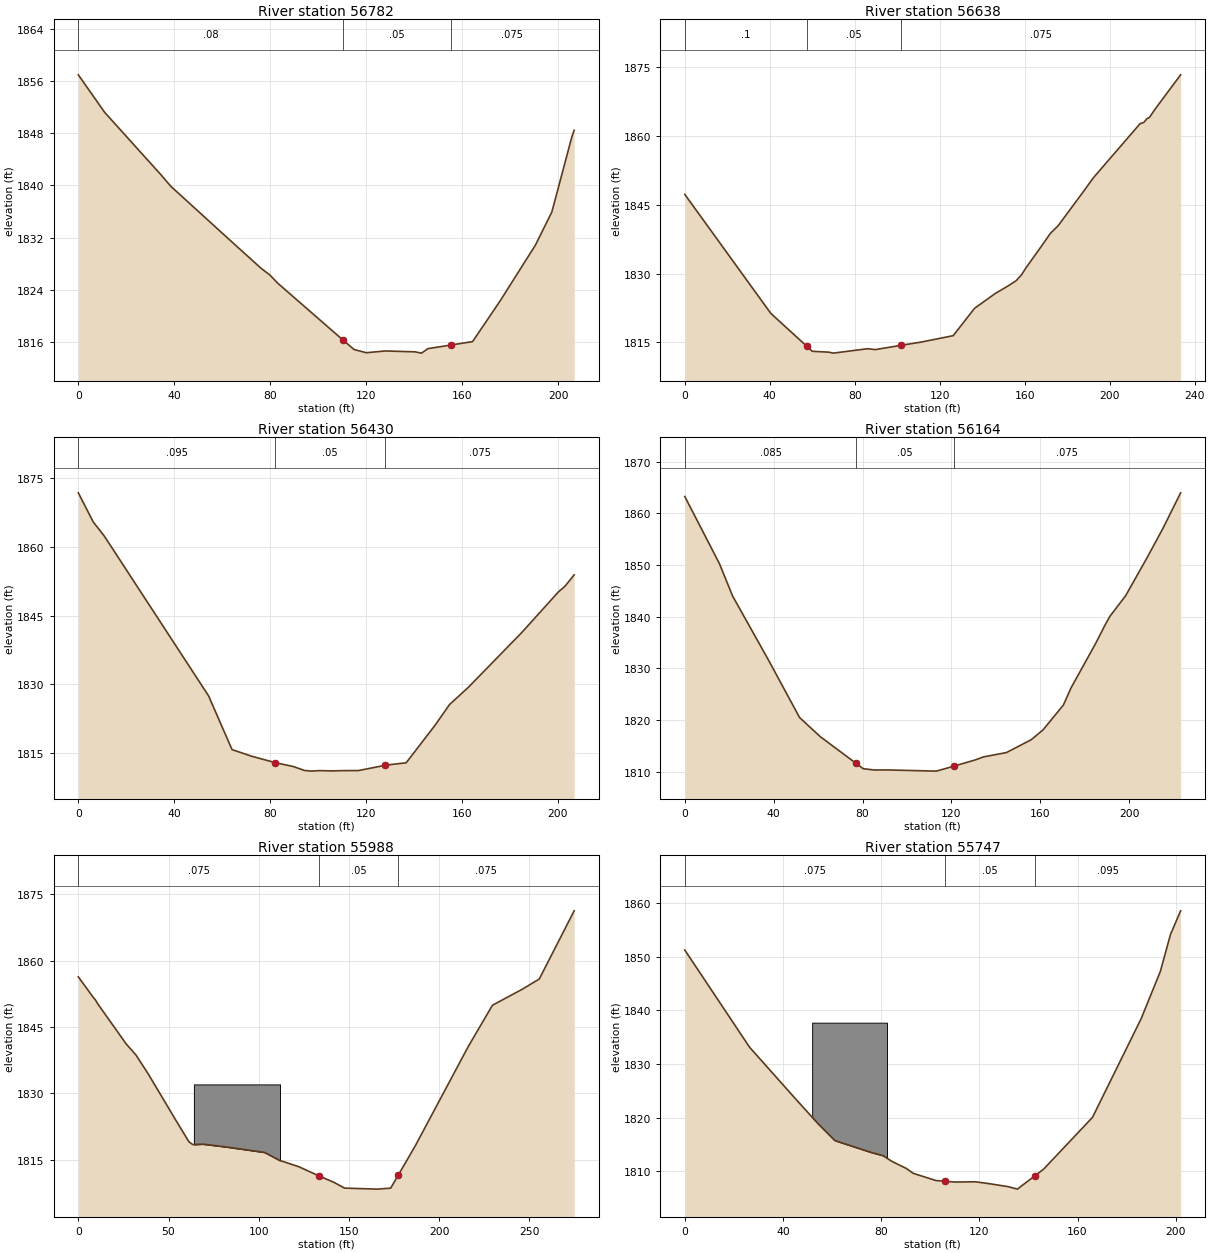
Type RM Length L Ch R = 1 ,56782   ,163.14,143.92,108.11
BEGIN DESCRIPTION:
56704.04
END DESCRIPTION:
XS GIS Cut Line= 5
  901854.0892793  810499.2702628  901799.4013742  810528.9580412
  901755.6516646  810549.2705161  901704.0885192  810563.3324473
  901665.0264614  810580.5201624
#Sta/Elev= 24
       0 1857.02   10.97 1851.25   34.42 1841.65   38.56 1839.87   62.23 1831.91
   76.13 1827.27   79.84 1826.22   83.13 1824.96  110.46 1816.17  114.91 1814.77
  120.01 1814.28   122.5 1814.37  127.82 1814.55  128.08 1814.55  140.26 1814.42
     143 1814.22  145.66 1814.91  155.091815.458  164.25 1815.99  175.74 1822.25
  190.45 1830.84  197.28 1835.92  205.63 1847.49  206.58 1848.49
#Mann= 3 , 0 , 0
       0     .08       0  110.46     .05       0  155.09    .075       0
Bank Sta=110.46,155.09
Exp/Cntr=0.3,0.1

Type RM Length L Ch R = 1 ,56638   ,260.92,208.34,147.42
BEGIN DESCRIPTION:
56560.12
END DESCRIPTION:
XS GIS Cut Line= 6
   901744.713469  810374.2696294  901694.7142399  810407.0821676
  901668.1512212  810432.0822943  901643.1510945  810463.3329647
  901618.1509679  810508.6455663  901607.2137965  810552.3952759
#Sta/Elev= 28
       0 1847.26   40.46 1821.32   57.351814.167   60.02 1813.04    67.8 1812.85
   69.85 1812.64   86.04  1813.6   89.71 1813.41  101.781814.342  111.48 1815.07
  126.33 1816.45  136.35 1822.41  146.11 1825.65  151.98 1827.25  155.88 1828.41
  158.51 1829.75  160.62 1831.28  167.94 1836.02  171.96 1838.71  175.74 1840.44
  188.25 1848.29  192.24 1850.86  214.29  1862.7  215.99 1862.94  217.59 1863.82
  218.58 1863.99  221.53 1865.98  233.35 1873.34
#Mann= 3 , 0 , 0
       0      .1       0   57.35     .05       0  101.78    .075       0
Bank Sta=57.35,101.78
Exp/Cntr=0.3,0.1

Type RM Length L Ch R = 1 ,56430   ,226.96,265.96,309.62
BEGIN DESCRIPTION:
56351.77
END DESCRIPTION:
XS GIS Cut Line= 6
  901472.8388838  810314.8950967   901469.714124  810378.9572812
  901477.5265355  810418.0203632  901477.5265355  810444.5823577
  901483.7760551  810482.0825477  901491.5884667  810519.5827377
#Sta/Elev= 29
       0 1871.84    6.23 1865.47   10.91 1862.34   54.45  1827.4   54.91 1826.81
   64.13 1815.75   72.16 1814.33   82.16  1812.9   89.74 1812.05   94.33  1811.2
   97.32 1811.05  100.45 1811.16  105.81  1811.1   110.3 1811.16  110.53 1811.16
  116.82 1811.17  128.02 1812.32  130.54  1812.5  136.78 1812.87  148.75 1821.02
  154.88  1825.6  162.68 1829.34   183.5 1840.52  183.77 1840.66  184.98 1841.31
  200.38 1850.25  201.94 1850.93  202.98 1851.41  206.86 1853.92
#Mann= 3 , 0 , 0
       0    .095       0   82.16     .05       0  128.02    .075       0
Bank Sta=82.16,128.02
Exp/Cntr=0.3,0.1

Type RM Length L Ch R = 1 ,56164   ,127.46,176.07,237.29
BEGIN DESCRIPTION:
56085.82
END DESCRIPTION:
XS GIS Cut Line= 5
  901288.4637177  810243.0205006  901246.2758759  810303.9579253
  901222.8386412  810335.2075716  901199.4014065  810372.7077616
    901171.27652  810432.0822943
#Sta/Elev= 26
       0 1863.26   15.59 1850.27    21.5 1844.03   38.09 1831.29   51.67  1820.5
   60.98 1816.81   77.141811.626   80.29 1810.62   85.24 1810.37    91.5 1810.38
  113.18 1810.15  121.161811.122  130.78 1812.33  134.37  1812.9  144.73 1813.74
  155.88 1816.23  161.13  1818.1  170.35 1822.93  173.82 1826.27  184.84 1834.82
  188.98 1838.31  191.26 1840.08  198.39 1844.09   208.1  1851.5  215.21 1857.15
   223.1 1863.97
#Mann= 3 , 0 , 0
       0    .085       0   77.14     .05       0  121.16    .075       0
Bank Sta=77.14,121.16
Exp/Cntr=0.3,0.1

Type RM Length L Ch R = 1 ,55988   ,120.6,240.41,285.94
BEGIN DESCRIPTION:
55909.75
END DESCRIPTION:
XS GIS Cut Line= 6
  901232.2139447  810172.7077724  901143.1516335   810196.145007
  901107.2133113   810216.457482  901080.6513169  810225.8327855
  900997.8385253  810241.4576086  900975.9641826  810260.2071915
#Sta/Elev= 27
       0 1856.31     8.2 1851.71     9.4 1851.13   10.95  1850.1   26.52 1841.14
   31.99 1838.61   38.79 1834.32   53.68 1824.13   61.35 1818.97   63.49 1818.37
   69.02 1818.48   82.27 1817.82  103.18 1816.61   111.5 1814.81   122.3 1813.35
  133.52 1811.26  141.62 1809.84  147.56 1808.53  165.51  1808.3   173.1 1808.52
  177.381811.525  186.63 1818.02  216.09 1840.55  229.49 1849.89  245.96 1853.49
  255.44 1855.82  274.77 1871.24
#Mann= 3 , 0 , 0
       0    .075       0  133.52     .05       0  177.38    .075       0
#Block Obstruct= 1 ,-1
   64.04  111.781831.985
Bank Sta=133.52,177.38
Exp/Cntr=0.3,0.1

Type RM Length L Ch R = 1 ,55747   ,381.97,394.48,384.36
BEGIN DESCRIPTION:
55669.33
END DESCRIPTION:
XS GIS Cut Line= 4
  901229.0891849   810088.333113  901179.0889316  810057.0824425
  901110.3390953  809999.2697776  901069.7141455  809964.8953716
#Sta/Elev= 29
       0 1851.21   26.38 1833.11   43.95 1824.09   46.85 1822.61   54.33 1818.83
   58.96 1816.71   61.04 1815.75   62.99 1815.44   75.87 1813.52    80.8 1812.91
   84.25 1811.87   90.26 1810.52   93.08 1809.61  102.33 1808.27  105.821808.143
  110.03 1807.99  114.27 1808.01  118.35 1808.04  124.39 1807.66  131.77 1807.13
   135.5 1806.67  142.571809.133  146.24 1810.41  148.79 1811.65  166.11 1820.04
  185.93 1838.42  193.74 1847.21  197.88 1854.11  202.01 1858.51
#Mann= 3 , 0 , 0
       0    .075       0  105.82     .05       0  142.57    .095       0
#Block Obstruct= 1 ,-1
   51.89   82.371837.678
Bank Sta=105.82,142.57
Exp/Cntr=0.3,0.1

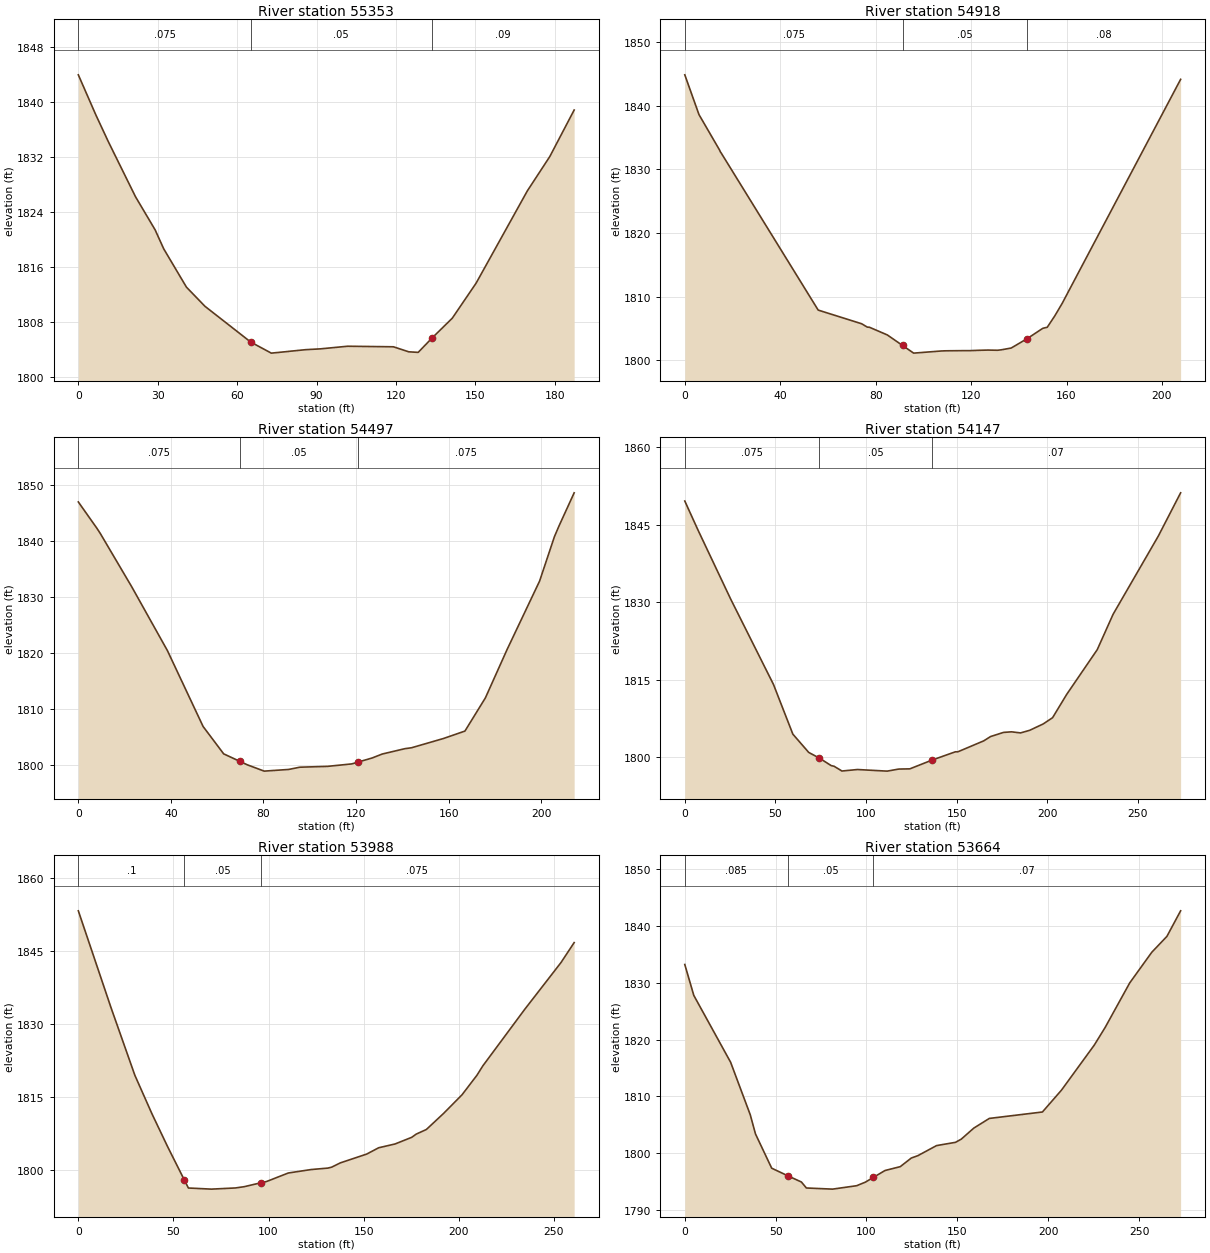
Type RM Length L Ch R = 1 ,55353   ,437.91,434.4,436.55
BEGIN DESCRIPTION:
55274.85
END DESCRIPTION:
XS GIS Cut Line= 3
  901515.0267255  809857.0824533  901460.3388204  809800.8326804
   901375.964161  809732.0828441
#Sta/Elev= 27
       0 1843.92    6.57 1838.14    11.3 1834.24   21.58 1826.23   29.01 1821.41
   32.26 1818.65   40.84 1813.09   47.83 1810.31   65.11 1805.12   72.21 1803.65
   72.89 1803.51   78.45 1803.72   80.36  1803.8   80.51 1803.81   80.68 1803.81
   85.83 1804.01   91.47 1804.13   101.7 1804.51  119.02 1804.43  124.82  1803.7
  128.38 1803.62  133.55 1805.68  141.25 1808.58  150.27 1813.68  169.61 1827.07
   178.1 1832.06  187.29 1838.81
#Mann= 3 , 0 , 0
       0    .075       0   65.11     .05       0  133.55     .09       0
Bank Sta=65.11,133.55
Exp/Cntr=0.3,0.1

Type RM Length L Ch R = 1 ,54918   ,422.05,421.11,423.43
BEGIN DESCRIPTION:
54840.45
END DESCRIPTION:
XS GIS Cut Line= 3
  901849.4016275  809569.5830449  901732.2134057  809463.3330186
  901688.4636961  809439.8947597
#Sta/Elev= 29
       0 1844.89    5.95 1838.63   14.65 1833.01   14.89 1832.77   14.96 1832.75
   15.29 1832.57   55.91 1807.88   74.13 1805.73    76.5  1805.2   77.39 1805.18
   84.89 1803.97   91.281802.312   95.91 1801.11  107.62 1801.45  108.93 1801.47
   110.7 1801.48  116.83  1801.5  119.51  1801.5  122.79 1801.55  127.17 1801.59
  131.06 1801.56  132.64 1801.63   136.8 1801.91  143.55  1803.4  150.04 1805.01
  151.92 1805.18   155.1 1806.98  158.18 1808.94  207.82 1844.18
#Mann= 3 , 0 , 0
       0    .075       0   91.28     .05       0  143.55     .08       0
Bank Sta=91.28,143.55
Exp/Cntr=0.3,0.1

Type RM Length L Ch R = 1 ,54497   ,371.2,349.95,302.54
BEGIN DESCRIPTION:
54419.33
END DESCRIPTION:
XS GIS Cut Line= 5
  902149.4010993  809272.7073087  902102.5266299  809230.5204911
  902057.2140283  809194.5821689  902022.8385981  809171.1449342
  902000.9642554  809124.2704648
#Sta/Elev= 27
       0 1846.92    7.91 1842.29     9.5 1841.29   23.18  1831.7   38.51 1820.37
   53.91 1806.84    62.8 1801.95   69.871800.598      73    1800    80.3 1798.87
   90.89 1799.17    95.7 1799.57   107.7 1799.72  118.16 1800.16   120.9 1800.49
  126.97 1801.22  131.29 1801.92  141.12 1802.88  143.96 1803.04  157.74 1804.69
  167.04 1806.02  175.87 1811.94  185.21 1820.54   199.3  1832.8   205.7 1840.72
  207.69 1842.64  214.23 1848.55
#Mann= 3 , 0 , 0
       0    .075       0   69.87     .05       0   120.9    .075       0
Bank Sta=69.87,120.9
Exp/Cntr=0.3,0.1

Type RM Length L Ch R = 1 ,54147   ,201.67,159,68.69
BEGIN DESCRIPTION:
54069.39
END DESCRIPTION:
XS GIS Cut Line= 6
  902374.4012152  808950.8324701  902258.7758854  808919.5828238
  902216.5890677  808899.2703489  902194.7137009  808897.7074569
  902158.7764028  808896.1455891  902110.3390415  808903.9580007
#Sta/Elev= 30
       0 1849.62    7.27 1844.01   25.35 1830.61    48.9 1814.13   59.62 1804.48
   68.38 1800.94   74.31 1799.83   80.77 1798.39   82.37 1798.26    86.7 1797.34
   95.28 1797.63  111.64 1797.32  118.08 1797.72  124.16 1797.76  136.19 1799.43
  149.27 1801.06  150.65 1801.06  164.92 1803.18  168.73 1804.02  175.88 1804.82
  180.29 1804.93  185.24 1804.72  190.26 1805.22  197.71 1806.45  202.92 1807.67
  210.76 1812.21  227.56 1820.84  236.32  1827.7  261.26 1842.84  273.56 1851.21
#Mann= 3 , 0 , 0
       0    .075       0   74.31     .05       0  136.19     .07       0
Bank Sta=74.31,136.19
Exp/Cntr=0.3,0.1

Type RM Length L Ch R = 1 ,53988   ,378.8,324.58,205.39
BEGIN DESCRIPTION:
53910.39
END DESCRIPTION:
XS GIS Cut Line= 6
  902335.3391574  808730.5200059  902288.4636638  808763.3325442
  902230.6509989  808799.2698422  902199.4013526  808816.4575573
  902157.2135108  808830.5205127  902108.7761495  808857.0825071
#Sta/Elev= 30
       0 1853.34   17.12 1833.49   29.71 1819.51   38.72 1811.56   46.95  1804.8
   55.741797.944   57.86  1796.3   69.97 1796.07   82.55 1796.31   87.19 1796.57
   95.81 1797.36   98.99 1797.64  110.39 1799.39   122.4  1800.1  131.23  1800.4
  133.25  1800.6  137.73 1801.47  151.65 1803.29  157.89 1804.58   166.5 1805.36
  175.27 1806.73  177.63 1807.39  182.97 1808.34  191.98 1811.63  201.71 1815.48
  209.54 1819.49  212.67 1821.44  234.59 1833.02  253.74 1842.69  260.67  1846.8
#Mann= 3 , 0 , 0
       0      .1       0   55.74     .05       0   95.81    .075       0
Bank Sta=55.74,95.81
Exp/Cntr=0.3,0.1

Type RM Length L Ch R = 1 ,53664   ,317.42,265.14,125.95
BEGIN DESCRIPTION:
53585.81
END DESCRIPTION:
XS GIS Cut Line= 6
  901994.7137116  808525.8323649  902004.0890152  808574.2697263
  902004.0890152  808625.8328716  902002.5261232  808664.8949295
  902000.9642554   808710.207531  901997.8384714  808797.7079744
#Sta/Elev= 30
       0 1833.18    4.96 1827.75   25.22 1816.01   36.04 1806.77    38.9 1803.42
   47.82  1797.4    56.71796.062   64.18 1794.97   66.93 1793.92   81.31 1793.72
   94.59 1794.32   99.34 1794.94  103.721795.765  110.18 1796.99  118.59 1797.67
  124.66 1799.18  128.28  1799.6  138.58 1801.37     149 1801.94  152.16  1802.5
  159.06 1804.44   167.6 1806.14  196.83 1807.27  207.32 1811.11  225.38 1819.03
  231.31  1822.1  244.88 1829.95  256.99 1835.32  265.34 1838.12  272.89 1842.61
#Mann= 3 , 0 , 0
       0    .085       0    56.7     .05       0  103.72     .07       0
Bank Sta=56.7,103.72
Exp/Cntr=0.3,0.1

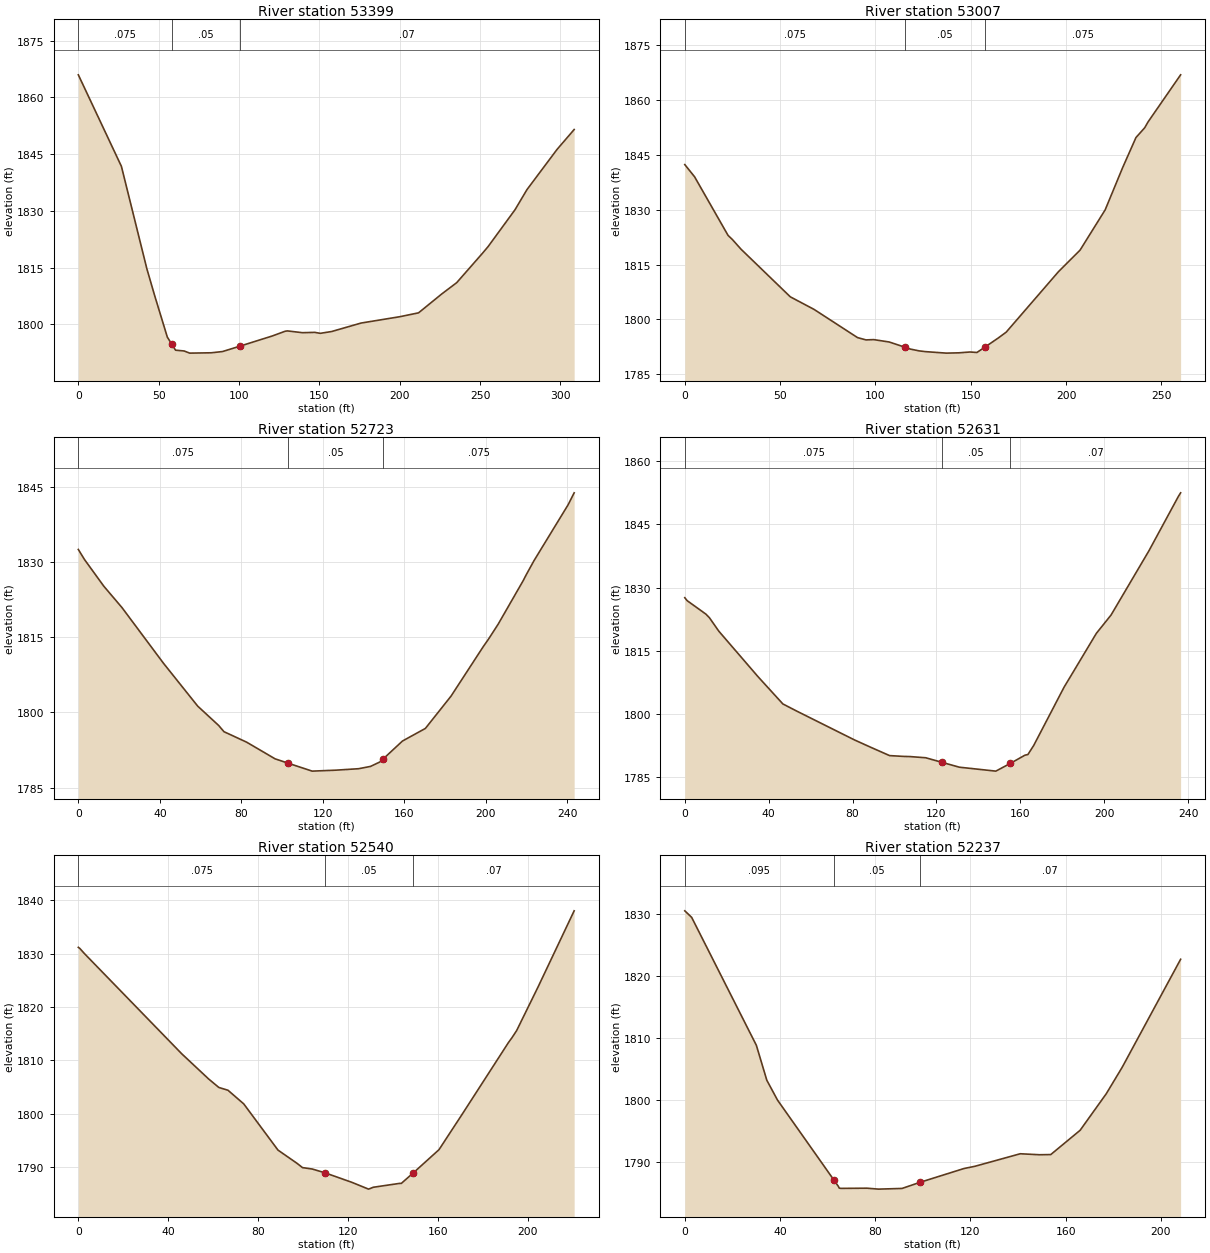
Type RM Length L Ch R = 1 ,53399   ,386.85,391.64,389.38
BEGIN DESCRIPTION:
53320.67
END DESCRIPTION:
XS GIS Cut Line= 6
  901683.7760443  808596.1450932  901727.5267781  808614.8946761
  901808.7766777  808666.4578215  901849.4016275   808710.207531
  901879.0883818  808752.3953728  901893.1513371   808803.957494
#Sta/Elev= 30
       0 1865.99   26.81  1841.8   42.66  1814.7    47.6 1807.49    55.4 1796.64
   58.241794.724    60.5  1793.2   65.82 1792.99   69.29 1792.42   82.73 1792.51
   89.78 1792.84  100.651794.275  120.75 1796.96  128.73 1798.21  130.16 1798.29
  139.53 1797.82  147.17 1797.91  150.53 1797.65  157.62 1798.13  175.97 1800.37
  200.24 1802.06  211.73 1803.07   226.2 1808.07  235.48 1811.05  251.67 1818.89
  255.12 1820.64  271.77 1830.33  279.18 1835.63   297.9 1846.26  308.57 1851.53
#Mann= 3 , 0 , 0
       0    .075       0   58.24     .05       0  100.65     .07       0
Bank Sta=58.24,100.65
Exp/Cntr=0.3,0.1

Type RM Length L Ch R = 1 ,53007   ,275.13,283.6,282.88
BEGIN DESCRIPTION:
52929.03
END DESCRIPTION:
XS GIS Cut Line= 6
  901449.4016491  808872.7073303  901511.9009416  808919.5828238
  901536.9010683  808938.3324067  901575.9641502  808977.3954887
  901607.2137965  809014.8946546  901643.1510945   809044.582433
#Sta/Elev= 30
       0 1842.37    5.14 1839.03   22.66 1823.01   25.08 1821.79   29.46 1819.22
   55.35 1806.16   67.77 1802.73   90.57 1795.01   95.01 1794.37   99.09 1794.45
  107.18  1793.8  115.24 1792.41  118.26 1791.86  122.97 1791.36  126.21 1791.16
  137.15 1790.75  143.66 1790.83  149.56 1791.06  153.22 1790.93  157.511792.428
  164.62 1794.97  168.58  1796.5  195.98 1813.05  207.31 1818.95   220.5    1830
  229.59 1841.48  236.62 1849.77  241.23 1852.47  242.96 1854.05  260.05 1866.95
#Mann= 3 , 0 , 0
       0    .075       0  115.24     .05       0  157.51    .075       0
Bank Sta=115.24,157.51
Exp/Cntr=0.3,0.1

Type RM Length L Ch R = 1 ,52723   ,75.57,92.1,123.03
BEGIN DESCRIPTION:
52645.42
END DESCRIPTION:
XS GIS Cut Line= 6
  901268.1512427  809041.4576732   901300.963781  809099.2703382
  901325.9639077  809125.8323326  901357.2135539  809160.2077629
  901382.2136806  809182.0831297  901416.5891108  809232.0823589
#Sta/Elev= 28
       0 1832.46    3.04 1830.45   12.49 1825.15   21.44 1820.87   41.83 1809.76
   58.61 1801.23   68.86 1797.39   71.46 1796.15   82.59 1794.06   96.55 1790.74
  102.95 1789.87  114.75 1788.29  126.31 1788.48  137.51 1788.77  143.38 1789.23
  147.91  1790.1  149.41 1790.65  159.06 1794.29   170.3  1796.8  182.93 1803.26
  198.73 1813.12  201.33 1814.63  206.02 1817.58  218.35 1826.29  219.62  1827.3
  223.58 1830.22  240.34 1841.37   243.3 1843.75
#Mann= 3 , 0 , 0
       0    .075       0  102.95     .05       0  149.41    .075       0
Bank Sta=102.95,149.41
Exp/Cntr=0.3,0.1

Type RM Length L Ch R = 1 ,52631   ,76.93,90.87,102.51
BEGIN DESCRIPTION:
52553.32
END DESCRIPTION:
XS GIS Cut Line= 6
  901213.4633376  809072.7073195  901232.2139447  809122.7075728
  901268.1512427  809191.4574091  901274.4017865  809214.8946438
  901279.0884141  809243.0205545  901290.0266096  809294.5826756
#Sta/Elev= 29
       0 1827.61    1.02 1826.97    1.49 1826.78   10.06 1823.72   11.74 1822.87
   16.23 1819.67   34.93 1808.88   46.78 1802.42    53.4 1800.72   80.92 1793.89
   88.34 1792.22   97.67 1790.17  104.35 1789.98  107.39 1789.94   114.9 1789.66
  122.781788.558  130.96 1787.42  148.34 1786.49  155.24 1788.32  162.22 1790.27
  163.64 1790.43  166.41 1792.58  180.93 1806.44  183.76 1808.77  196.27 1819.15
   203.3 1823.51  221.35 1838.73  235.46 1851.68  236.47 1852.48
#Mann= 3 , 0 , 0
       0    .075       0  122.78     .05       0  155.24     .07       0
Bank Sta=122.78,155.24
Exp/Cntr=0.3,0.1

Type RM Length L Ch R = 1 ,52540   ,290.86,303.51,280.58
BEGIN DESCRIPTION:
52462.45
END DESCRIPTION:
XS GIS Cut Line= 6
  901158.7764567  809093.0197944  901163.4641084  809150.8324593
  901179.0889316  809186.7697573  901182.2136914  809216.4575358
  901180.6518236  809274.2702007  901194.7137547  809307.0827389
#Sta/Elev= 26
       0  1831.2     .69 1830.98    2.78    1830      46 1811.26      58 1806.53
   62.51 1804.95    66.6 1804.42    73.6 1801.87   88.84 1793.21   97.19 1790.77
   99.75 1789.93  104.14 1789.66  109.58 1788.98  121.67 1787.18  129.13  1785.9
  131.24 1786.25  142.99 1786.98   143.7 1786.97  148.92  1788.9  160.47 1793.29
  170.85 1799.97  191.31 1813.32  192.96 1814.28  195.04 1815.62  204.61 1823.83
  220.61 1838.04
#Mann= 3 , 0 , 0
       0    .075       0  109.58     .05       0  148.92     .07       0
Bank Sta=109.58,148.92
Exp/Cntr=0.3,0.1

Type RM Length L Ch R = 1 ,52237   ,384.39,393.56,411.09
BEGIN DESCRIPTION:
52158.95
END DESCRIPTION:
XS GIS Cut Line= 6
  900877.5265678  809125.8323326  900877.5265678  809202.3956046
  900882.2142196  809236.7700107   900891.588499  809264.8948972
  900900.9638025  809289.8950238  900902.5266945  809330.5199736
#Sta/Elev= 22
       0 1830.56    2.89  1829.5   30.07 1808.84   34.45 1803.21   38.92 1800.02
    62.61787.114   64.46  1786.1   64.85 1785.81   65.47 1785.75   76.56 1785.78
   81.33 1785.63   91.25 1785.74   98.73 1786.72  117.29 1788.96  121.79 1789.31
   140.9 1791.34  149.02 1791.18  153.72 1791.21  166.05 1795.13  177.08 1801.06
  183.73 1805.31  208.26 1822.74
#Mann= 3 , 0 , 0
       0    .095       0    62.6     .05       0   98.73     .07       0
Bank Sta=62.6,98.73
Exp/Cntr=0.3,0.1

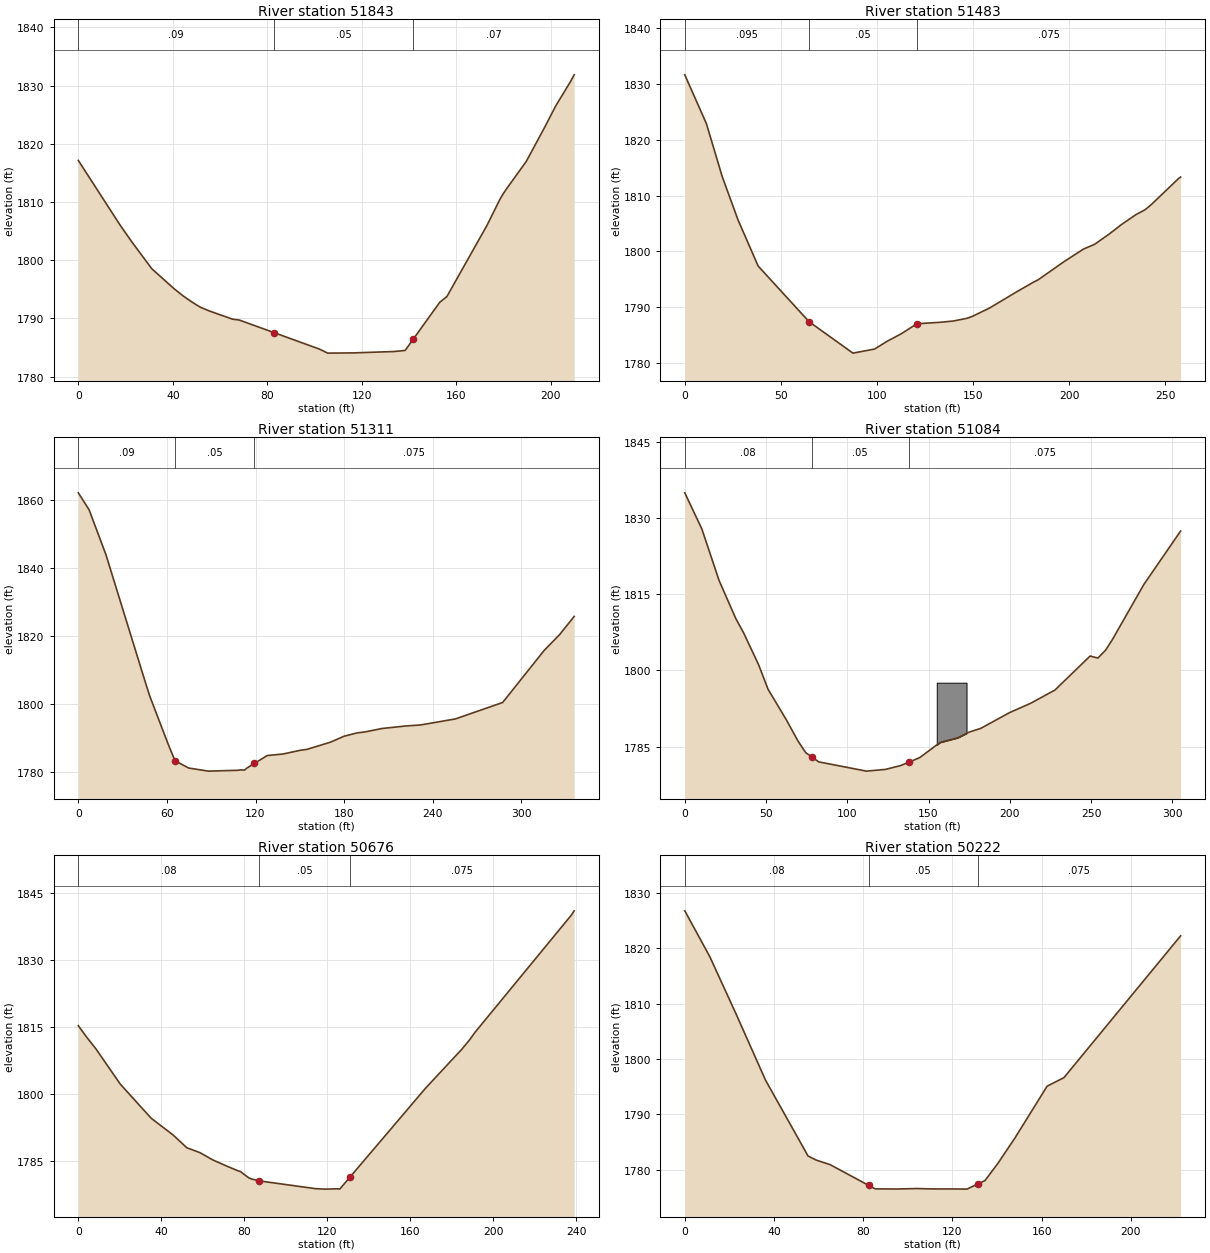
Type RM Length L Ch R = 1 ,51843   ,364.52,359.98,339.01
BEGIN DESCRIPTION:
51765.39
END DESCRIPTION:
XS GIS Cut Line= 6
  900504.0885839   809138.332396  900490.0266527  809196.1450609
  900490.0266527  809219.5822956  900490.0266527  809253.9577258
  900490.0266527  809299.2703274  900496.2761723  809346.1447968
#Sta/Elev= 29
       0 1817.14   17.63 1806.06   22.89 1803.01   31.09 1798.54   40.41 1795.14
   44.33 1793.87   48.06 1792.82   51.74  1791.9   55.58 1791.26   65.33 1789.86
   68.11 1789.72   82.94 1787.54  102.11 1784.72  105.59 1784.03  116.39 1784.07
  133.45  1784.3  138.35 1784.49  141.761786.415     153 1792.76  156.03 1793.75
     173 1805.98  178.51 1810.48   179.9 1811.43  181.31 1812.28  189.59 1816.94
  197.41 1822.82  202.09  1826.5  208.41 1830.72  209.91 1831.85
#Mann= 3 , 0 , 0
       0     .09       0   82.94     .05       0  141.76     .07       0
Bank Sta=82.94,141.76
Exp/Cntr=0.3,0.1

Type RM Length L Ch R = 1 ,51483   ,208.98,171.98,114.77
BEGIN DESCRIPTION:
51405.41
END DESCRIPTION:
XS GIS Cut Line= 6
  900136.9011436  809146.1448075  900132.2134919  809183.6449976
   900130.651624  809221.1451876   900130.651624  809252.3948338
  900135.3392758  809308.6456309   900186.901397  809388.3326386
#Sta/Elev= 29
       0 1831.64   11.23  1822.9   19.47 1813.41   27.71 1805.63   38.17 1797.38
   64.69  1787.4   87.47 1781.78   98.71 1782.51  105.46 1783.94  112.53 1785.23
  120.76 1787.04  133.36 1787.32  139.82 1787.54   146.8 1788.02   149.5 1788.35
   158.5 1789.85  172.74 1792.78  181.15 1794.45  183.77  1794.9  197.38 1798.19
  207.46 1800.43  213.19 1801.27  220.76 1803.11  227.35 1804.86  234.73  1806.6
  239.46 1807.47  242.55 1808.35   256.9 1813.07  257.95 1813.33
#Mann= 3 , 0 , 0
       0    .095       0   64.69     .05       0  120.76    .075       0
Bank Sta=64.69,120.76
Exp/Cntr=0.3,0.1

Type RM Length L Ch R = 1 ,51311   ,252.1,227.48,148.7
BEGIN DESCRIPTION:
51233.43
END DESCRIPTION:
XS GIS Cut Line= 6
  899911.9010277  809185.2078895  899930.6516348  809225.8328393
  899957.2136293  809258.6453776  899997.8385791  809313.3322585
  900030.6511173  809360.2077521  900100.9638456  809461.7701266
#Sta/Elev= 30
       0 1862.14     7.3 1857.15    18.7 1843.95   44.74 1807.35   48.39 1802.35
   60.44 1788.69   65.47 1783.35   74.76 1781.21   88.07  1780.3  108.25 1780.55
  109.91 1780.68  112.56 1780.59  114.07 1781.17  119.311782.573  127.93 1784.88
  138.81 1785.35  150.17 1786.41  154.85  1786.7  170.77 1788.81  179.98 1790.56
  188.91 1791.55  194.06 1791.82   205.6 1792.83  221.81 1793.58  231.71 1793.87
   255.4 1795.65  287.39 1800.48  315.52  1815.8  325.95 1820.43  335.83 1825.79
#Mann= 3 , 0 , 0
       0     .09       0   65.47     .05       0  119.31    .075       0
Bank Sta=65.47,119.31
Exp/Cntr=0.3,0.1

Type RM Length L Ch R = 1 ,51084   ,358.01,408.04,455.33
BEGIN DESCRIPTION:
51005.95
END DESCRIPTION:
XS GIS Cut Line= 5
  899732.2135134  809399.2698099  899791.5890703  809432.0823482
  899930.6516348  809485.2073613  899969.7136926   809510.207488
  899997.8385791  809541.4571342
#Sta/Elev= 30
       0    1835   10.55 1827.84   21.08 1817.74   31.37 1810.24   36.22 1807.39
   45.42 1801.13   51.22  1796.3   62.48 1790.28    69.7 1786.07   74.45 1783.79
   78.02 1782.99   82.44 1781.98  111.81 1780.16  123.49  1780.5  132.77 1781.25
  137.961781.927  144.54 1782.82   157.1 1785.81  167.94 1786.73  174.76 1787.82
  182.23  1788.6  199.98 1791.71  212.79 1793.52  227.83 1796.15  249.41 1802.84
  254.24 1802.44  259.04 1804.03  263.08 1806.05  282.45 1816.92  305.12 1827.47
#Mann= 3 , 0 , 0
       0     .08       0   78.02     .05       0  137.96    .075       0
#Block Obstruct= 1 ,-1
  155.04  173.37 1797.59
Bank Sta=78.02,137.96
Exp/Cntr=0.3,0.1

Type RM Length L Ch R = 1 ,50676   ,454.84,454.02,462.41
BEGIN DESCRIPTION:
50597.91
END DESCRIPTION:
XS GIS Cut Line= 5
  899500.9638779  809618.0204062  899524.4011126  809680.5196988
  899552.5259991  809724.2704325  899571.2766062  809753.9571868
  899621.2758353  809822.7080472
#Sta/Elev= 26
       0 1815.27    4.05 1812.68    8.55 1810.03    20.2 1802.18   35.15  1794.5
   45.61 1790.79   52.29  1787.9    58.6 1786.81   64.78 1785.18   71.58 1783.78
   76.76 1782.77   78.11 1782.57   82.02 1781.19   83.41 1780.91   87.21 1780.47
  114.21 1778.74  118.68 1778.63  124.79  1778.7  125.98 1778.65  130.88 1781.33
  167.29 1801.26  184.78    1810  188.58 1812.14  191.06 1813.75  237.68 1840.15
  238.88 1841.02
#Mann= 3 , 0 , 0
       0     .08       0   87.21     .05       0  130.88    .075       0
Bank Sta=87.21,130.88
Exp/Cntr=0.3,0.1

Type RM Length L Ch R = 1 ,50222   ,179.04,244.59,276.55
BEGIN DESCRIPTION:
50143.89
END DESCRIPTION:
XS GIS Cut Line= 5
  899113.4639628  809849.2700417  899135.3383055  809897.7074031
  899149.4012608  809936.7704851  899177.5261473  809972.7077831
  899188.4633186  810053.9576827
#Sta/Elev= 26
       0 1826.76   11.22 1818.48   23.23 1807.92   36.21 1796.17   53.15 1784.01
    55.2 1782.51    58.8 1781.77   65.21 1780.92   79.221777.882   82.391777.195
   85.32 1776.56   93.94 1776.53    94.8 1776.53  102.58  1776.6  103.71 1776.62
  108.29 1776.57  112.81 1776.54  120.52 1776.54  126.48 1776.51  131.261777.419
  134.53 1778.04   140.3 1781.12  148.08 1785.79  162.43  1795.1  169.97 1796.64
  222.28 1822.25
#Mann= 3 , 0 , 0
       0     .08       0   82.39     .05       0  131.26    .075       0
Bank Sta=82.39,131.26
Exp/Cntr=0.3,0.1

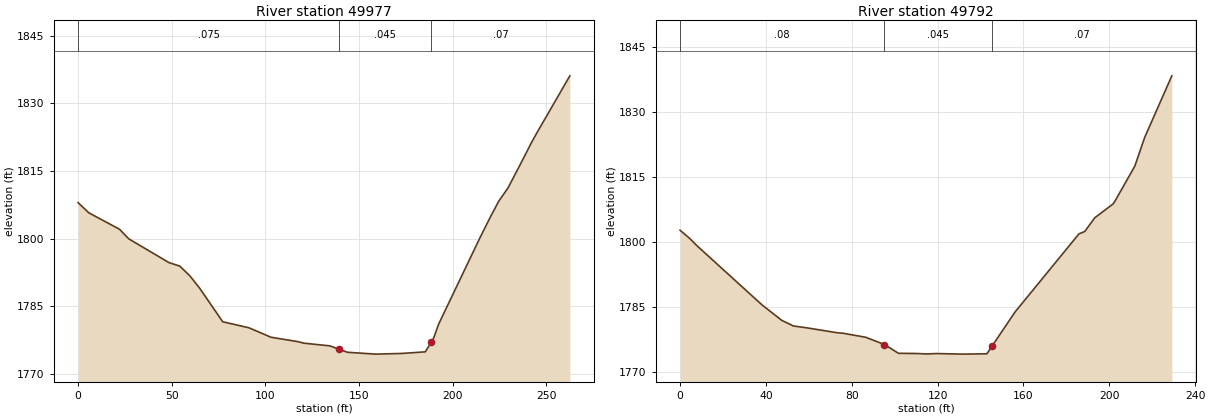
Type RM Length L Ch R = 1 ,49977   ,188.75,184.76,196.83
BEGIN DESCRIPTION:
49899.30
END DESCRIPTION:
XS GIS Cut Line= 6
  899004.0891767  809869.5825166  898957.2136831  809916.4580102
    898941.58886  809936.7704851  898927.5259047  809961.7706118
  898927.5259047  809980.5201947  898908.7763218  810102.3950441
#Sta/Elev= 30
       0 1807.97    5.72 1805.72   22.13 1802.07   27.04 1799.95   48.52 1794.68
   54.31  1793.9   59.68 1791.75   64.99 1788.96   77.24 1781.56   91.17 1780.23
  103.06 1778.12  117.38 1777.15   120.6 1776.81  134.36 1776.22  139.35 1775.48
  143.84 1774.79  158.99 1774.38  172.93 1774.53  185.46 1774.89  188.531776.983
  189.86 1777.89  192.61 1781.06  214.54  1800.1  220.34  1804.9  224.65 1808.27
  229.64 1811.25  235.79 1816.13  242.01 1821.17  244.94 1823.37  262.67  1836.1
#Mann= 3 , 0 , 0
       0    .075       0  139.35    .045       0  188.53     .07       0
Bank Sta=139.35,188.53
Exp/Cntr=0.3,0.1

Type RM Length L Ch R = 1 ,49792   ,429.3,414.46,395.08
BEGIN DESCRIPTION:
49714.54
END DESCRIPTION:
XS GIS Cut Line= 5
  898794.7138839  809833.6452186  898758.7765859  809925.8322896
  898740.0259788  809977.3954349  898722.8392879  810007.0821892
  898710.3392245  810046.1452712
#Sta/Elev= 27
       0  1802.7    4.56 1800.78    7.72 1799.19   38.18 1785.46   47.38 1781.89
   52.82 1780.59   58.97 1780.17   73.31 1779.02   75.88 1778.92   86.43 1777.99
   95.24 1776.31  101.76 1774.28  110.56 1774.23  114.83 1774.13   119.6 1774.22
   131.7 1774.09  142.96 1774.17   145.41775.969   156.1 1783.84  185.86 1801.87
  188.57 1802.42  193.24 1805.59  201.77 1808.78  202.55 1809.36  211.87  1817.5
  216.53 1824.21  229.13 1838.37
#Mann= 3 , 0 , 0
       0     .08       0   95.24    .045       0   145.4     .07       0
Bank Sta=95.24,145.4
Exp/Cntr=0.3,0.1