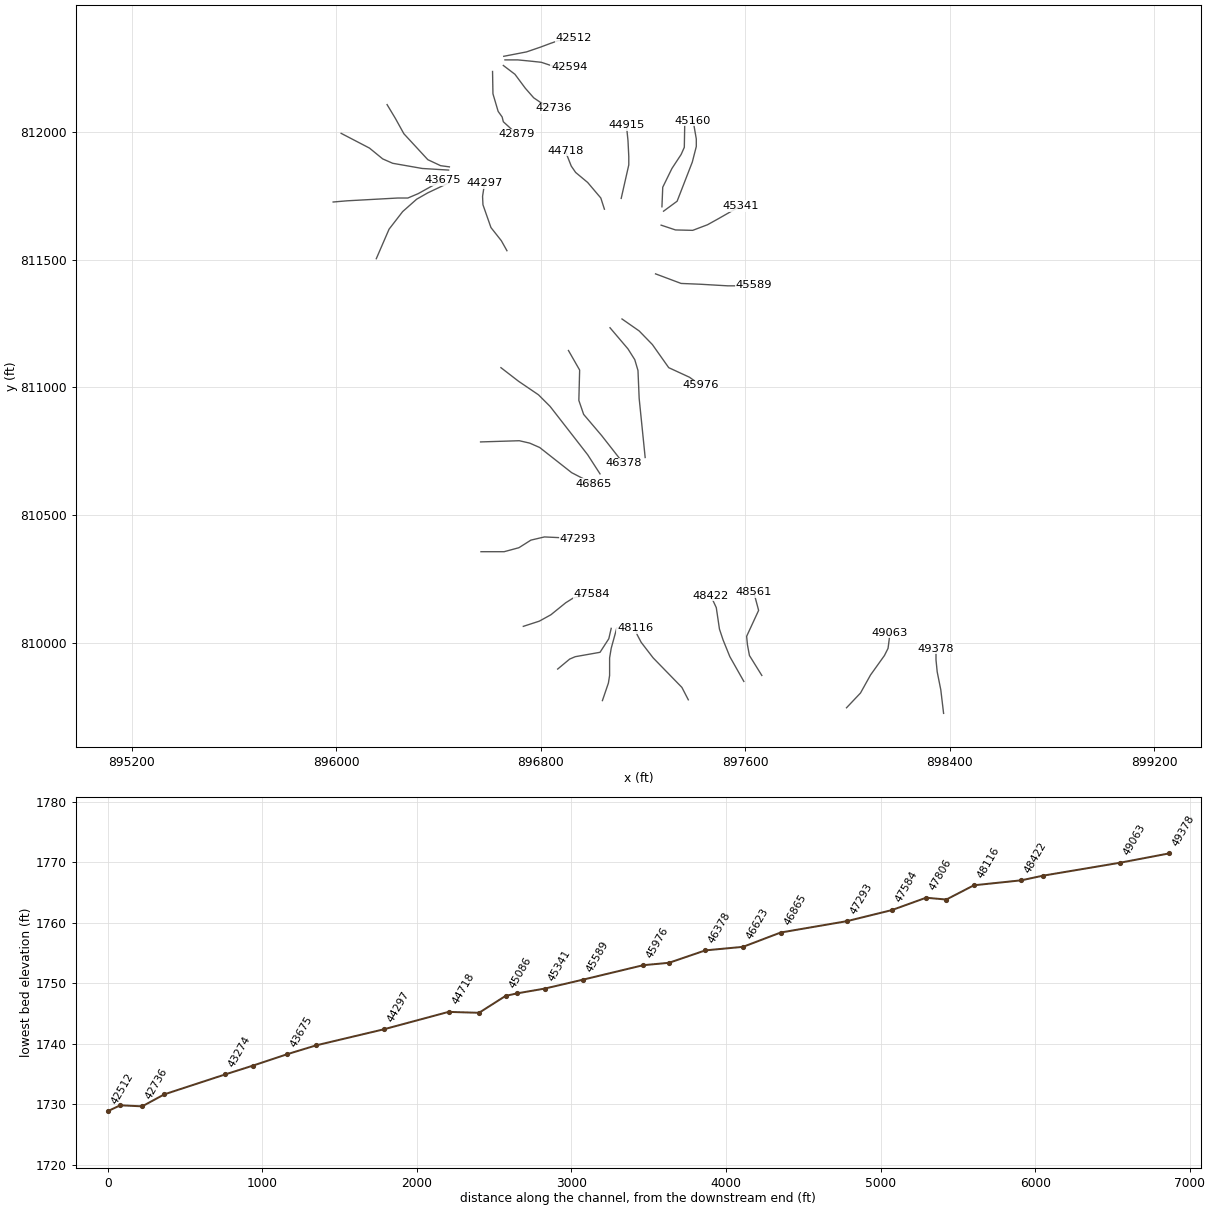
HEC-RAS study lds_big_laurel_crk.prj: lds_big_laurel_crk

--- lds_big_laurel_crk.g20 (geometry) --- (continued)

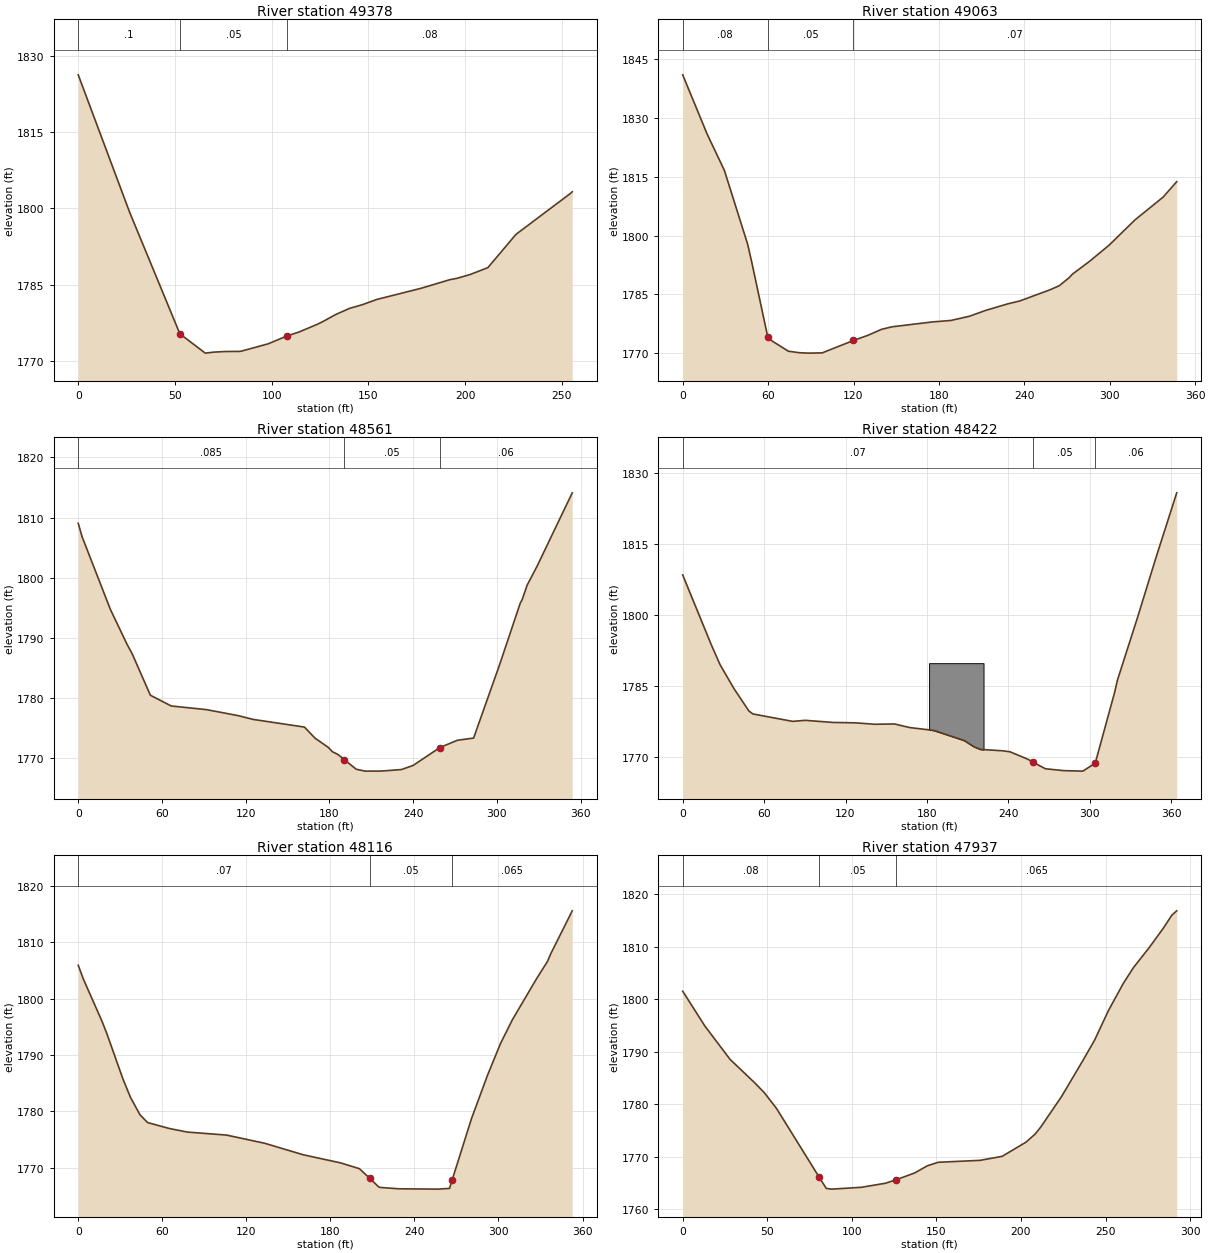
Type RM Length L Ch R = 1 ,49378   ,362.58,315.11,202.04
BEGIN DESCRIPTION:
49300.08
END DESCRIPTION:
XS GIS Cut Line= 5
  898375.9643225  809724.2704325   898365.026127  809816.4575035
  898350.9641959  809886.7702317  898346.2765441  809933.6447011
  898346.2765441  809977.3954349
#Sta/Elev= 25
       0 1826.25   26.48  1799.3   52.55  1775.3   65.68  1771.5    70.2  1771.7
   76.28 1771.82   83.55 1771.84   84.72 1771.93   98.26 1773.34  107.91 1774.88
  113.98 1775.63  123.29 1777.12  126.26 1777.66  133.07 1779.09  140.32 1780.31
  146.85 1781.02  154.17 1782.04  177.46 1784.28  192.11 1785.95  195.52 1786.19
  202.66 1786.97  211.79 1788.32  226.29 1794.86  254.58 1802.95   255.4 1803.25
#Mann= 3 , 0 , 0
       0      .1       0   52.55     .05       0  107.91     .08       0
Bank Sta=52.55,107.91
Exp/Cntr=0.3,0.1

Type RM Length L Ch R = 1 ,49063   ,440.92,502.1,542.83
BEGIN DESCRIPTION:
48984.97
END DESCRIPTION:
XS GIS Cut Line= 6
   897996.276819  809746.1447752  898050.9636999  809803.9574402
  898090.0267819  809874.2701684  898144.7136629  809950.8324162
  898158.7766182  809978.9573027  898166.5890298  810039.8947274
#Sta/Elev= 30
       0 1841.06   17.16 1825.93   29.27 1816.66   45.63 1797.79   48.46 1793.29
   59.71 1774.17   61.53 1773.36   74.23 1770.46   82.19 1770.07   88.36 1769.97
   98.05 1770.04  119.95  1773.2  130.17 1774.53  139.56 1776.03  146.97 1776.69
  175.48 1777.94  188.55 1778.32  201.54  1779.4  212.59 1780.85  228.51 1782.57
  236.89  1783.3     258 1786.14  264.52 1787.18  271.49 1789.23  273.72 1790.12
  285.65 1793.36  299.64 1797.57  317.73 1803.99  337.57 1809.84  347.09 1813.76
#Mann= 3 , 0 , 0
       0     .08       0   59.71     .05       0  119.95     .07       0
Bank Sta=59.71,119.95
Exp/Cntr=0.3,0.1

Type RM Length L Ch R = 1 ,48561   ,77.26,138.4,172.13
BEGIN DESCRIPTION:
48482.87
END DESCRIPTION:
XS GIS Cut Line= 6
  897665.0266768  809872.7072764  897616.5893154  809950.8324162
  897608.7758797   809993.020258  897605.6511199  810025.8327963
  897652.5266134  810127.3951708  897633.7760064   810197.707899
#Sta/Elev= 30
       0 1809.05    2.75 1806.82   23.02 1794.73   35.06 1788.87   38.61 1787.36
   51.69 1780.44   66.68 1778.65   91.98 1778.04  114.72 1777.04  125.22 1776.42
  162.09 1775.14  169.63 1773.31  179.18 1771.76  182.12 1771.04  186.16 1770.57
  190.631769.731  199.21 1768.12  205.66 1767.81  217.22 1767.82  231.58 1768.07
  240.01 1768.76   259.2 1771.74  271.75 1772.95  283.31 1773.31  301.95 1785.53
  316.72 1795.75  318.12 1796.35  321.67 1798.75   328.8 1801.91     354 1814.12
#Mann= 3 , 0 , 0
       0    .085       0  190.63     .05       0   259.2     .06       0
Bank Sta=190.63,259.2
Exp/Cntr=0.3,0.1

Type RM Length L Ch R = 1 ,48422   ,234.9,306.82,324.25
BEGIN DESCRIPTION:
48344.46
END DESCRIPTION:
XS GIS Cut Line= 6
  897594.7139485  809849.2700417  897540.0260434  809946.1447645
  897513.4640489  810011.7698409  897499.4010936  810053.9576827
  897486.9010303  810138.3323421  897465.0266876  810185.2078357
#Sta/Elev= 30
       0 1808.49   20.88 1793.87   27.53 1789.55   37.57 1784.58   48.81 1779.75
   51.72 1779.13   81.09 1777.56   90.37 1777.78  110.56 1777.34  127.33 1777.25
   141.6 1776.95  156.14 1777.01  167.38 1776.25  185.03 1775.65  207.43 1773.53
  214.73 1772.19  219.43 1771.64  236.02 1771.34  241.33 1771.13  254.57 1769.54
  258.56 1768.88  267.37 1767.55  280.97 1767.15  294.97 1767.05   304.1 1768.74
  318.41 1783.73  320.41 1786.24  334.95 1799.23  349.11 1812.38  364.14 1825.84
#Mann= 3 , 0 , 0
       0     .07       0  258.56     .05       0   304.1     .06       0
#Block Obstruct= 1 ,-1
   181.6  221.741789.856
Bank Sta=258.56,304.1
Exp/Cntr=0.3,0.1

Type RM Length L Ch R = 1 ,48116   ,291.19,178.71,117.49
BEGIN DESCRIPTION:
48037.65
END DESCRIPTION:
XS GIS Cut Line= 6
  897377.5262442  809777.3954457  897352.5261175   809825.832807
  897240.0265716  809941.4581369  897193.1510781  810002.3955616
   897177.526255  810032.0823158  897169.7138434  810057.0824425
#Sta/Elev= 30
       0 1805.91    3.67 1803.45   16.89 1796.03   20.44 1793.79    31.9 1785.76
   37.28  1782.5   44.11  1779.4   49.49 1778.03    65.1 1776.97   78.04 1776.34
  105.87 1775.81  133.09 1774.36   160.6 1772.32  187.31 1770.88  200.74 1769.85
  208.03 1768.16  214.66 1766.58  216.09 1766.52  228.65 1766.29  256.86 1766.23
  265.03 1766.36  266.881767.818  280.71 1778.72  292.26 1786.48  301.58 1792.12
  310.02  1796.3  327.13 1803.51  334.95 1806.58  337.29 1807.94  352.65 1815.56
#Mann= 3 , 0 , 0
       0     .07       0  208.03     .05       0  266.88    .065       0
Bank Sta=208.03,266.88
Exp/Cntr=0.3,0.1

Type RM Length L Ch R = 1 ,47937   ,200.62,130.92,22.68
BEGIN DESCRIPTION:
47858.94
END DESCRIPTION:
XS GIS Cut Line= 6
  897041.5884502  809774.2696617  897065.0267091  809843.0205221
  897069.7133367  809872.7072764  897069.7133367  809941.4581369
  897075.9638804  809978.9573027  897097.8392473  810058.6453345
#Sta/Elev= 30
       0 1801.54   13.09 1794.92   27.97 1788.58   42.39 1784.16   48.25 1782.23
   55.53  1779.2   80.451766.269    84.9    1764   88.12 1763.87  105.69 1764.22
  120.04    1765  126.36 1765.67  137.25 1766.96  144.73 1768.33  151.13 1768.98
  175.89 1769.35  188.88 1770.11  202.97 1772.81  208.32 1774.33  211.72 1775.69
  224.03 1781.51  236.51 1788.29   243.5 1792.21  251.69 1797.84   260.5 1803.02
   266.5 1806.03  275.78 1809.82  284.07 1813.49  289.22 1816.02  292.09 1816.84
#Mann= 3 , 0 , 0
       0     .08       0   80.45     .05       0  126.36    .065       0
Bank Sta=80.45,126.36
Exp/Cntr=0.3,0.1

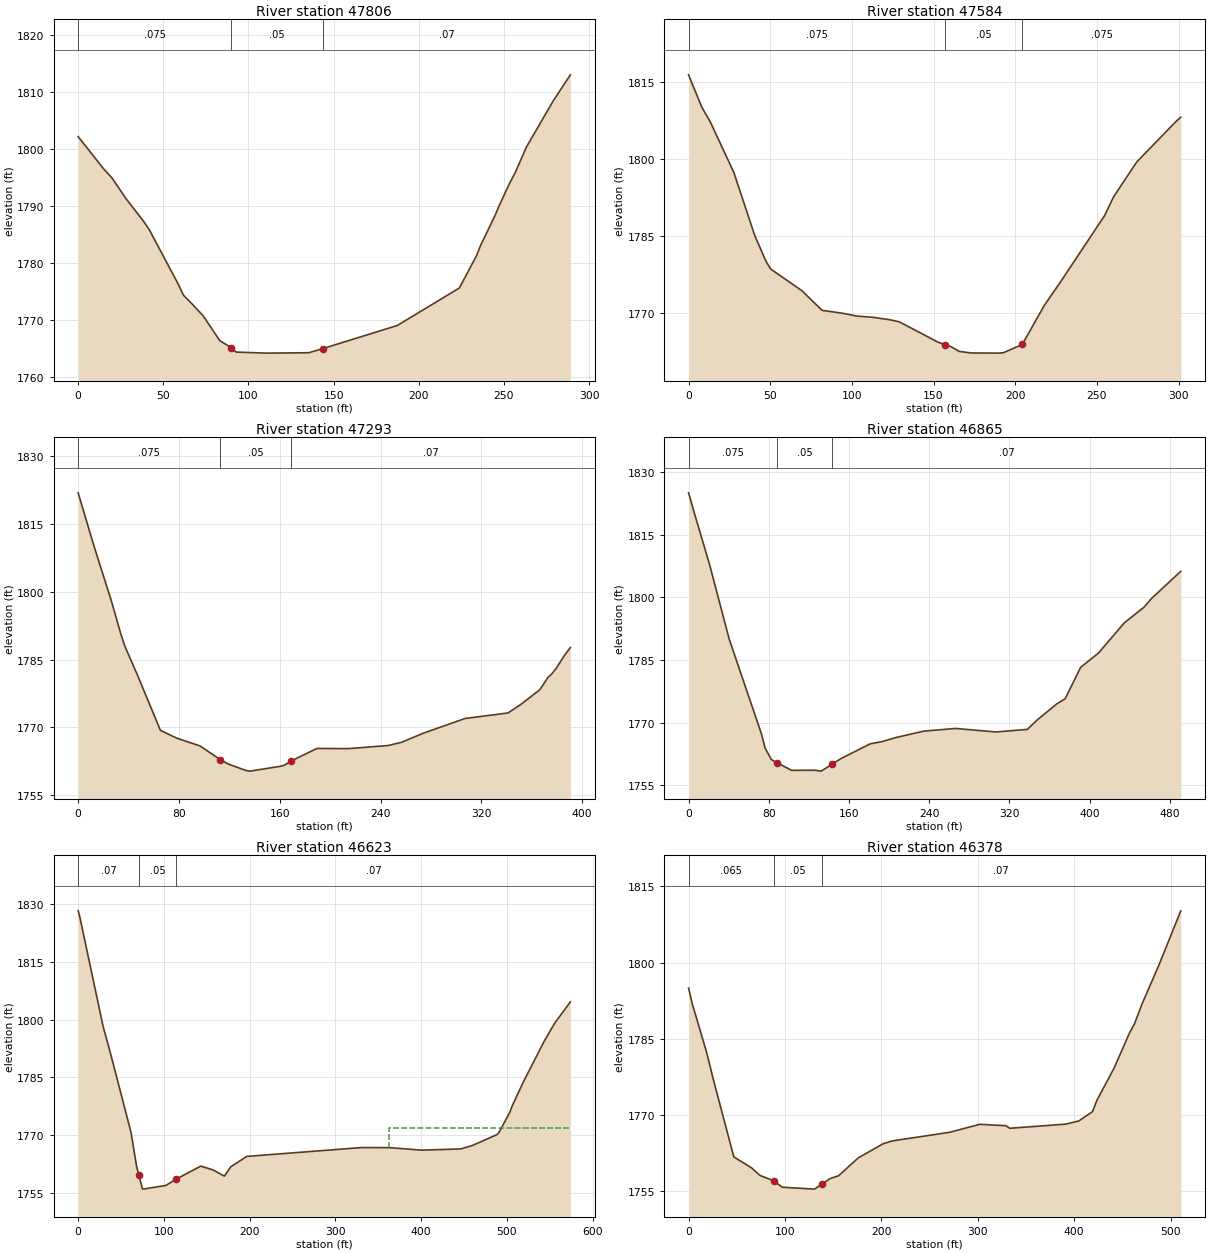
Type RM Length L Ch R = 1 ,47806   ,191.8,221.75,217.73
BEGIN DESCRIPTION:
47728.02
END DESCRIPTION:
XS GIS Cut Line= 6
  896866.5885877  809897.7074031  896913.4640812  809936.7704851
  896935.3384239  809946.1447645  897032.2141709  809963.3324796
  897066.5885769  810016.4574927  897075.9638804  810057.0824425
#Sta/Elev= 27
       0 1802.12   14.69 1796.57   19.88 1794.87      28 1791.29   38.59  1787.2
   41.76 1785.81   58.95 1776.15    61.8 1774.33   66.32 1772.97   73.38 1770.71
   83.15 1766.37   89.66 1765.15    92.8 1764.35  110.97 1764.17  135.47 1764.24
  143.69 1764.97  187.35 1769.01  223.82 1775.59  233.82 1781.21  236.23 1783.02
  244.63 1788.22   247.3 1790.09  253.25 1793.92  256.48 1795.74  263.23 1800.32
  278.98 1808.42  288.99 1812.95
#Mann= 3 , 0 , 0
       0    .075       0   89.66     .05       0  143.69     .07       0
Bank Sta=89.66,143.69
Exp/Cntr=0.3,0.1

Type RM Length L Ch R = 1 ,47584   ,324.93,291.02,243.91
BEGIN DESCRIPTION:
47506.27
END DESCRIPTION:
XS GIS Cut Line= 6
  896732.2136749  810064.8948541  896794.7139916   810085.207329
  896840.0265932  810110.2074557  896897.8392581  810157.0829492
  896927.5260124  810175.8325321  896999.4016326  810193.0202473
#Sta/Elev= 30
       0 1816.34    8.09 1810.06   13.38 1807.12   27.75  1797.3   40.51 1785.05
   46.67 1780.54    47.8  1779.8   50.26 1778.51   69.37 1774.29   81.76 1770.45
   94.26 1769.89  103.12 1769.34  113.14 1769.09  122.68 1768.65  128.95 1768.23
  152.83 1764.24  157.26 1763.75  160.72 1763.37  165.74 1762.45  173.17 1762.15
  189.39 1762.12  192.77  1762.2  204.32 1763.81  217.73 1771.38  227.46 1775.87
  254.64 1788.88  260.26 1792.59  274.37 1799.35  298.42 1807.26  301.37 1808.08
#Mann= 3 , 0 , 0
       0    .075       0  157.26     .05       0  204.32    .075       0
Bank Sta=157.26,204.32
Exp/Cntr=0.3,0.1

Type RM Length L Ch R = 1 ,47293   ,432.51,428.27,284.13
BEGIN DESCRIPTION:
47215.25
END DESCRIPTION:
XS GIS Cut Line= 6
  896566.5891159  810357.0829385  896657.2143191  810357.0829385
  896715.0259598  810372.7077616  896761.9014534    810402.39554
  896815.0264665  810414.8956034  896944.7137275  810408.6450596
#Sta/Elev= 30
       0 1821.92   12.67 1810.03   26.33 1798.02   33.79 1790.74   37.06 1787.97
   47.37 1781.37   65.28 1769.32   78.12 1767.61   96.77 1765.86  112.94 1762.81
  119.07 1761.87  133.14 1760.44  136.36 1760.29  161.01 1761.38  163.51 1761.57
   168.9 1762.51  189.46 1765.31  214.51 1765.27  245.98 1765.96  256.85 1766.69
  273.38 1768.63  307.06 1771.95  341.14 1773.17  351.14 1775.02  366.34 1778.29
  372.85 1781.02  375.94 1781.83  379.37 1783.02  386.12 1785.98  390.69 1787.66
#Mann= 3 , 0 , 0
       0    .075       0  112.94     .05       0   168.9     .07       0
Bank Sta=112.94,168.9
Exp/Cntr=0.3,0.1

Type RM Length L Ch R = 1 ,46865   ,280.07,242.29,130.45
BEGIN DESCRIPTION:
46786.98
END DESCRIPTION:
XS GIS Cut Line= 6
  896565.0262239  810786.7696712  896716.5888518   810791.457323
  896757.2138016  810782.0830436  896796.2758594  810764.8953285
  896921.2764928  810666.4577138  897005.6511522  810622.7080042
#Sta/Elev= 30
       0 1825.06    5.64 1820.33    20.8 1808.01   40.47 1790.09   72.85 1767.21
   76.36  1763.9   82.64 1761.17   88.61 1760.36  102.86  1758.6  125.71 1758.63
  132.23 1758.41  143.011760.047  152.14 1761.43  181.08 1764.94  192.96 1765.48
  206.74 1766.45  234.37 1767.98  266.17 1768.63  306.49 1767.79   337.8  1768.4
   347.7 1770.67  367.21 1774.52  375.52 1775.74  390.86  1783.2  391.46 1783.36
  408.88 1786.72  434.56 1793.93  454.09 1797.66  461.78 1799.78  490.86 1806.27
#Mann= 3 , 0 , 0
       0    .075       0   88.61     .05       0  143.01     .07       0
Bank Sta=88.61,143.01
Exp/Cntr=0.3,0.1

Type RM Length L Ch R = 1 ,46623   ,263.16,244.53,95.3
BEGIN DESCRIPTION:
46544.69
END DESCRIPTION:
XS GIS Cut Line= 6
  896644.7142557  811077.3948636   896713.464092  811024.2698504
  896791.5892318  810971.1448373  896836.9008092  810925.8322357
  896983.7768095   810736.770442  897032.2141709   810661.770062
#Sta/Elev= 30
       0 1828.21    2.16 1826.41    29.1 1798.25   38.17 1790.87   60.95 1771.38
   61.98 1770.33   68.22 1761.88   70.761759.744   74.87 1756.15   75.53 1756.05
  102.31    1757  114.42 1758.66  143.06 1762.02  157.29 1761.03  170.56 1759.42
  178.01 1761.84  196.64 1764.53  330.81 1766.83  362.39 1766.81  400.71 1766.16
  446.13 1766.47  459.86 1767.37  488.75 1770.21  491.49 1771.01  503.51    1776
  505.97 1777.47  518.95 1783.71  543.56 1794.39  555.57    1799  574.13 1804.61
#Mann= 3 , 0 , 0
       0     .07       0   70.76     .05       0  114.42     .07       0
#XS Ineff= 2 , 0
       0                  362.39       0    1772
Permanent Ineff=
       F       F
Bank Sta=70.76,114.42
Exp/Cntr=0.3,0.1

Type RM Length L Ch R = 1 ,46378   ,204.95,234.51,178.12
BEGIN DESCRIPTION:
46300.16
END DESCRIPTION:
XS GIS Cut Line= 6
  896908.7764295   811144.582832  896952.5261391  811068.0205842
  896949.4013793  810949.2704946  896968.1509622  810894.5825895
  897038.4636904  810811.7697979  897122.8383498  810703.9579038
#Sta/Elev= 30
       0 1794.99     4.3 1791.62   18.64 1782.42    25.7 1777.03   46.93 1761.81
   65.25 1759.65    74.1 1758.15   88.19 1757.12   97.11 1755.84  130.67 1755.46
  137.99 1756.41  146.63 1757.52  155.73 1758.11  176.09 1761.62  201.89 1764.39
  211.08 1764.94  270.86 1766.64  302.12 1768.21  329.18 1767.93  333.16 1767.43
  391.06 1768.24  404.89 1768.88  418.93 1770.71  423.66 1772.98  441.47 1779.31
  457.38 1786.21  462.41 1787.94  470.34 1791.89  487.98 1799.61  510.52  1810.2
#Mann= 3 , 0 , 0
       0    .065       0   88.19     .05       0  137.99     .07       0
Bank Sta=88.19,137.99
Exp/Cntr=0.3,0.1

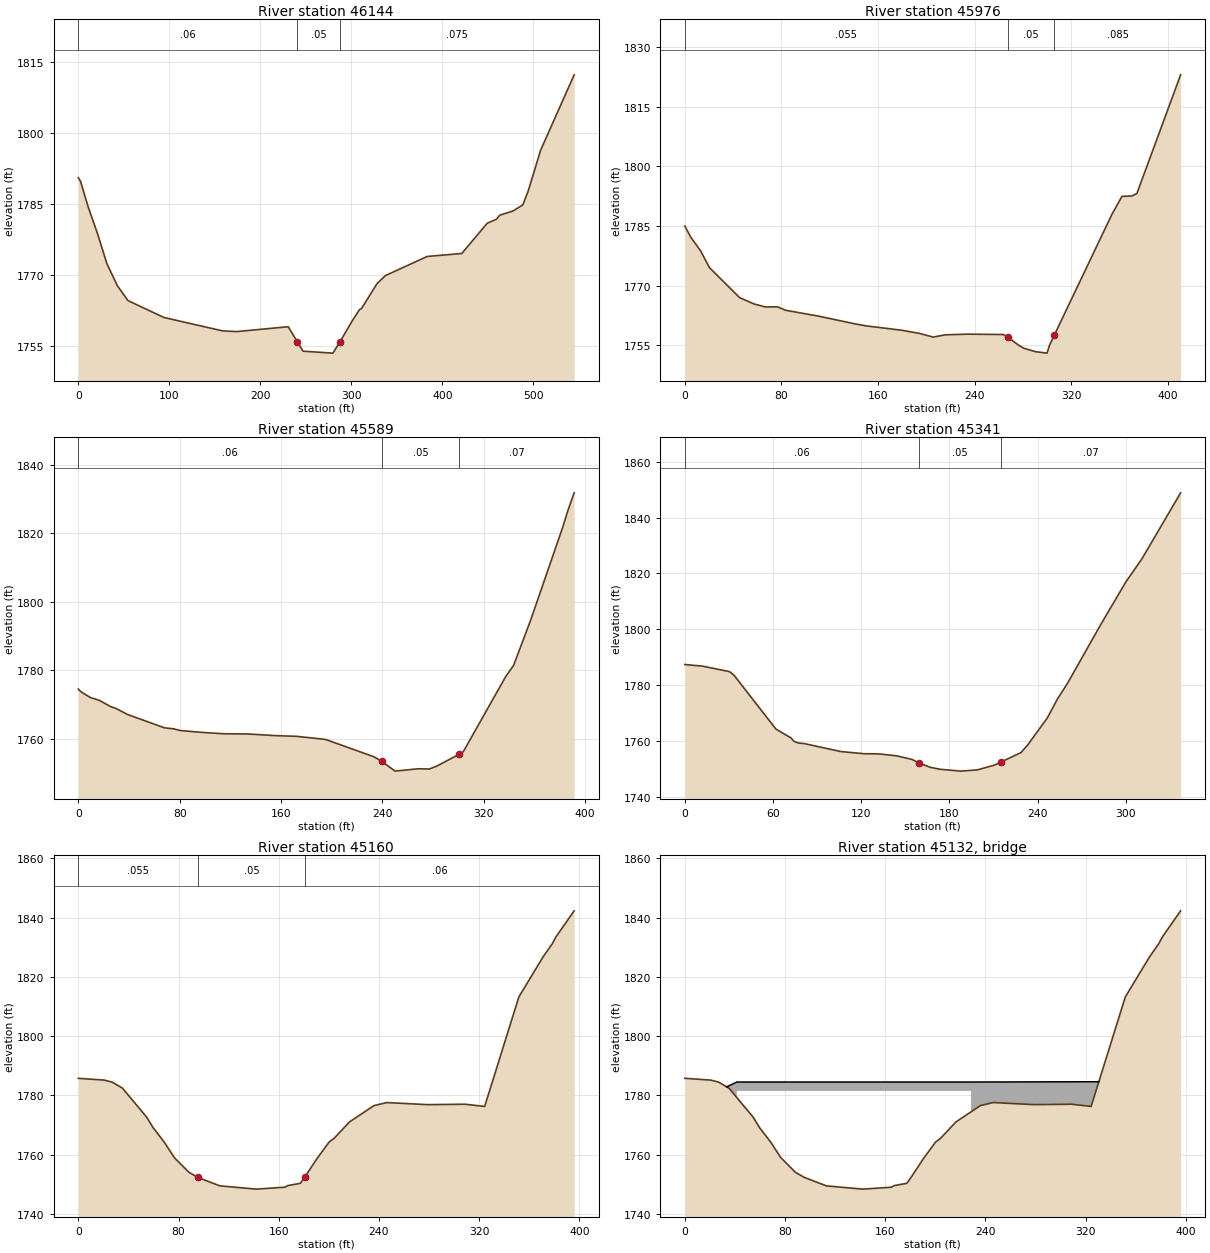
Type RM Length L Ch R = 1 ,46144   ,80.73,167.35,280.51
BEGIN DESCRIPTION:
46065.65
END DESCRIPTION:
XS GIS Cut Line= 6
  897071.2762287  811233.6451432  897141.5889569  811150.8323516
  897168.1509514   811108.645534  897180.6510147  811066.4576922
  897185.3386665  810957.0829062  897208.7759012  810725.8322465
#Sta/Elev= 30
       0 1790.48    2.52 1789.68   10.36 1784.58   21.26 1778.56   31.47 1772.28
   43.07 1767.61   54.59 1764.51   94.08 1760.94   158.5 1758.11  173.92 1757.96
  230.64 1758.99  240.75 1755.78  246.91 1753.82  279.75 1753.41  287.65 1755.84
  300.68 1760.13  309.02 1762.62  311.07  1762.8  328.22  1768.1  337.57 1769.81
  383.46 1773.84  421.38 1774.47  449.37 1780.87  459.19 1781.68  463.24 1782.57
  477.56 1783.44   488.4 1784.72  494.35 1787.66  508.02 1796.29  544.86 1812.22
#Mann= 3 , 0 , 0
       0     .06       0  240.75     .05       0  287.65    .075       0
Bank Sta=240.75,287.65
Exp/Cntr=0.3,0.1

Type RM Length L Ch R = 1 ,45976   ,242.96,387.49,429.36
BEGIN DESCRIPTION:
45898.30
END DESCRIPTION:
XS GIS Cut Line= 6
  897118.1517222  811268.0205734  897185.3386665  811221.1450799
  897236.9018119  811168.0200667  897300.9639964  811077.3948636
   897382.213896  811039.8946736  897425.9636056  811008.6450273
#Sta/Elev= 30
       0 1784.95    5.24 1782.02   13.15  1778.7   20.36 1774.52   45.43 1766.96
   57.35 1765.37   66.71 1764.62   76.75 1764.66   83.55 1763.78  110.61 1762.32
   141.6 1760.33  150.26 1759.86  179.72 1758.76  193.69 1758.01  205.71 1757.05
   215.8 1757.61   233.8 1757.78  263.86 1757.69  267.45 1757.04  276.32 1755.05
  280.96 1754.22  290.41 1753.38  300.01 1753.01  302.22 1755.07  306.14 1757.57
  353.92 1787.97  362.11 1792.42  370.31 1792.51  374.47 1793.14   410.7 1822.97
#Mann= 3 , 0 , 0
       0    .055       0  267.45     .05       0  306.14    .085       0
Bank Sta=267.45,306.14
Exp/Cntr=0.3,0.1

Type RM Length L Ch R = 1 ,45589   ,200.88,247.92,275.68
BEGIN DESCRIPTION:
45510.81
END DESCRIPTION:
XS GIS Cut Line= 6
   897249.400851  811444.5823038  897349.4013577   811407.083138
  897424.4017378   811403.957354  897532.2136318  811397.7078344
  897568.1509299  811397.7078344  897633.7760064  811402.3954862
#Sta/Elev= 30
       0 1774.55    2.36  1773.7    9.54 1772.09   16.76 1771.25   25.49 1769.44
   29.48 1768.96    38.9 1767.14   68.03 1763.26   75.47 1762.95   80.65 1762.46
   96.48 1761.96  114.29 1761.53  133.52 1761.47  156.26 1760.97  172.24 1760.78
  195.29 1759.87  233.45 1754.82  239.81 1753.45  250.18 1750.63  268.38 1751.32
  277.26 1751.25  283.01 1752.08  300.48 1755.48  304.01 1756.28  337.64 1778.28
  343.78 1781.47  357.31 1794.74  382.61 1821.81  386.52 1826.49  391.59 1831.79
#Mann= 3 , 0 , 0
       0     .06       0  239.81     .05       0  300.48     .07       0
Bank Sta=239.81,300.48
Exp/Cntr=0.3,0.1

Type RM Length L Ch R = 1 ,45341   ,123.62,180.96,242.03
BEGIN DESCRIPTION:
45262.89
END DESCRIPTION:
XS GIS Cut Line= 6
  897271.2762179  811635.2080137  897327.5259908  811616.4574066
  897394.7139593  811614.8955388  897452.5266242  811636.7698815
  897494.7134418  811660.2081403  897582.2138852  811710.2073695
#Sta/Elev= 30
       0 1787.36   12.04 1786.79   30.53  1784.8   33.54 1783.49   62.01 1764.23
   72.19 1761.07   74.37  1759.8   77.27 1759.23   81.24 1759.03  106.25 1756.16
  122.01 1755.39  131.67 1755.34  144.19 1754.63   154.6 1753.35  159.27 1752.08
  167.16 1750.49  173.62 1749.82   187.8 1749.15  198.98 1749.59   210.6  1751.3
  215.431752.473  228.76 1755.81  233.34 1758.57   246.6 1768.16  253.54 1775.01
  260.24  1780.5     283 1801.68  300.04 1816.93  310.96  1825.2  337.35 1848.91
#Mann= 3 , 0 , 0
       0     .06       0  159.27     .05       0  215.43     .07       0
Bank Sta=159.27,215.43
Exp/Cntr=0.5,0.3

Type RM Length L Ch R = 1 ,45160   ,76.42,73.71,54.79
BEGIN DESCRIPTION:
45081.94
END DESCRIPTION:
XS GIS Cut Line= 6
  897280.6515215  811689.8948946  897333.7765346  811728.9579766
  897393.1510673  811882.0824723  897408.7758904   811943.019897
  897408.7758904  811972.7076754  897396.2758271  812044.5822715
#Sta/Elev= 30
       0 1785.74    20.7 1785.14   27.07 1784.45   35.22 1782.43   54.55 1772.65
   59.67 1769.11   68.47 1764.28   76.67 1758.96   88.42 1753.99   95.55 1752.28
  113.03 1749.45   142.1 1748.35  164.93    1749  167.11 1749.53  177.25 1750.32
  180.85 1752.46  190.61 1758.71  200.15 1764.21  204.23 1765.52  216.43 1771.02
  236.03 1776.54  246.23 1777.56  278.86 1776.86  308.58    1777  324.37 1776.25
  351.68 1813.22  371.09 1826.78   378.4 1831.19  381.34 1833.51  395.81 1842.26
#Mann= 3 , 0 , 0
       0    .055       0   95.55     .05       0  180.85     .06       0
Bank Sta=95.55,180.85
Exp/Cntr=0.5,0.3

Type RM Length L Ch R = 3 ,45132   ,,,
BEGIN DESCRIPTION:
45051.9  FBSTR_1286  No Photo
END DESCRIPTION:
Bridge Culvert--1,0,-1,-1, 0
Deck Dist Width WeirC Skew NumUp NumDn MinLoCord MaxHiCord MaxSubmerge Is_Ogee
12,37,2.6,0, 5, 5, , , 0.95, 0, 0,0,,
   33.36    41.5     135   228.5  330.52
 1782.84 1784.49 1784.49 1784.49 1784.59
         1781.49 1781.49 1781.49
   17.41   35.25     129   222.5  288.24
 1782.61 1784.49 1784.49 1784.49 1784.58
         1781.49 1781.49 1781.49
BR Coef=-1 , 0 , 0 ,, 0 ,,,0.8,0,,0,
WSPro=,,,, 1 ,,,, 0 ,,,, 0 ,,,,-1 ,-1 ,-1 , 0 , 0 , 0 , 0 , 0
BC Design=,, 0 ,, 0 ,,,,,,

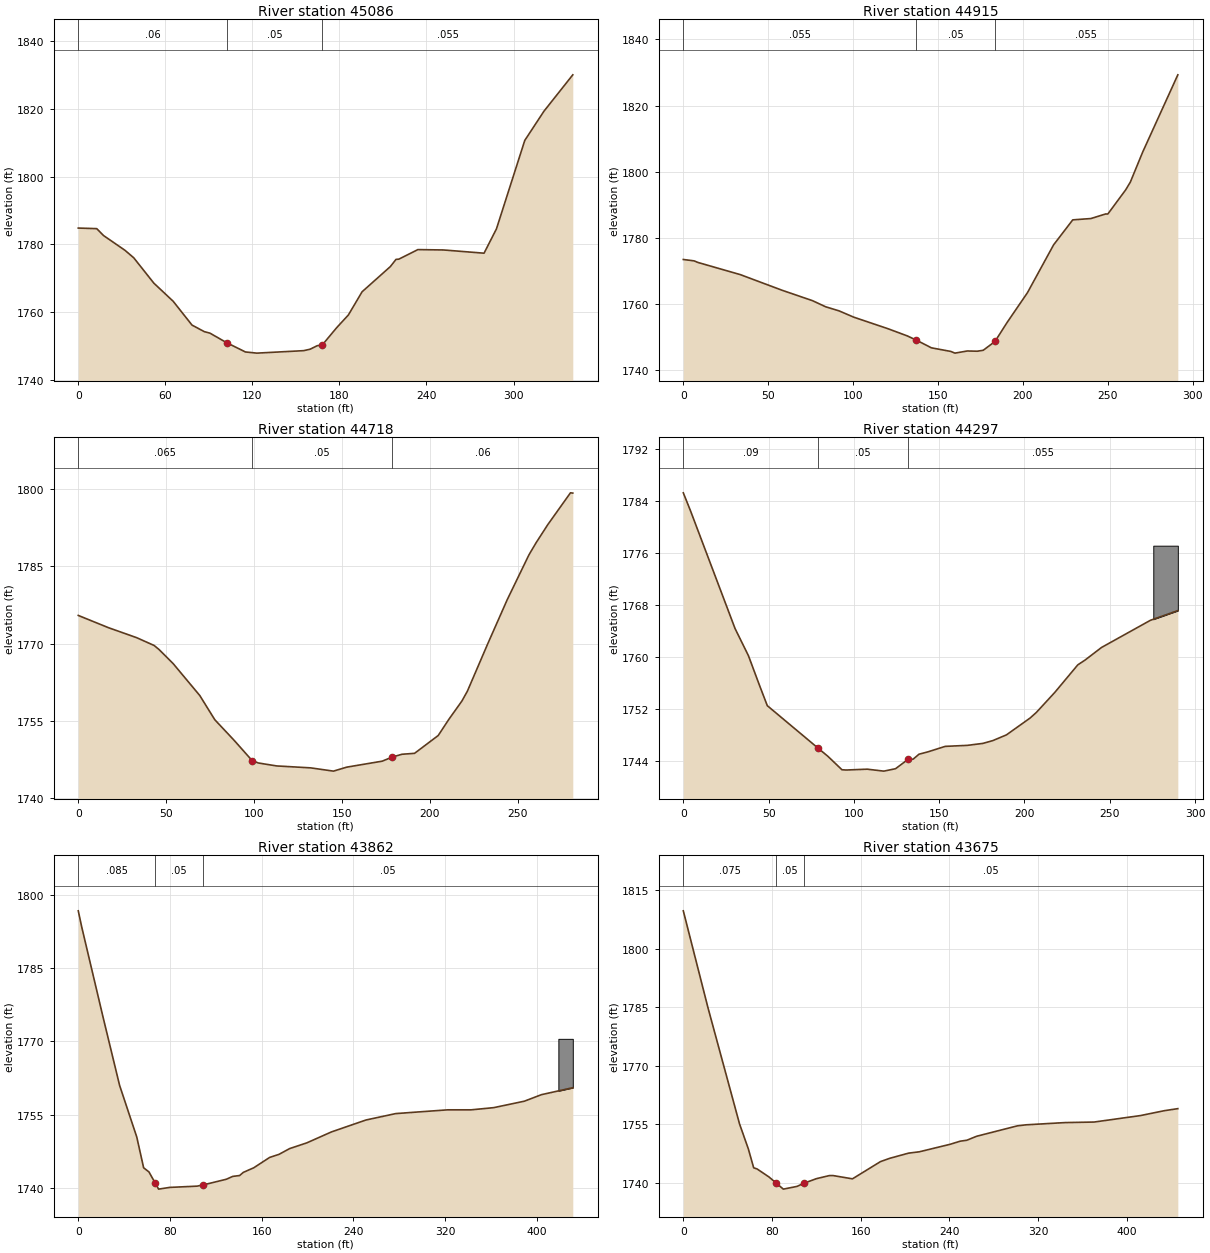
Type RM Length L Ch R = 1 ,45086   ,153.43,171.52,217
BEGIN DESCRIPTION:
45008.22
END DESCRIPTION:
XS GIS Cut Line= 6
  897274.4009777  811707.0826097  897277.5267617  811783.6448576
  897313.4640597  811857.0823456  897349.4013577  811911.7702507
  897361.9014211  811939.8951372   897363.464313  812025.8326886
#Sta/Elev= 30
       0 1784.81   12.73 1784.64   17.41 1782.61   32.23 1778.24   38.22 1776.05
   52.13 1768.55   65.42 1763.22    78.4  1756.2   86.94 1754.25   90.73 1753.83
  102.27 1751.01  115.23 1748.27  123.08 1747.93  155.43 1748.66  159.89  1749.1
  164.63 1750.11  168.22 1750.36  178.04  1755.4  186.17 1759.18  195.64 1766.03
  215.11 1773.45  218.99 1775.57  220.95 1775.64  234.08 1778.46   251.8 1778.35
  279.69  1777.4  288.24 1784.58  307.76 1810.66  320.94 1819.25  340.85    1830
#Mann= 3 , 0 , 0
       0     .06       0  102.27     .05       0  168.22    .055       0
Bank Sta=102.27,168.22
Exp/Cntr=0.5,0.3

Type RM Length L Ch R = 1 ,44915   ,129.27,197.09,240.73
BEGIN DESCRIPTION:
44836.70
END DESCRIPTION:
XS GIS Cut Line= 5
  897115.0259383   811739.895148  897144.7137167  811871.1453009
  897144.7137167  811903.9578392  897141.5889569  811966.4571317
  897135.3384132  812027.3955806
#Sta/Elev= 30
       0 1773.45    6.38 1773.03    8.57 1772.56   33.55 1768.88   58.17 1764.15
   76.14 1760.99   83.84 1759.15    91.7 1757.92  100.33 1756.02  120.64  1752.5
  131.88 1750.35  137.21 1749.08  146.11 1746.74  157.47 1745.66  159.95 1745.14
  167.22 1745.79  173.13 1745.72  176.62    1746  183.54 1748.66  190.64 1754.38
  202.67 1763.42  218.05 1777.87  229.33 1785.43  240.04 1785.83  248.75 1787.22
     250  1787.2  260.48 1794.49  263.23 1796.83  270.47 1805.87  291.21 1829.28
#Mann= 3 , 0 , 0
       0    .055       0  137.21     .05       0  183.54    .055       0
Bank Sta=137.21,183.54
Exp/Cntr=0.3,0.1

Type RM Length L Ch R = 1 ,44718   ,428.13,420.27,372.24
BEGIN DESCRIPTION:
44639.62
END DESCRIPTION:
XS GIS Cut Line= 6
  897049.4008618  811697.7073062  897035.3389306    811741.45804
  896983.7768095  811802.3954647  896936.9013159  811841.4575225
  896919.7136008  811866.4576492  896896.2763661  811925.8321819
#Sta/Elev= 30
       0 1775.49    17.2 1773.11   33.21 1771.18   43.19 1769.66   45.96 1768.88
   53.97 1766.16   69.15 1759.96   77.71 1755.26   88.86 1751.21   98.94 1747.34
  102.49 1746.87  112.89  1746.3  132.31 1745.92  145.23 1745.29  152.78 1746.06
  172.96 1747.22   178.6    1748  184.23 1748.56   191.4 1748.74  204.87  1752.2
  210.97 1755.36  218.34 1758.88  221.46 1760.79  233.02 1769.96  244.18 1778.57
  256.51 1787.24  260.51 1789.55  267.21 1793.09  280.13 1799.27  281.46 1799.22
#Mann= 3 , 0 , 0
       0    .065       0   98.94     .05       0   178.6     .06       0
Bank Sta=98.94,178.6
Exp/Cntr=0.3,0.1

Type RM Length L Ch R = 1 ,44297   ,506.25,435.48,273.32
BEGIN DESCRIPTION:
44219.35
END DESCRIPTION:
XS GIS Cut Line= 6
  896668.1514904   811535.207507  896646.2761235   811574.270589
  896605.6511737  811625.8327101  896574.4015275  811714.8950213
  896572.8386355  811747.7075595  896580.6510471  811799.2696807
#Sta/Elev= 30
       0 1785.26    4.21  1782.5   30.35 1764.35   38.18 1760.18   44.77 1755.54
   49.24 1752.48   79.18  1745.9   84.81 1744.67   93.01 1742.61   95.42 1742.57
  107.78  1742.7  117.55  1742.4  124.39 1742.77  131.81 1744.22  134.72 1744.24
  138.19 1745.01  143.29 1745.36  153.49 1746.21  166.61 1746.37  175.59 1746.67
  181.33 1747.09  189.41 1747.98   203.3 1750.58  206.96 1751.44  217.82 1754.54
  231.22 1758.76  235.52 1759.51  245.19 1761.45  273.83 1765.63  289.88 1767.12
#Mann= 3 , 0 , 0
       0     .09       0   79.18     .05       0  131.81    .055       0
#Block Obstruct= 1 ,-1
  275.49  289.881777.124
Bank Sta=79.18,131.81
Exp/Cntr=0.3,0.1

Type RM Length L Ch R = 1 ,43862   ,242.49,186.83,20.05
BEGIN DESCRIPTION:
43783.87
END DESCRIPTION:
XS GIS Cut Line= 6
  896157.2138339  811503.9578607  896207.2140872  811619.5821664
  896260.3391004  811688.3330268  896315.0259813  811736.7703882
  896358.7767151  811761.7705149  896444.7142665  811802.3954647
#Sta/Elev= 30
       0 1796.72    3.08 1793.35   21.76 1774.83   36.05    1761   51.05 1750.42
   57.03 1744.13   61.68 1743.28   67.04 1741.04   70.09 1739.76   79.68 1740.11
   103.6 1740.37  108.59  1740.6  129.16 1741.78  134.82 1742.37  140.75 1742.54
  143.94 1743.18  153.18 1744.14  166.98 1746.25  175.16 1746.88  184.35 1748.05
  199.42 1749.23   220.9 1751.47  251.03 1753.91  276.93 1755.22  322.45 1755.99
  342.86 1755.99  362.53 1756.44  389.23 1757.76  404.04 1759.09  431.44 1760.52
#Mann= 3 , 0 , 0
       0    .085       0   67.04     .05       0  108.59     .05       0
#Block Obstruct= 1 ,-1
  418.85  431.441770.525
Bank Sta=67.04,108.59
Exp/Cntr=0.3,0.1

Type RM Length L Ch R = 1 ,43675   ,245.43,220.85,113.92
BEGIN DESCRIPTION:
43597.04
END DESCRIPTION:
XS GIS Cut Line= 6
  895988.4634909  811725.8321926   896043.151396  811730.5198444
  896241.5884933    811741.45804  896280.6515753    811741.45804
  896321.2765251  811758.6447309  896416.5883559   811811.769744
#Sta/Elev= 30
       0 1809.74   22.32 1784.79   50.69 1755.06   58.66 1748.62   63.46 1743.77
   66.48 1743.49   77.27 1741.42    83.3 1739.97   90.22  1738.3  102.54    1739
  108.53 1739.78  120.09 1740.99  131.61 1741.77  134.88 1741.79  152.53 1740.94
  177.79 1745.36  186.24 1746.22   203.2 1747.54  212.79 1747.88  240.76 1749.82
   249.6  1750.6  255.67 1750.85  264.52 1751.87  301.16 1754.54  309.23 1754.81
  344.22 1755.38  370.45 1755.52  412.23 1757.18  433.86 1758.44  445.93 1758.96
#Mann= 3 , 0 , 0
       0    .075       0    83.3     .05       0  108.53     .05       0
Bank Sta=83.3,108.53
Exp/Cntr=0.3,0.1

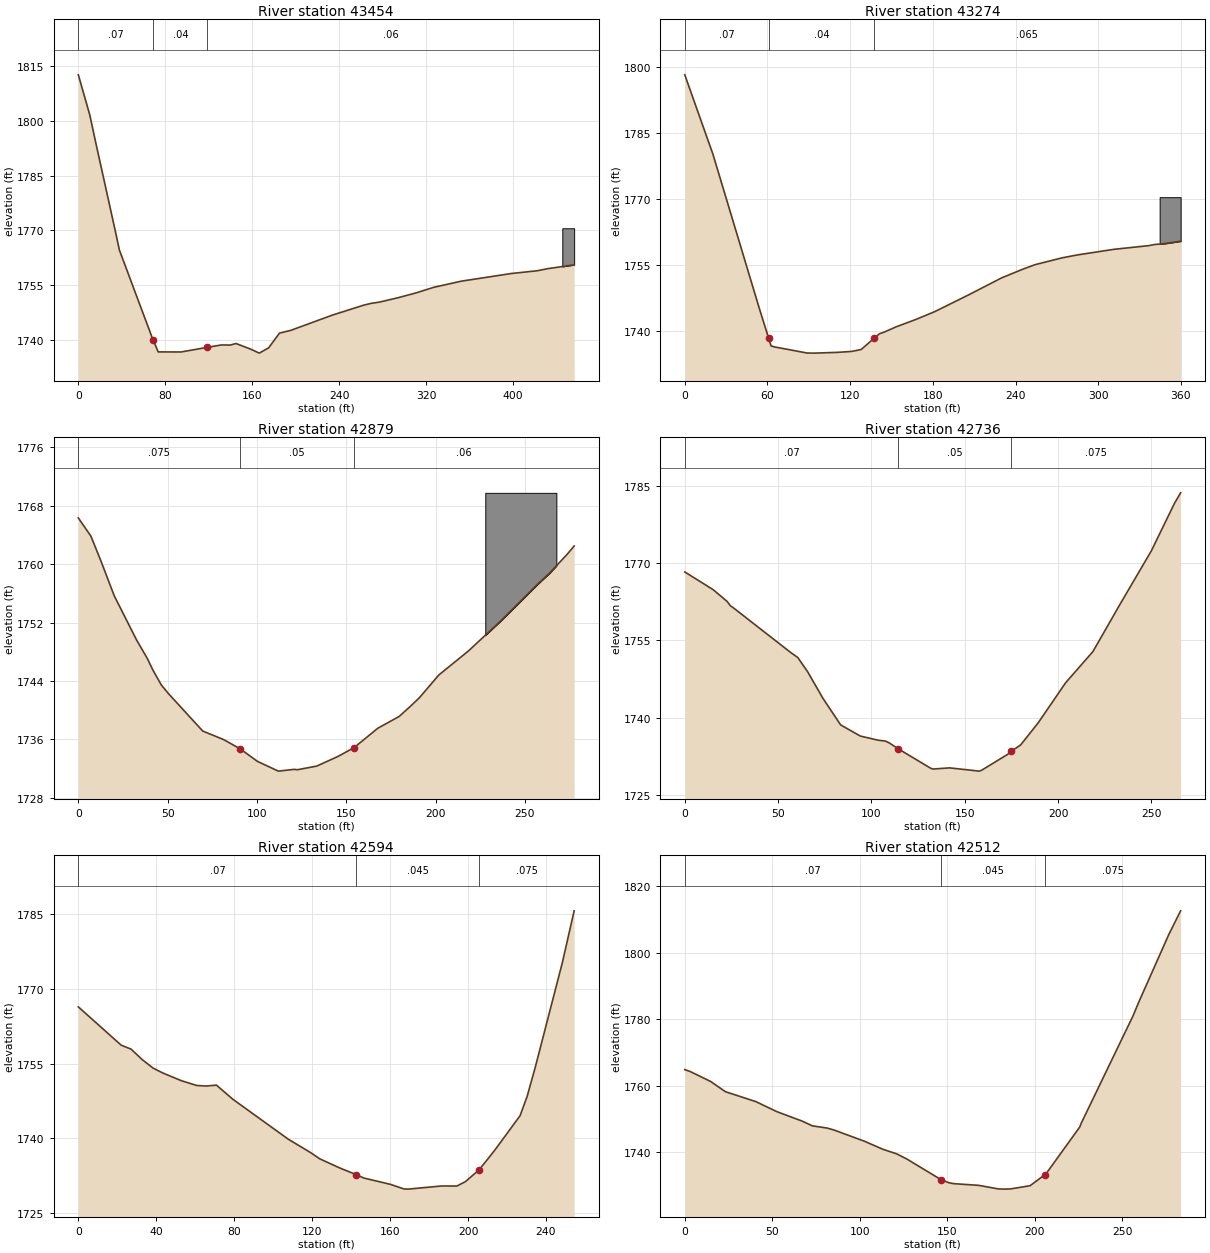
Type RM Length L Ch R = 1 ,43454   ,195.2,179.61,75.95
BEGIN DESCRIPTION:
43376.19
END DESCRIPTION:
XS GIS Cut Line= 6
  896019.7141614  811994.5830423  896130.6508152  811936.7703774
  896182.2139606  811894.5825356  896221.2760184  811877.3948205
  896336.9013482  811857.0823456  896440.0266147   811850.832826
#Sta/Elev= 30
       0 1812.55   10.59 1801.52    16.1  1793.9   34.05 1769.78   37.77 1764.63
   67.57 1740.94   68.97 1739.94   73.43 1736.76   94.47 1736.73  118.741738.004
  131.46 1738.65  139.93 1738.63  145.06 1739.05   158.9 1737.47  166.45 1736.42
  175.04 1737.85  185.09  1741.9  195.21 1742.62  233.93 1746.84  262.77 1749.56
   269.5 1750.04  276.98 1750.37  294.09 1751.57  310.34 1752.86  326.96 1754.42
  352.47 1756.11  398.16 1758.19  422.29 1758.96  431.37  1759.5  456.17 1760.58
#Mann= 3 , 0 , 0
       0     .07       0   68.97     .04       0  118.74     .06       0
#Block Obstruct= 1 ,-1
  445.26  456.171770.575
Bank Sta=68.97,118.74
Exp/Cntr=0.3,0.1

Type RM Length L Ch R = 1 ,43274   ,416.42,395.66,377.55
BEGIN DESCRIPTION:
43196.57
END DESCRIPTION:
XS GIS Cut Line= 6
  896199.4016757  812107.0825882  896232.2142139  812052.3946831
  896265.0267522  811993.0201503  896358.7767151  811891.4577758
  896408.7759443  811868.0205411  896443.1513745  811863.3328894
#Sta/Elev= 28
       0 1798.18    20.4 1780.16   53.96 1745.23   60.74 1738.45    62.6 1736.59
   65.76 1736.33   88.78 1734.98   94.28 1734.96  111.18 1735.14  121.13 1735.35
  127.95 1735.78  137.36 1738.34  141.26 1739.36   144.6 1739.72     153 1740.89
  167.49 1742.59  181.18 1744.36  205.98  1748.2  229.91 1752.06  245.26 1754.03
  254.06 1755.05  274.12 1756.63   284.9 1757.27  311.33 1758.54  336.48 1759.37
  340.79 1759.63  347.49 1759.81  359.74 1760.38
#Mann= 3 , 0 , 0
       0     .07       0   60.74     .04       0  137.36    .065       0
#Block Obstruct= 1 ,-1
  344.52  359.741770.382
Bank Sta=60.74,137.36
Exp/Cntr=0.3,0.1

Type RM Length L Ch R = 1 ,42879   ,89.43,142.88,163.1
BEGIN DESCRIPTION:
42800.91
END DESCRIPTION:
XS GIS Cut Line= 6
  896611.9017175  812236.7698492  896613.4635853    812149.27043
  896633.7760602  812080.5205937  896649.4008833  812058.6452268
  896654.0885351  812039.8956439  896707.2135482  811991.4572584
#Sta/Elev= 30
       0 1766.32    7.06 1763.82   12.99 1760.21   20.08 1755.67   32.58 1749.62
   38.59 1747.09   41.68 1745.52   46.42 1743.46   50.28 1742.31   69.63 1737.14
   81.33 1735.97   90.67 1734.69  100.29 1732.98  111.97 1731.65  120.83 1731.89
  122.62 1731.84  133.46 1732.34  145.36 1733.66  154.41 1734.88  167.63 1737.52
  179.61 1739.14  186.29 1740.62  190.95 1741.71  201.81 1744.82  218.39 1748.11
  236.31 1752.19  257.06 1757.24  263.73 1758.75  273.48  1761.3  277.54 1762.48
#Mann= 3 , 0 , 0
       0    .075       0   90.67     .05       0  154.41     .06       0
#Block Obstruct= 1 ,-1
  227.79  267.581769.758
Bank Sta=90.67,154.41
Exp/Cntr=0.3,0.1

Type RM Length L Ch R = 1 ,42736   ,65.25,141.79,169.79
BEGIN DESCRIPTION:
42658.03
END DESCRIPTION:
XS GIS Cut Line= 6
  896654.0885351   812260.208108  896699.4011367  812225.8326778
  896740.0260865  812171.1447727  896772.8386247  812133.6456069
  896821.2759861  812100.8330686  896852.5266565  812093.0196329
#Sta/Elev= 30
       0 1768.29   15.24 1764.84   22.63 1762.59   24.56 1761.68   25.76 1761.41
   56.88 1752.63   60.53  1751.7   65.84 1748.92   74.02 1743.78   83.48 1738.64
   94.04 1736.47  103.66 1735.66  107.49  1735.5  109.55 1735.14  114.16 1734.04
   131.6 1730.26   132.9 1730.07  141.88  1730.3  157.68 1729.67  158.88 1729.81
  172.92 1732.91  174.85  1733.5  179.96 1734.76  189.39 1739.06     204 1746.79
  218.67 1752.86  233.43 1762.18  249.97 1772.39  262.34 1781.59  265.64 1783.63
#Mann= 3 , 0 , 0
       0     .07       0  114.16     .05       0  174.85    .075       0
Bank Sta=114.16,174.85
Exp/Cntr=0.3,0.1

Type RM Length L Ch R = 1 ,42594   ,27.95,81.68,107.54
BEGIN DESCRIPTION:
42516.24
END DESCRIPTION:
XS GIS Cut Line= 6
  896660.3390789  812282.0824507   896710.338308  812282.0824507
  896758.7766936   812277.394799  896802.5264032  812272.7071472
   896844.714245  812258.6452161  896911.9011892  812255.5204563
#Sta/Elev= 30
       0 1766.36   21.98 1758.69   27.08 1757.89   32.86 1755.77   38.36  1754.1
   43.43  1753.1   52.81 1751.58   60.74 1750.61   65.62  1750.5   70.89 1750.68
    79.3 1747.85  107.78 1739.84  119.14 1737.18  123.86 1735.92  134.22 1734.07
  142.66 1732.74  146.57 1732.06  160.34 1730.78  166.99 1729.89  169.18 1729.84
  186.42 1730.47  194.28 1730.46  198.66 1731.34  205.74 1733.73  213.47 1737.51
  226.71 1744.55  230.34 1748.42  234.51 1754.25  248.45 1775.29  254.47 1785.61
#Mann= 3 , 0 , 0
       0     .07       0  142.66    .045       0  205.74    .075       0
Bank Sta=142.66,205.74
Exp/Cntr=0.3,0.1

Type RM Length L Ch R = 1 ,42512   ,52.74,140.83,211.8
XS GIS Cut Line= 6
  896655.6514271  812296.1454061  896744.7137383  812313.3331212
  896799.4016434  812332.0827041  896836.9008092  812346.1446352
  896868.1514797  812357.0828308  896929.0889044  812366.4581343
#Sta/Elev= 30
       0 1764.85    2.97  1764.3   14.79 1761.28   23.21  1758.2   40.58 1755.22
   52.67 1752.18   67.08 1749.34   72.93 1747.91   81.33 1747.25      85 1746.71
  102.58  1743.3  113.24 1740.85  121.02  1739.5  126.78 1737.96  146.32 1731.74
  150.77 1730.81  153.54 1730.51  167.87    1730  179.28 1728.92  182.92 1728.86
  186.09 1728.92  197.32 1729.89  205.69 1733.18  206.35 1733.42  225.67 1747.55
   226.7 1748.88  256.14 1781.04  259.31 1785.05  276.64 1805.61  283.33 1812.67
#Mann= 3 , 0 , 0
       0     .07       0  146.32    .045       0  205.69    .075       0
Bank Sta=146.32,205.69
Exp/Cntr=0.3,0.1