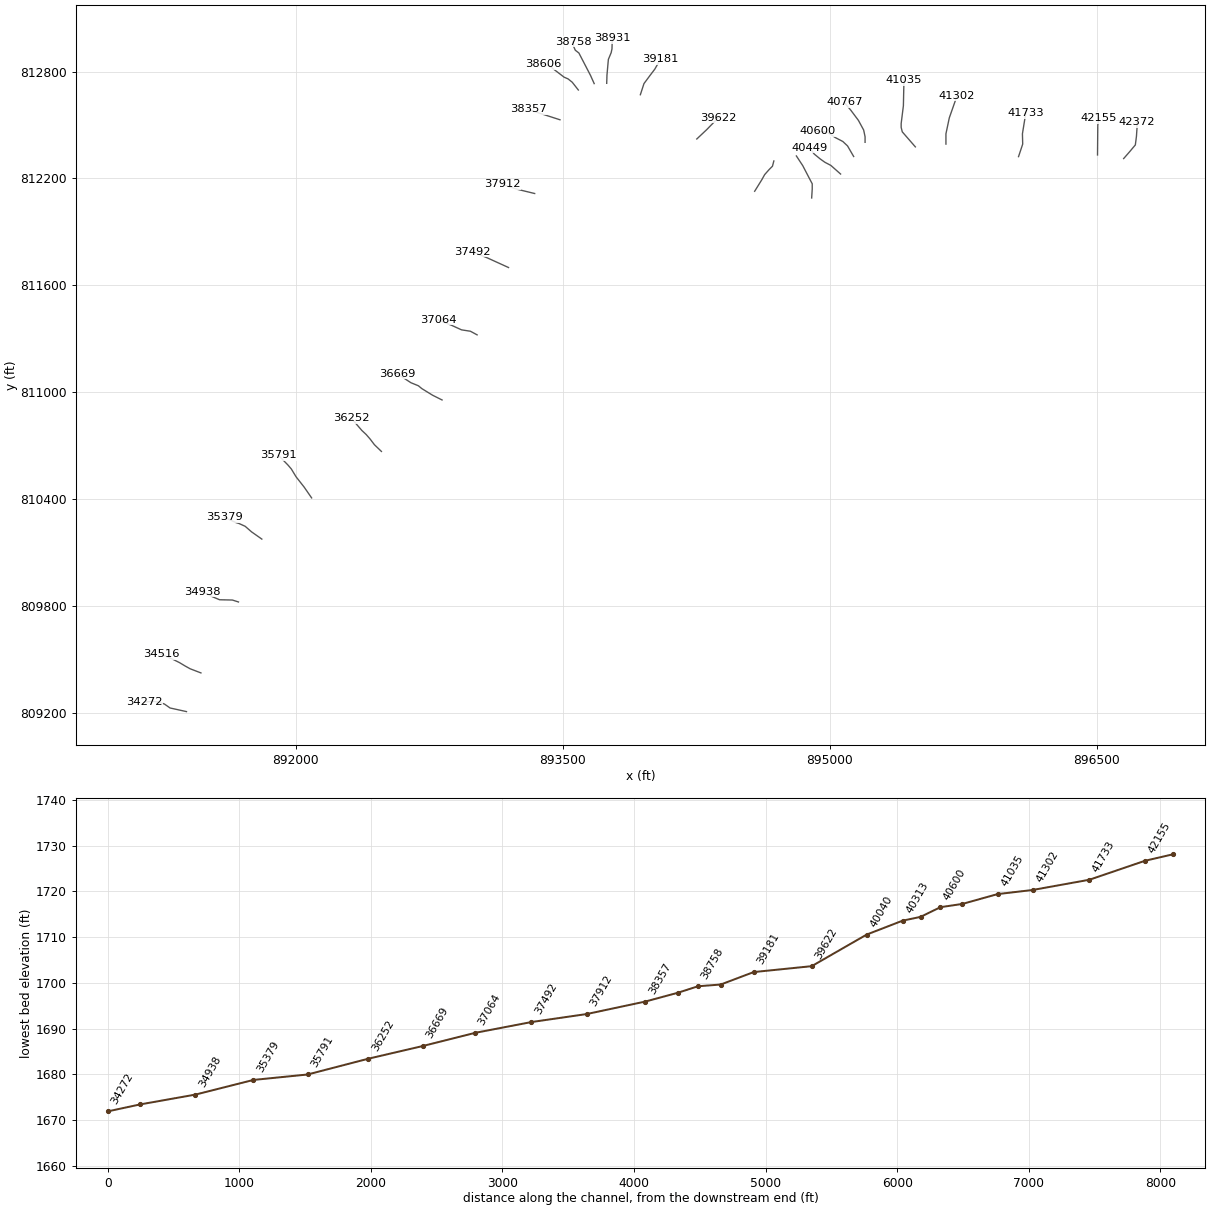
HEC-RAS study lds_big_laurel_crk.prj: lds_big_laurel_crk

--- lds_big_laurel_crk.g20 (geometry) --- (continued)

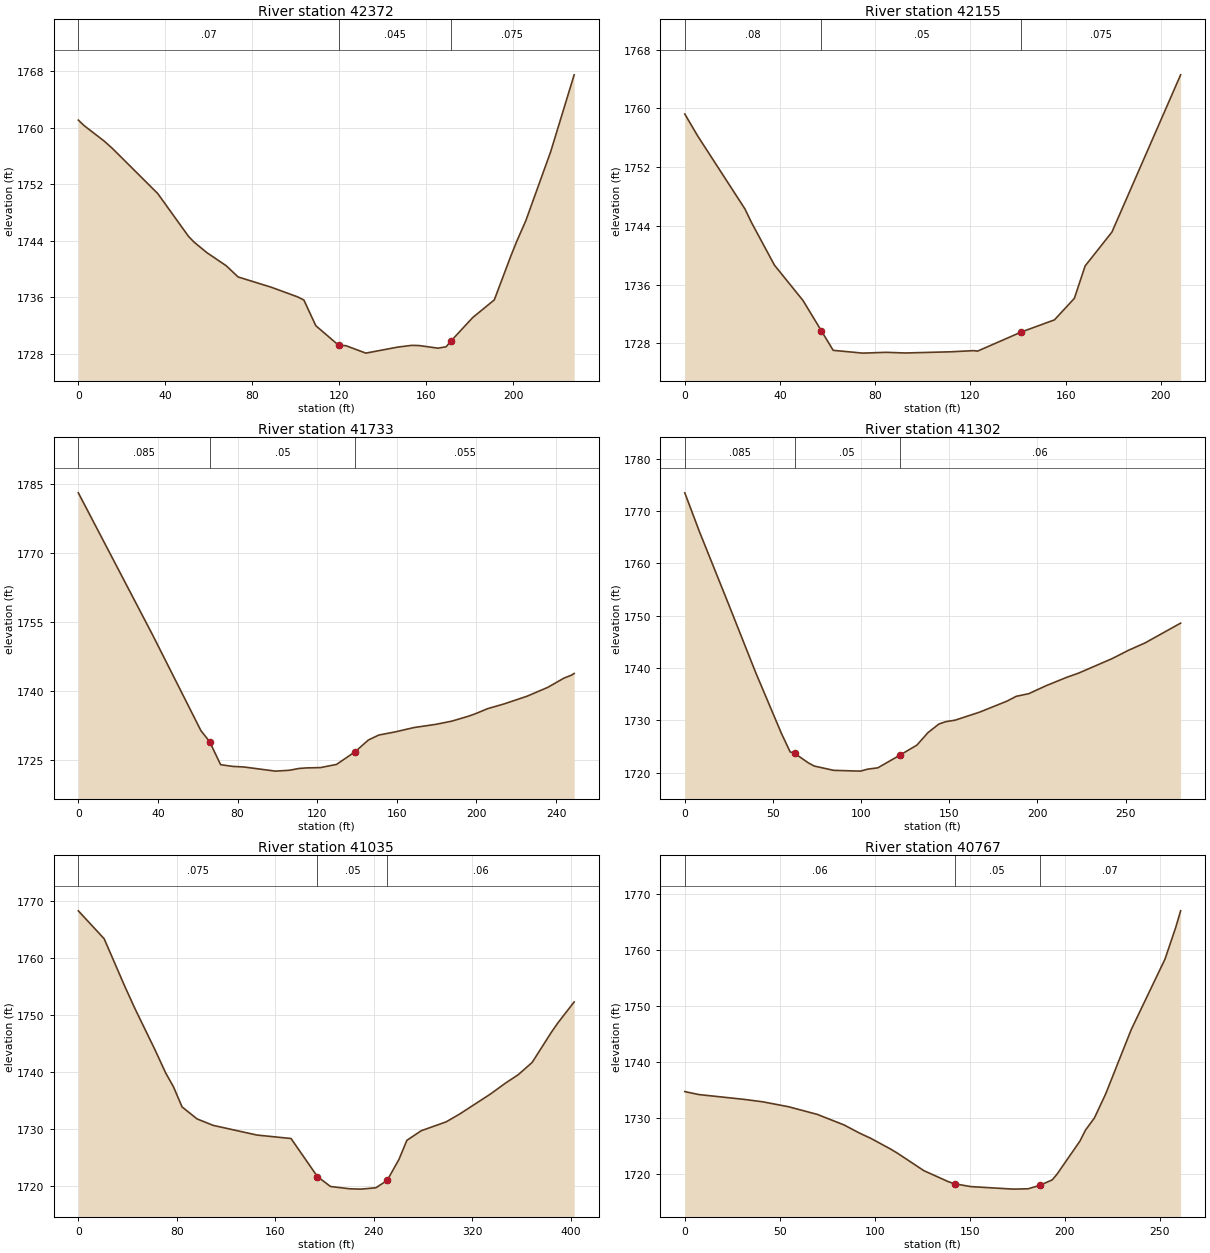
Type RM Length L Ch R = 1 ,42372   ,176.6,216.38,220.85
XS GIS Cut Line= 6
  896652.5266673  812311.7702292  896685.3392055  812349.2704192
  896718.1517438   812388.332477  896724.4012634  812436.7698384
  896727.5260231   812483.645332  896727.5260231  812514.8949782
#Sta/Elev= 30
       0 1761.07    2.77 1760.26    11.9  1758.1   15.81 1757.02   36.51 1750.68
   50.65 1744.63   53.19 1743.82   58.99 1742.35   68.01 1740.47   73.44 1738.89
   88.56 1737.45  100.84 1736.07  103.67 1735.63  109.16    1732  119.62 1729.24
  122.99 1729.17  132.16 1728.12   146.8 1728.97  153.24 1729.22  156.65 1729.19
  165.34 1728.82  169.07 1729.02  171.14 1729.78  181.21 1733.13  191.21 1735.65
  198.73 1741.79  201.47 1743.89  205.67 1746.83  217.13 1756.61  227.91 1767.47
#Mann= 3 , 0 , 0
       0     .07       0  119.62    .045       0  171.14    .075       0
Bank Sta=119.62,171.14
Exp/Cntr=0.3,0.1

Type RM Length L Ch R = 1 ,42155   ,432.79,422.4,415.76
BEGIN DESCRIPTION:
42077.35
END DESCRIPTION:
XS GIS Cut Line= 3
  896505.6516912  812332.0827041   896507.213559  812499.2701551
  896513.4641028  812539.8951049
#Sta/Elev= 20
       0 1759.24    5.45 1756.24   25.26 1746.32   28.05 1744.45   37.65 1738.67
   49.68 1733.84   57.36 1729.73   62.34 1727.06   74.81 1726.68   84.49 1726.79
   92.55  1726.7  111.74 1726.86  121.38 1727.02  122.97 1726.95   141.4 1729.56
   155.3 1731.21  163.66 1734.14  168.18 1738.55  179.45 1743.17   208.3 1764.58
#Mann= 3 , 0 , 0
       0     .08       0   57.36     .05       0   141.4    .075       0
Bank Sta=57.36,141.4
Exp/Cntr=0.3,0.1

Type RM Length L Ch R = 1 ,41733   ,428.93,430.87,409.68
BEGIN DESCRIPTION:
41654.94
END DESCRIPTION:
XS GIS Cut Line= 4
   896061.900979  812322.7074006  896085.3392378  812393.0201288
  896083.7763459  812450.8327937  896102.5259288  812566.4581236
#Sta/Elev= 29
       0 1783.03   37.28 1752.17   61.58 1731.35   65.95 1728.96   71.48 1723.94
   77.51 1723.57   83.19 1723.44   99.03 1722.54  106.12 1722.73  110.87 1723.12
  114.79 1723.24  121.66 1723.31  129.72    1724  139.17 1726.79  145.67 1729.29
  150.94 1730.38  159.35 1731.08  168.61 1732.01  179.59 1732.71  187.57  1733.4
  195.82 1734.45  199.17 1734.96  205.65 1736.12  213.99 1737.16  225.47 1738.83
  235.76 1740.73   243.9 1742.74  247.72  1743.4  249.09 1743.76
#Mann= 3 , 0 , 0
       0    .085       0   65.95     .05       0  139.17    .055       0
Bank Sta=65.95,139.17
Exp/Cntr=0.3,0.1

Type RM Length L Ch R = 1 ,41302   ,231.36,267.05,289.9
BEGIN DESCRIPTION:
41224.07
END DESCRIPTION:
XS GIS Cut Line= 4
  895654.0885889  812393.0201288  895654.0885889  812450.8327937
   895672.839196  812539.8951049  895716.5889056  812664.8947141
#Sta/Elev= 30
       0 1773.46    8.28 1766.07   24.56 1752.42   40.13  1739.2   54.86 1727.47
   59.77 1723.97   62.29 1723.71   70.06 1721.88   73.44 1721.27   84.43 1720.45
   99.64  1720.3   103.8 1720.68  109.49 1720.93  122.06 1723.36   131.7 1725.28
  137.87 1727.63  144.15  1729.3  147.97 1729.74  153.28 1730.03  167.18 1731.56
  182.77 1733.67  188.01 1734.59  195.09 1735.09   204.7 1736.58  216.58 1738.21
  223.37 1739.02  242.39 1741.79  251.68 1743.38  261.08 1744.79  281.26 1748.57
#Mann= 3 , 0 , 0
       0    .085       0   62.29     .05       0  122.06     .06       0
Bank Sta=62.29,122.06
Exp/Cntr=0.3,0.1

Type RM Length L Ch R = 1 ,41035   ,245.22,268.09,324.51
BEGIN DESCRIPTION:
40957.01
END DESCRIPTION:
XS GIS Cut Line= 6
  895482.2134862  812377.3953057  895408.7759981  812461.7699651
  895402.5264785  812486.7700918  895402.5264785  812508.6454586
  895415.0265419  812608.6449412  895418.1513017  812750.8322655
#Sta/Elev= 30
       0 1768.34   20.98 1763.43   37.46 1755.19   46.07  1751.1   62.34 1743.86
   70.86 1739.86   77.34 1737.35   84.22 1733.86   96.38 1731.75  109.51 1730.61
  144.99 1728.91  172.71  1728.3  194.12 1721.61  204.78 1719.86  220.29 1719.46
   229.6  1719.4  241.58 1719.64  250.79 1720.94  260.38 1724.65  266.74 1727.98
  278.41 1729.67  298.55 1731.22  309.65 1732.61  334.46  1736.1  346.94 1738.06
  357.15 1739.52  368.47 1741.68  383.88 1746.92     389 1748.53  402.57 1752.32
#Mann= 3 , 0 , 0
       0    .075       0  194.12     .05       0  250.79     .06       0
Bank Sta=194.12,250.79
Exp/Cntr=0.3,0.1

Type RM Length L Ch R = 1 ,40767   ,128.85,166.55,187.32
BEGIN DESCRIPTION:
40688.92
END DESCRIPTION:
XS GIS Cut Line= 6
  895199.6956679  812403.0314454  895199.6956679  812434.2810917
  895191.8832564  812471.7812817  895162.1954779  812526.4691868
  895120.0086603  812582.7189597  895082.5084703  812628.0315613
#Sta/Elev= 28
       0 1734.66    7.42 1734.13   31.25 1733.27   41.12 1732.83   54.56 1731.96
   69.74 1730.59   83.79 1728.71   92.01 1727.24   97.85 1726.32   108.3  1724.4
  111.79 1723.69  125.84 1720.54  138.68 1718.58  141.92 1718.21   150.5  1717.7
   172.9 1717.25  180.65 1717.31  186.66 1717.91  193.35  1718.9  195.76 1719.87
  207.87 1725.79  210.84 1727.78  215.52 1729.94  221.48 1734.25  234.89 1745.71
  252.69 1758.31  258.36    1764  260.91 1766.93
#Mann= 3 , 0 , 0
       0     .06       0  141.92     .05       0  186.66     .07       0
Bank Sta=141.92,186.66
Exp/Cntr=0.3,0.1

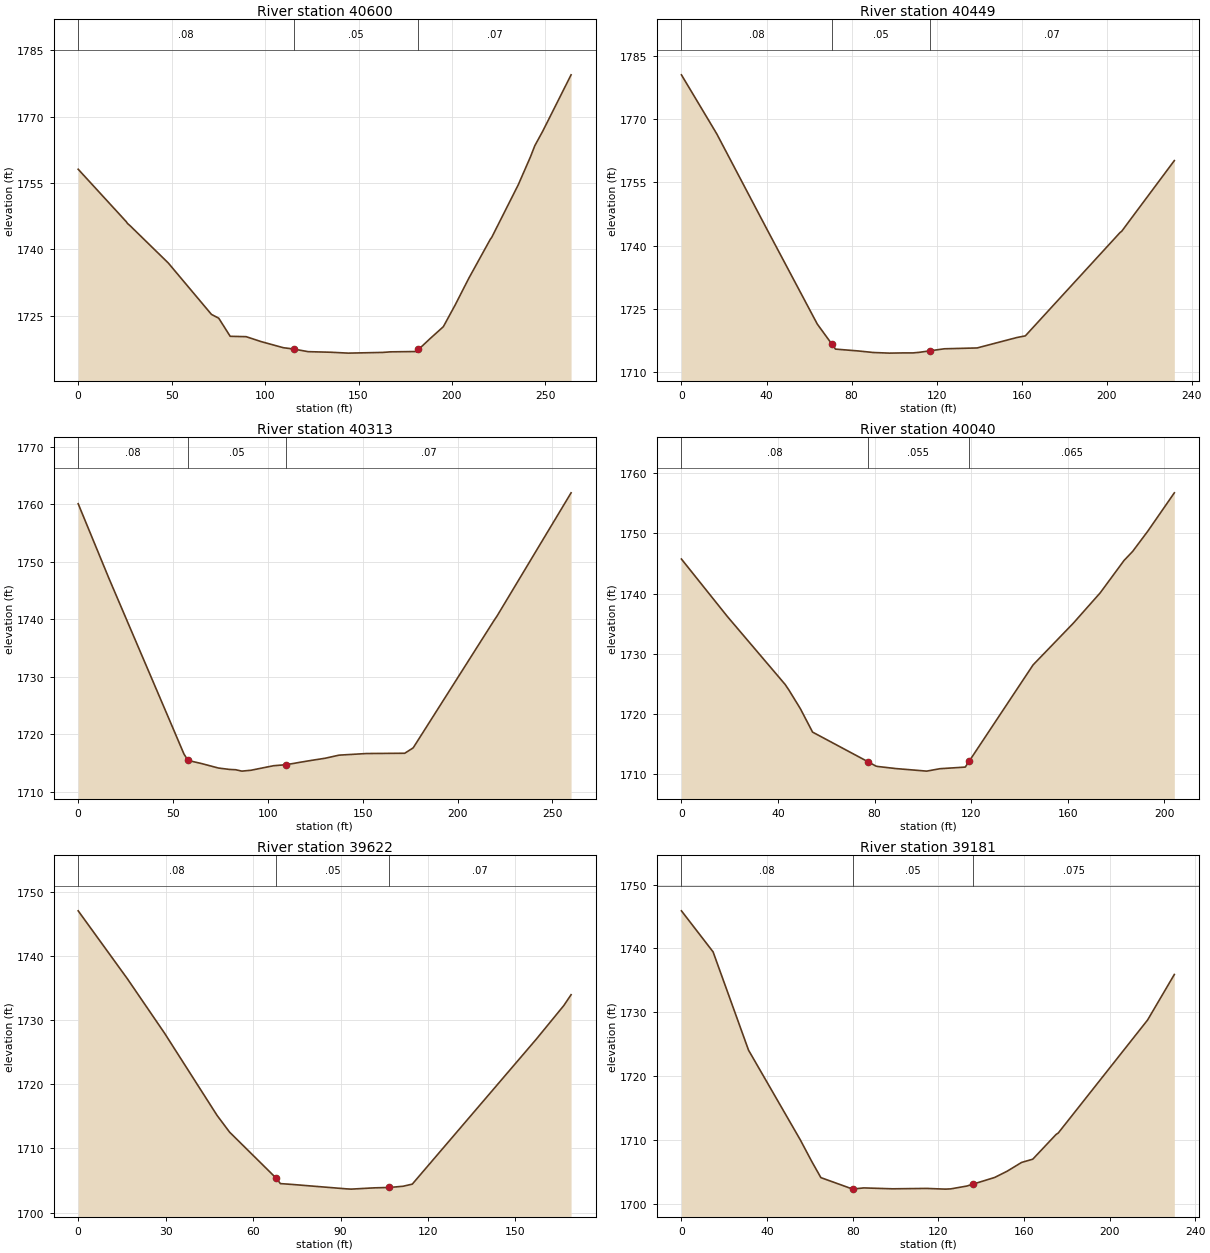
Type RM Length L Ch R = 1 ,40600   ,148.31,151.03,144.61
BEGIN DESCRIPTION:
40522.37
END DESCRIPTION:
XS GIS Cut Line= 6
  895135.6334834  812323.3444378  895101.2580532  812382.7189705
  895074.6960587  812407.7190972  895032.5082169  812429.5944641
  894985.6337475  812460.8441103  894930.9458424  812463.9688701
#Sta/Elev= 30
       0  1758.1   25.71 1746.26   26.41 1745.83   27.79 1745.33   48.19 1736.92
   71.32 1725.29   75.22 1724.43   81.34 1720.34   89.88 1720.26   97.69 1719.17
  109.81 1717.76  115.25 1717.47  123.08 1716.87  135.17 1716.74  144.49 1716.54
  162.97  1716.7  167.18 1716.83  180.88  1716.9  182.09 1717.36  188.23 1719.79
  195.39 1722.51  201.78 1727.47  208.97 1733.42  220.54 1742.28  221.25 1742.67
  235.51 1754.61  242.04 1760.93  244.36 1763.44  248.63 1766.74  263.75 1779.44
#Mann= 3 , 0 , 0
       0     .08       0  115.25     .05       0  182.09     .07       0
Bank Sta=115.25,182.09
Exp/Cntr=0.3,0.1

Type RM Length L Ch R = 1 ,40449   ,183.83,136.7,96.64
BEGIN DESCRIPTION:
40371.34
END DESCRIPTION:
XS GIS Cut Line= 6
  895062.1959954  812224.9068231  895007.5080903  812273.3441844
   894974.695552  812290.5318995  894948.1335575  812309.2814825
  894913.7581273  812337.4063689  894887.1961328   812373.343667
#Sta/Elev= 26
       0 1780.57   16.63 1766.52   40.13 1743.93   63.86 1721.33   70.681716.593
   72.44 1715.37   73.05 1715.35   83.28 1714.93   90.19 1714.57   97.78 1714.42
  104.06 1714.47  108.82 1714.47   110.1 1714.53  110.46 1714.55  111.67  1714.6
  116.72 1714.96   123.6 1715.45  138.93 1715.65  139.09 1715.66  139.45 1715.71
  157.78 1718.14  161.67 1718.52  206.21 1743.09  206.97 1743.38  211.15 1746.23
  231.71 1760.18
#Mann= 3 , 0 , 0
       0     .08       0   70.68     .05       0  116.72     .07       0
Bank Sta=70.68,116.72
Exp/Cntr=0.3,0.1

Type RM Length L Ch R = 1 ,40313   ,305.85,272.85,194.51
XS GIS Cut Line= 6
  894899.6961962  812090.5319103   894902.820956  812140.5311395
   894902.820956  812170.2189179  894890.3208926  812193.6561526
  894849.6959428  812271.7812924  894813.7586448  812326.4691976
#Sta/Elev= 28
       0 1760.11   16.13 1747.19    50.1 1720.96   55.73 1716.59   57.91 1715.45
    64.9 1714.92   73.91 1714.13   79.67 1713.89   83.05 1713.83   86.31 1713.59
   91.07 1713.74   98.43 1714.23  103.02 1714.53  106.35 1714.62  109.01 1714.69
  109.42 1714.71   113.4 1714.92  116.12 1715.08  122.99 1715.46  130.18 1715.83
  137.53 1716.37  151.92 1716.65  172.16  1716.7   176.6 1717.64   194.4 1726.89
   219.1 1739.74  220.85  1740.6  259.84 1762.01
#Mann= 3 , 0 , 0
       0     .08       0   57.91     .05       0  109.42     .07       0
Bank Sta=57.91,109.42
Exp/Cntr=0.3,0.1

Type RM Length L Ch R = 1 ,40040   ,429.28,417.63,411.32
BEGIN DESCRIPTION:
39961.79
END DESCRIPTION:
XS GIS Cut Line= 6
  894579.3832253  812128.0310762  894620.0081751  812193.6561526
  894635.6329983  812221.7810391  894660.6331249  812249.9069497
   894679.383732  812268.6565327  894687.1961436  812298.3443111
#Sta/Elev= 21
       0 1745.72   18.93 1736.24   42.97 1724.92   44.49 1724.02   49.25 1720.92
   54.33 1717.02   77.18 1712.13   80.61 1711.38   81.33 1711.32   88.94 1710.97
  101.61 1710.55  107.08 1710.95  117.59 1711.22  119.141712.155  145.67 1728.16
  162.37 1735.09   173.5 1740.12   183.4  1745.5  186.92 1746.98  193.19 1750.33
   204.2  1756.7
#Mann= 3 , 0 , 0
       0     .08       0   77.18    .055       0  119.14    .065       0
Bank Sta=77.18,119.14
Exp/Cntr=0.3,0.1

Type RM Length L Ch R = 1 ,39622   ,425.74,441.13,452.12
BEGIN DESCRIPTION:
39544.16
END DESCRIPTION:
XS GIS Cut Line= 3
  894254.3836269  812421.7810283  894310.6333998  812474.9060415
  894374.6955843   812540.531118
#Sta/Elev= 20
       0 1747.04   16.87 1736.45   29.59 1727.99   47.65 1715.14   51.93 1712.54
   67.88 1705.38   69.37 1704.51   71.63 1704.44   73.69 1704.37   92.06 1703.69
   93.65 1703.65   99.17 1703.79   101.7 1703.85  106.74 1703.91  106.85 1703.91
  111.47  1704.1  114.61 1704.43  157.14 1727.03  166.58 1732.27  169.08 1733.96
#Mann= 3 , 0 , 0
       0     .08       0   67.88     .05       0  106.74     .07       0
Bank Sta=67.88,106.74
Exp/Cntr=0.3,0.1

Type RM Length L Ch R = 1 ,39181   ,220.81,250.38,290.15
BEGIN DESCRIPTION:
39103.03
END DESCRIPTION:
XS GIS Cut Line= 5
  893937.1954158  812670.2194031  893957.5078907  812732.7186956
   893993.446213   812781.156057  894018.4463396  812813.9685952
  894049.6959859  812868.6565004
#Sta/Elev= 22
       0 1745.89   14.79 1739.47   31.36 1724.09   55.56 1710.05   60.91 1706.67
   65.15 1704.16   79.97 1702.37   85.18 1702.55   98.64 1702.41  114.56 1702.47
  123.25 1702.36  125.85  1702.4  133.33 1702.84  136.111703.128  146.38 1704.19
   152.2 1705.17  158.93 1706.54  164.13 1707.04  175.02 1710.91  176.02 1711.13
  217.79 1728.82  230.27 1735.93
#Mann= 3 , 0 , 0
       0     .08       0   79.97     .05       0  136.11    .075       0
Bank Sta=79.97,136.11
Exp/Cntr=0.3,0.1

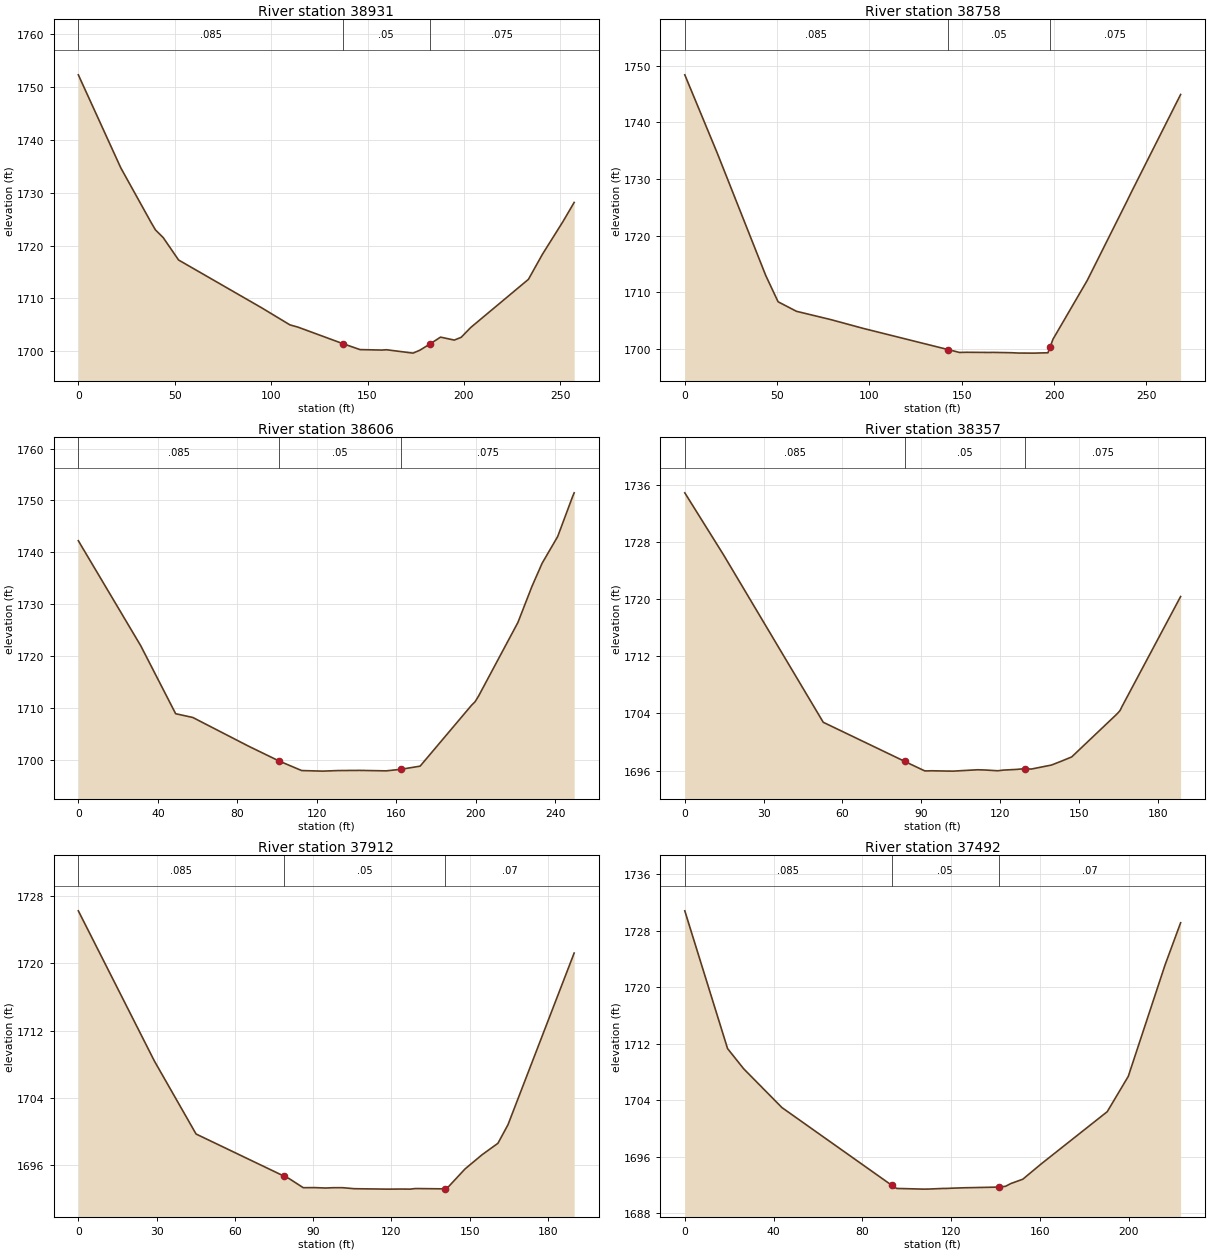
Type RM Length L Ch R = 1 ,38931   ,97.67,172.5,219.6
BEGIN DESCRIPTION:
38852.65
END DESCRIPTION:
XS GIS Cut Line= 6
  893748.1336221  812734.2815876    893749.69549   812781.156057
  893757.5079015  812868.6565004  893773.1337488  812906.1566904
  893777.8203764  812928.0310331  893779.3832684    812987.40659
#Sta/Elev= 24
       0 1752.32   22.01 1734.72   37.64 1724.44   40.02 1722.96   44.03 1721.51
   51.99 1717.27   95.08 1708.22  109.74 1704.99  113.86 1704.57  137.16 1701.44
   146.1 1700.31  157.41 1700.22  159.84 1700.28   173.6 1699.64  177.16  1700.2
  182.231701.334  187.87 1702.67  194.98 1702.11  198.56 1702.63  203.55  1704.5
  233.46 1713.61  240.71 1718.35  251.26 1724.48  257.17 1728.16
#Mann= 3 , 0 , 0
       0    .085       0  137.16     .05       0  182.23    .075       0
Bank Sta=137.16,182.23
Exp/Cntr=0.3,0.1

Type RM Length L Ch R = 1 ,38758   ,107.12,152.03,169.78
BEGIN DESCRIPTION:
38680.15
END DESCRIPTION:
XS GIS Cut Line= 6
  893677.8208939  812732.7186956   893657.508419  812778.0312972
  893591.8833425  812904.5937984  893571.5708676  812920.2186215
  893562.1955641  812942.0939884  893559.0708043  812968.6559829
#Sta/Elev= 26
       0 1748.36   17.63 1734.51   43.85 1712.95   49.66 1708.92   50.53 1708.32
   60.47 1706.64   79.14 1705.17   96.68 1703.62  142.491699.892  146.21 1699.59
  148.74 1699.38  152.36 1699.41  164.63 1699.38  167.01 1699.39  176.97 1699.33
  180.93 1699.27  182.78 1699.27  189.18 1699.26  192.35 1699.29  196.67 1699.32
  197.74 1700.26  199.39 1701.71  217.98 1712.11  239.61 1726.17  241.78 1727.62
  268.52 1744.89
#Mann= 3 , 0 , 0
       0    .085       0  142.49     .05       0  197.74    .075       0
Bank Sta=142.49,197.74
Exp/Cntr=0.3,0.1

Type RM Length L Ch R = 1 ,38606   ,229.59,248.61,270.76
BEGIN DESCRIPTION:
38528.12
END DESCRIPTION:
XS GIS Cut Line= 6
  893588.7585827  812696.7813976  893554.3831525  812740.5311072
  893530.9459178  812759.2817143  893509.0705509  812768.6559937
  893423.1329995  812834.2810701  893391.8833533  812840.5316139
#Sta/Elev= 22
       0 1742.24    31.4 1722.01   48.98 1708.91    57.6 1708.19   85.65 1702.66
   101.2 1699.77  112.39 1697.96  122.97 1697.85  130.88 1697.96  141.67 1697.99
  154.89  1697.9   162.3  1698.2     172 1698.81  197.89 1710.55  199.63 1711.21
   201.4 1712.31  221.23 1726.51  228.25 1733.42  233.37 1737.89  241.21 1743.04
  248.73 1750.75  249.51 1751.47
#Mann= 3 , 0 , 0
       0    .085       0   101.2     .05       0   162.3    .075       0
Bank Sta=101.2,162.3
Exp/Cntr=0.3,0.1

Type RM Length L Ch R = 1 ,38357   ,439.78,445.07,444.95
BEGIN DESCRIPTION:
38279.51
END DESCRIPTION:
XS GIS Cut Line= 2
  893485.6333162  812529.5939466  893305.9458019  812587.4066115
#Sta/Elev= 26
       0 1734.89   14.81 1726.17   52.71 1702.76   83.681697.292    86.3 1696.83
   91.31 1695.96   92.44 1695.95   93.98 1695.97   99.74 1695.93  102.19 1695.92
  111.42 1696.11  114.22 1696.08   119.1 1695.97  121.45 1696.07  123.75 1696.11
  126.54 1696.17  129.34 1696.26  131.92 1696.21  139.58 1696.77  143.34 1697.31
   147.3 1697.91  164.29 1703.84  165.08 1704.14  165.72 1704.42  166.46 1704.98
  188.76 1720.37
#Mann= 3 , 0 , 0
       0    .085       0   83.68     .05       0  129.34    .075       0
Bank Sta=83.68,129.34
Exp/Cntr=0.3,0.1

Type RM Length L Ch R = 1 ,37912   ,437.26,420.45,415.28
BEGIN DESCRIPTION:
37834.44
END DESCRIPTION:
XS GIS Cut Line= 3
  893343.4459919  812115.5310128  893246.5712692  812138.9692717
  893160.6337178  812167.0941581
#Sta/Elev= 24
       0 1726.21   29.16 1708.39   45.14 1699.73   78.841694.733   80.88 1694.43
   86.23 1693.36   90.53 1693.37   94.13 1693.33   94.66 1693.32   97.82 1693.36
  101.32 1693.36  105.82 1693.24  118.16 1693.19  119.57 1693.19  123.71  1693.2
  127.31 1693.19  129.17 1693.26  140.75 1693.22  141.15 1693.22  148.24 1695.58
  154.78 1697.27  160.87 1698.63  164.72 1700.83  190.09  1721.2
#Mann= 3 , 0 , 0
       0    .085       0   78.84     .05       0  140.75     .07       0
Bank Sta=78.84,140.75
Exp/Cntr=0.3,0.1

Type RM Length L Ch R = 1 ,37492   ,416.84,427.84,431.23
BEGIN DESCRIPTION:
37414.00
END DESCRIPTION:
XS GIS Cut Line= 3
  893196.5710158  811699.9062112  893076.2580342  811754.5941163
  892991.8833748  811788.9685224
#Sta/Elev= 25
       0 1730.85   19.26 1711.34   26.52 1708.48   43.74 1702.99   93.12    1692
   93.94 1691.84   95.37 1691.54   95.81 1691.53   96.46 1691.53  107.44 1691.44
  109.85 1691.45  116.68 1691.54  117.81 1691.54  121.75 1691.59  126.88 1691.64
  127.44 1691.64  141.47 1691.73  144.42 1691.84  146.89 1692.24  152.19 1692.84
  160.53 1695.02  190.23 1702.41   199.7 1707.41  216.24 1723.17  223.27 1729.16
#Mann= 3 , 0 , 0
       0    .085       0   93.12     .05       0  141.47     .07       0
Bank Sta=93.12,141.47
Exp/Cntr=0.3,0.1

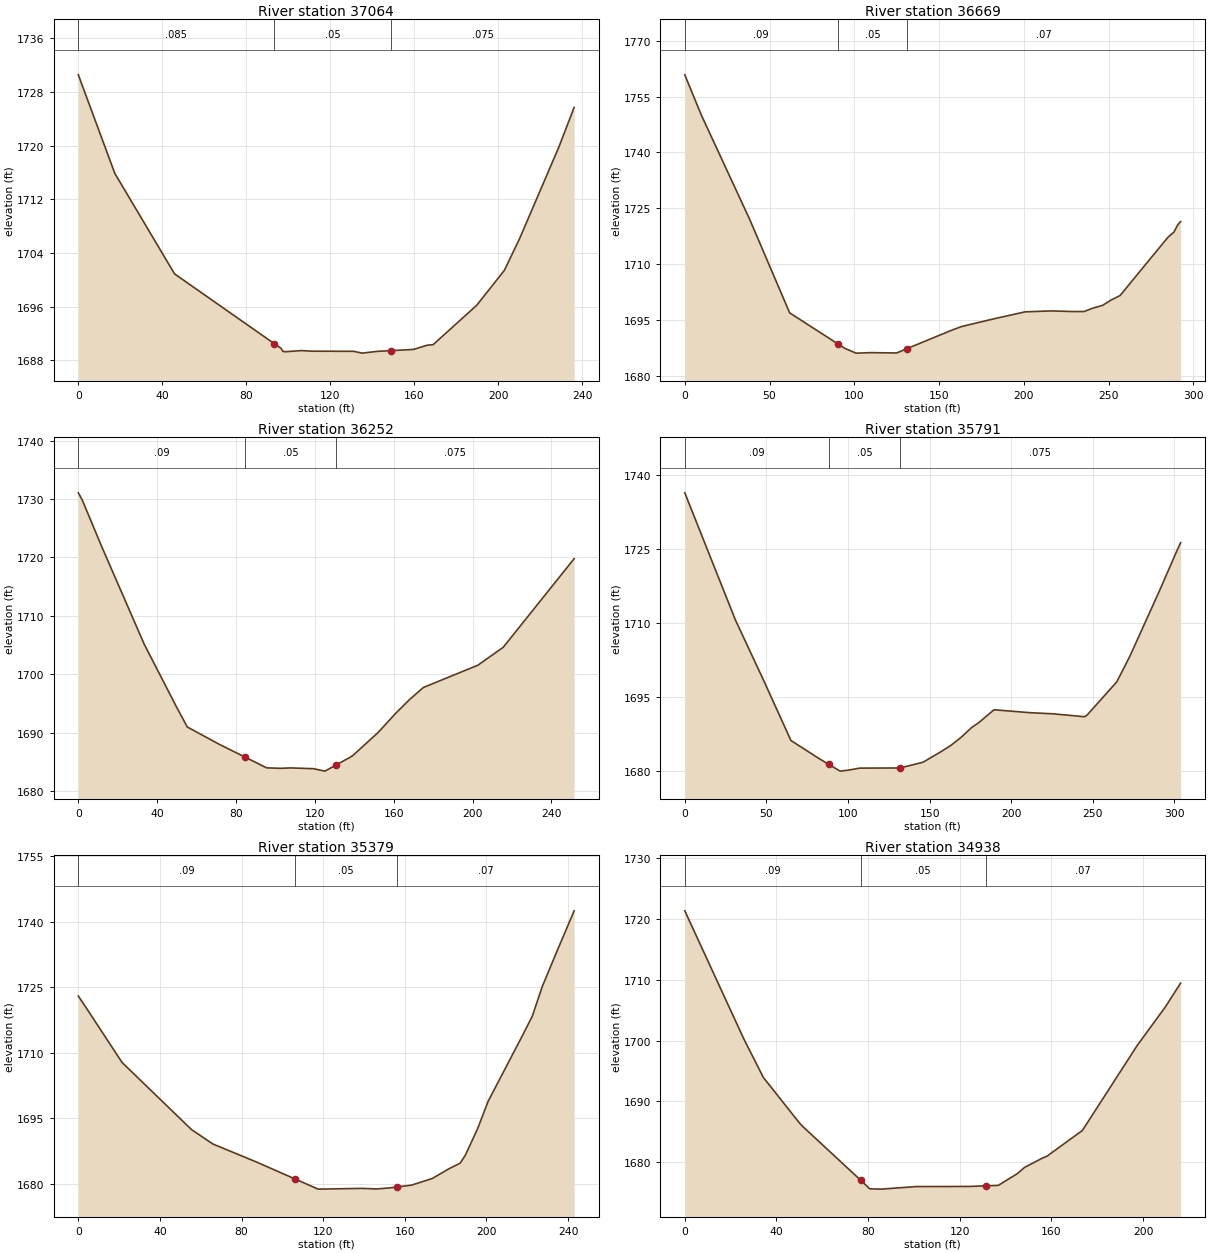
Type RM Length L Ch R = 1 ,37064   ,417.11,395.49,387.7
BEGIN DESCRIPTION:
36986.16
END DESCRIPTION:
XS GIS Cut Line= 5
  893020.0082613  811321.7815996  892982.5080713  811342.0940745
  892932.5088421  811349.9064861   892877.820937  811374.9066128
  892801.2586891   811406.156259
#Sta/Elev= 21
       0 1730.54   17.37 1715.86   45.81 1700.89   93.25  1690.5   96.52  1689.8
   97.41 1689.34   98.57 1689.29  106.36 1689.46  110.87 1689.37  131.07 1689.35
  135.15 1689.08  142.24 1689.34  148.88 1689.45  159.53 1689.63  166.29 1690.27
  168.93 1690.34  189.66  1696.2  202.85 1701.41  210.06 1706.11  228.81 1719.79
  236.08 1725.69
#Mann= 3 , 0 , 0
       0    .085       0   93.25     .05       0  148.88    .075       0
Bank Sta=93.25,148.88
Exp/Cntr=0.3,0.1

Type RM Length L Ch R = 1 ,36669   ,438.35,416.44,379.58
BEGIN DESCRIPTION:
36590.67
END DESCRIPTION:
XS GIS Cut Line= 6
  892823.1330318  810956.1560272  892770.0080187  810982.7190459
   892709.070594  811020.2192359  892690.3210111   811035.844059
  892648.1331693  811053.0317741  892571.5709214  811103.0310033
#Sta/Elev= 28
       0 1760.81    9.72 1750.06   38.31 1722.04   61.86 1697.02   90.151688.737
   94.34 1687.51  100.91 1686.24  102.13 1686.22  109.48 1686.35  124.57 1686.26
   125.4 1686.33  131.09 1687.43  157.88 1692.44  163.45 1693.37  183.42 1695.53
  200.73 1697.28   215.9 1697.53   229.6 1697.36  235.58 1697.38   240.4 1698.23
  246.48 1699.03   251.6 1700.48  256.76 1701.65  285.08 1717.31  288.56 1718.66
  290.66 1720.51   292.1 1721.33  292.49 1721.48
#Mann= 3 , 0 , 0
       0     .09       0   90.15     .05       0  131.09     .07       0
Bank Sta=90.15,131.09
Exp/Cntr=0.3,0.1

Type RM Length L Ch R = 1 ,36252   ,465.34,461.54,448.76
BEGIN DESCRIPTION:
36174.23
END DESCRIPTION:
XS GIS Cut Line= 6
  892482.5086103  810667.0937268  892443.4455283  810704.5939168
  892418.4454016  810737.4064551  892396.5710589  810762.4065818
  892373.1338242  810784.2819486  892313.7582673  810853.0317849
#Sta/Elev= 24
       0 1731.07    1.96 1729.86   11.86 1721.87   33.39 1705.18   49.49 1694.62
   55.27 1690.99   71.61    1688   84.33 1685.87   95.52 1683.99   102.6 1683.91
   107.5 1683.98  119.27 1683.85  125.11 1683.43  130.861684.503  137.83 1685.79
   138.6 1685.99  138.85 1685.98  152.07 1690.04  160.85 1693.28  168.01 1695.68
  175.06 1697.75  202.66 1701.56  215.54 1704.63  251.52  1719.8
#Mann= 3 , 0 , 0
       0     .09       0   84.33     .05       0  130.86    .075       0
Bank Sta=84.33,130.86
Exp/Cntr=0.3,0.1

Type RM Length L Ch R = 1 ,35791   ,383.7,411.92,445.94
BEGIN DESCRIPTION:
35712.68
END DESCRIPTION:
XS GIS Cut Line= 6
  892090.3210434  810406.1563129  892048.1332016  810467.0937376
     892002.8206  810524.9064025  891976.2586055  810568.6561121
  891957.5079984   810590.531479  891904.3829853  810645.2193841
#Sta/Elev= 27
       0 1736.35   31.04 1710.58   48.31 1698.36   65.03 1686.19   82.19 1682.54
   88.211681.352   95.16 1679.98  100.21 1680.18   107.2 1680.59  131.84 1680.62
  145.96 1681.78  157.28 1683.98  163.31 1685.26  169.51 1686.88  175.71  1688.8
  180.02 1689.77  189.48 1692.41  211.52 1691.82  225.53 1691.59  244.83    1691
  245.72 1691.14  246.74 1691.42  264.72 1698.07  272.89 1703.37     291 1716.61
  301.31 1724.44  303.82 1726.26
#Mann= 3 , 0 , 0
       0     .09       0   88.21     .05       0  131.84    .075       0
Bank Sta=88.21,131.84
Exp/Cntr=0.3,0.1

Type RM Length L Ch R = 1 ,35379   ,400.98,440.35,438.42
BEGIN DESCRIPTION:
35300.76
END DESCRIPTION:
XS GIS Cut Line= 6
  891810.6330223  810174.9066774  891752.8203574  810215.5316272
  891716.8830594  810246.7812735  891682.5086533  810262.4060966
  891662.1961784  810268.6566403  891602.8206215  810296.7815268
#Sta/Elev= 24
       0    1723    3.53 1720.55   21.45 1707.79   55.46 1692.43   65.92 1689.13
   87.11 1685.04  106.221681.113  117.53 1678.79  139.15 1678.96  146.13 1678.83
  152.14 1679.05  156.04 1679.28   163.3  1679.7  173.49 1681.23   181.6 1683.44
  187.17 1684.75  189.64 1686.53  195.68 1692.61  200.85  1698.9  217.69 1713.98
   222.5  1718.4  227.38 1725.18  234.58 1733.26  243.01 1742.52
#Mann= 3 , 0 , 0
       0     .09       0  106.22     .05       0  156.04     .07       0
Bank Sta=106.22,156.04
Exp/Cntr=0.3,0.1

Type RM Length L Ch R = 1 ,34938   ,445.3,422.44,420.31
BEGIN DESCRIPTION:
34860.41
END DESCRIPTION:
XS GIS Cut Line= 6
  891679.3828694  809821.7811683  891645.0084633  809832.7193638
  891573.1338673  809834.2812317  891532.5078933  809851.4689468
  891509.0706586  809863.9690101  891474.6962526  809879.5938332
#Sta/Elev= 20
       0 1721.32   25.73  1700.3   34.28 1693.95   49.79 1686.58   51.24 1685.97
    76.7 1677.08   80.74 1675.64    85.9 1675.59  100.91 1676.01     124 1676.03
  131.261676.132  136.83 1676.21  145.08 1678.12   148.3 1679.16  156.01 1680.67
  158.07    1681  173.55 1685.23  197.42 1699.17  209.68 1705.49  216.42 1709.45
#Mann= 3 , 0 , 0
       0     .09       0    76.7     .05       0  131.26     .07       0
Bank Sta=76.7,131.26
Exp/Cntr=0.3,0.1

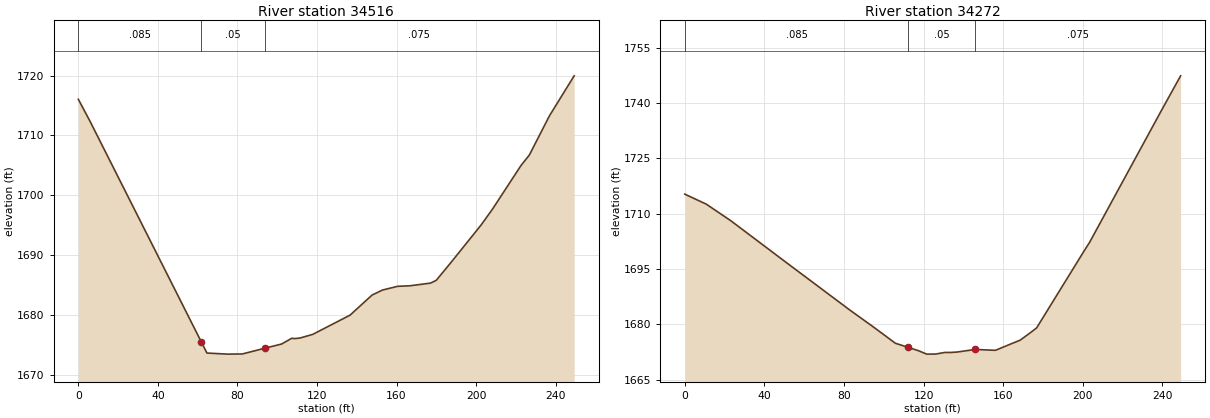
Type RM Length L Ch R = 1 ,34516   ,246.31,244.29,265.04
BEGIN DESCRIPTION:
34437.97
END DESCRIPTION:
XS GIS Cut Line= 6
  891468.4457088  809423.3440818  891407.5082841  809446.7813165
  891379.3833976  809462.4061397  891348.1337514  809481.1567468
  891310.6335614  809499.9063297  891243.4455929  809529.5941081
#Sta/Elev= 26
       0 1716.05       6 1712.29   61.791675.498   64.66 1673.61   74.99 1673.43
   82.49 1673.46   93.66 1674.41   102.2 1675.12  107.29 1676.08  108.83 1676.03
  111.42 1676.12  117.85 1676.73  136.62 1679.95  147.73 1683.32  152.96 1684.15
  160.55 1684.77  166.78 1684.86   177.1 1685.31  179.96 1685.77  187.54 1688.83
  202.54 1695.04  208.44 1697.78   222.6 1704.99  226.76 1706.72  236.86 1713.28
  249.29 1719.97
#Mann= 3 , 0 , 0
       0    .085       0   61.79     .05       0   93.66    .075       0
Bank Sta=61.79,93.66
Exp/Cntr=0.3,0.1

Type RM Length L Ch R = 1 ,34272   ,142.23,182.8,197.15
BEGIN DESCRIPTION:
34193.67
END DESCRIPTION:
XS GIS Cut Line= 6
  891387.1958092  809206.1563775  891295.0087382  809226.4688524
  891263.7580678  809248.3442193  891234.0713135  809259.2813906
  891198.1329913  809263.9690424  891149.6956299  809259.2813906
#Sta/Elev= 29
       0 1715.29   10.81 1712.58   23.21 1708.05   50.87 1696.81   82.08 1684.21
   82.15 1684.17   94.45 1679.41  105.82 1674.87  112.281673.744  116.32 1673.04
  117.28 1672.88  121.57 1671.92  126.04 1671.94  130.61 1672.37  133.65 1672.37
  136.72 1672.48  146.01 1673.19  155.56 1672.96   156.1 1672.97  157.06 1673.16
  164.24 1674.77   168.5  1675.7   173.4 1677.63  176.79 1679.03  200.48 1699.75
  203.43 1702.25     239 1737.49  239.23 1737.72  249.14 1747.37
#Mann= 3 , 0 , 0
       0    .085       0  112.28     .05       0  146.01    .075       0
Bank Sta=112.28,146.01
Exp/Cntr=0.3,0.1