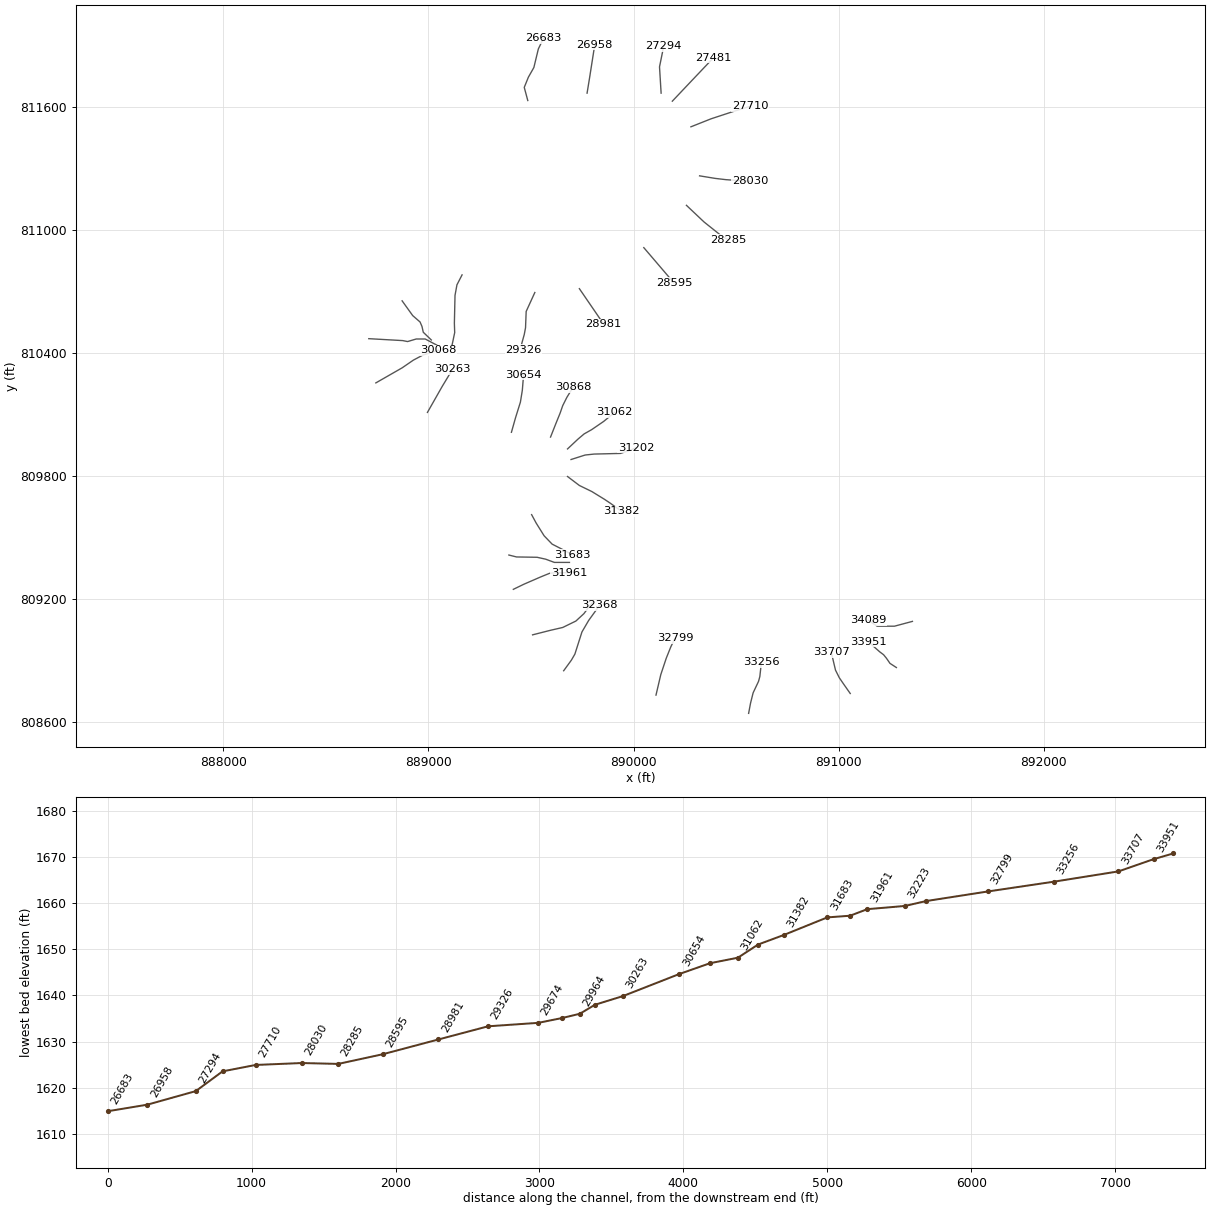
HEC-RAS study lds_big_laurel_crk.prj: lds_big_laurel_crk

--- lds_big_laurel_crk.g20 (geometry) --- (continued)

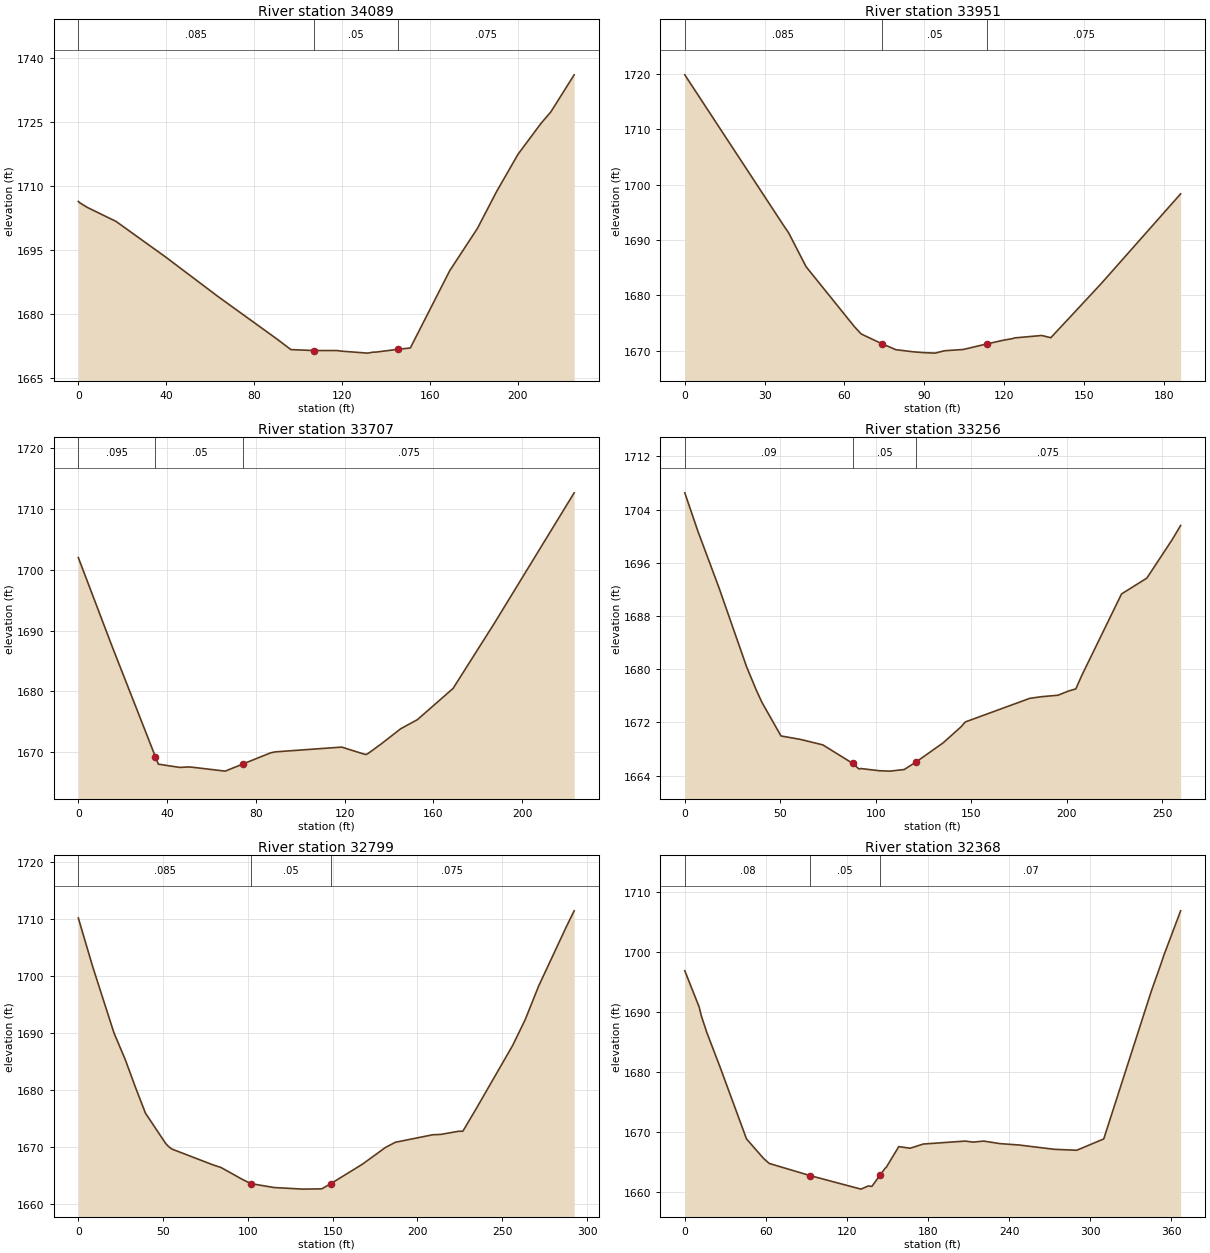
Type RM Length L Ch R = 1 ,34089   ,204.6,138.23,104.27
BEGIN DESCRIPTION:
34010.88
END DESCRIPTION:
XS GIS Cut Line= 6
  891359.0709227  809092.0939396  891271.5704794   809068.656705
  891243.4455929   809068.656705  891207.5082949   809068.656705
    891187.19582   809068.656705  891145.0079782  809096.7815914
#Sta/Elev= 23
       0 1706.38     .65 1706.08    4.09 1704.99   17.18  1701.7   39.69 1693.37
   63.58 1684.08   90.58 1674.04   96.74 1671.63  107.14 1671.41  117.74 1671.41
  119.61 1671.27  131.65  1670.8  134.31 1671.04  135.31 1671.03  145.37 1671.69
   151.1 1672.01  169.06 1690.17  181.61 1700.04  190.41 1708.76  200.16  1717.5
  210.59 1724.72  215.06 1727.41  225.66  1736.1
#Mann= 3 , 0 , 0
       0    .085       0  107.14     .05       0  145.37    .075       0
Bank Sta=107.14,145.37
Exp/Cntr=0.3,0.1

Type RM Length L Ch R = 1 ,33951   ,248.23,243.94,210.36
BEGIN DESCRIPTION:
33872.64
END DESCRIPTION:
XS GIS Cut Line= 6
  891280.9457829  808867.0938237  891249.6961366  808887.4062986
  891232.5084215  808912.4064253  891218.4454662  808929.5941404
  891199.6958833  808943.6560716  891145.0079782  808992.0944571
#Sta/Elev= 26
       0 1719.87   37.27 1692.53   39.03 1691.29   45.57 1685.18   63.73 1674.34
   66.22 1673.04   67.61 1672.71   73.92 1671.28   79.31 1670.17   86.03 1669.78
   89.75 1669.64   89.82 1669.64   94.04 1669.55   97.59 1669.98  104.65 1670.21
  113.25 1671.19  113.74 1671.24  119.48 1671.86  122.72 1672.14  123.16 1672.17
  123.87  1672.3  134.12 1672.74  137.53 1672.34  144.27 1675.81  156.48 1682.13
  186.31 1698.35
#Mann= 3 , 0 , 0
       0    .085       0   73.92     .05       0  113.74    .075       0
Bank Sta=73.92,113.74
Exp/Cntr=0.3,0.1

Type RM Length L Ch R = 1 ,33707   ,495.2,450.82,360.05
BEGIN DESCRIPTION:
33628.71
END DESCRIPTION:
XS GIS Cut Line= 5
   891055.945667  808740.5313225  891023.1331288  808787.4068161
  891002.8206539  808817.0935704  890984.0710709  808854.5937604
   890963.758596  808940.5313118
#Sta/Elev= 27
       0    1702   15.26 1687.37   34.731669.268   36.04 1668.05   41.51 1667.74
   45.71 1667.51   49.89 1667.59   52.36  1667.5   65.69 1666.92   66.17  1666.9
   74.311668.095   86.67 1669.91    88.8 1670.07   93.19 1670.18   93.82  1670.2
  118.68 1670.85  128.63 1669.71  129.72 1669.63   130.5 1669.79   133.8 1670.65
  135.12 1671.02  136.23  1671.3  145.28 1673.87  152.78 1675.36  168.85 1680.49
  187.43 1691.19  223.42 1712.65
#Mann= 3 , 0 , 0
       0    .095       0   34.73     .05       0   74.31    .075       0
Bank Sta=34.73,74.31
Exp/Cntr=0.3,0.1

Type RM Length L Ch R = 1 ,33256   ,460,456.78,453.17
BEGIN DESCRIPTION:
33177.89
END DESCRIPTION:
XS GIS Cut Line= 6
  890560.6338578  808643.6565998  890570.0081371  808693.6568532
  890582.5082005  808743.6560823  890609.0712191  808799.9068794
  890615.3207387  808823.3441141  890623.1331503  808893.6568424
#Sta/Elev= 30
       0 1706.53    6.88 1700.74   17.91 1692.25   32.38 1680.35   37.59 1676.75
   40.44 1674.99   50.39 1669.95   60.48 1669.44   72.29 1668.61   87.93 1665.83
   91.22 1664.98   92.22 1665.05  101.83 1664.72  107.44 1664.66  114.91  1664.9
  121.161666.041  135.28 1668.91  144.66 1671.32  146.84 1672.03   147.3  1672.1
  180.68 1675.61   186.6 1675.85  195.47 1676.08  200.97 1676.71  204.79 1677.03
  207.84 1679.01  228.74 1691.32     242  1693.7  255.38 1699.54  259.68 1701.62
#Mann= 3 , 0 , 0
       0     .09       0   87.93     .05       0  121.16    .075       0
Bank Sta=87.93,121.16
Exp/Cntr=0.3,0.1

Type RM Length L Ch R = 1 ,32799   ,451.44,430.79,411.12
BEGIN DESCRIPTION:
32721.11
END DESCRIPTION:
XS GIS Cut Line= 5
   890109.070734   808732.718911  890132.5079687  808832.7194177
  890159.0709873  808912.4064253  890180.9463542  808967.0943304
  890201.2588291  809009.2811481
#Sta/Elev= 30
       0 1710.23    8.48 1701.66   21.04 1690.01    27.7 1685.31      34 1680.22
   39.58 1675.92   51.53 1670.58   53.18 1670.05   55.23 1669.59   79.56  1666.8
   84.12 1666.36   96.63 1664.28  101.74 1663.52  115.47 1662.83  132.61 1662.55
  143.61  1662.6  148.791663.494  167.53 1666.93  181.15 1669.88  186.98 1670.79
  208.98 1672.11  213.71 1672.17  224.14 1672.72  226.78 1672.73  234.67  1676.7
   256.2 1687.84  263.57 1692.36  271.44 1698.23  287.75 1708.65  292.43 1711.49
#Mann= 3 , 0 , 0
       0    .085       0  101.74     .05       0  148.79    .075       0
Bank Sta=101.74,148.79
Exp/Cntr=0.3,0.1

Type RM Length L Ch R = 1 ,32368   ,207.14,145.01,37.89
BEGIN DESCRIPTION:
32290.32
END DESCRIPTION:
XS GIS Cut Line= 6
  889659.0705022  808851.4690006  889696.5706922  808903.0311218
  889713.7584073  808932.7189002  889748.1338375  809040.5318185
  889780.9453516  809096.7815914  889834.0703647  809170.2190795
#Sta/Elev= 30
       0 1696.87   10.69 1690.79   12.23 1689.35   16.31 1686.57   26.02 1680.86
   45.68 1668.83   58.41 1665.55    62.5 1664.74   92.68 1662.72  130.37 1660.46
  135.72 1660.98  138.47 1660.92  144.751662.857   148.1 1663.89  149.27 1664.15
  158.38 1667.55  166.83 1667.28  176.56 1667.98  207.55 1668.47  213.36  1668.3
  221.27 1668.47  233.14 1668.05  247.28 1667.82   273.4  1667.1  290.12 1666.94
  310.08 1668.83  345.32 1693.49   352.1 1697.79  354.39 1699.34  366.98 1706.86
#Mann= 3 , 0 , 0
       0     .08       0   92.68     .05       0  144.75     .07       0
Bank Sta=92.68,144.75
Exp/Cntr=0.3,0.1

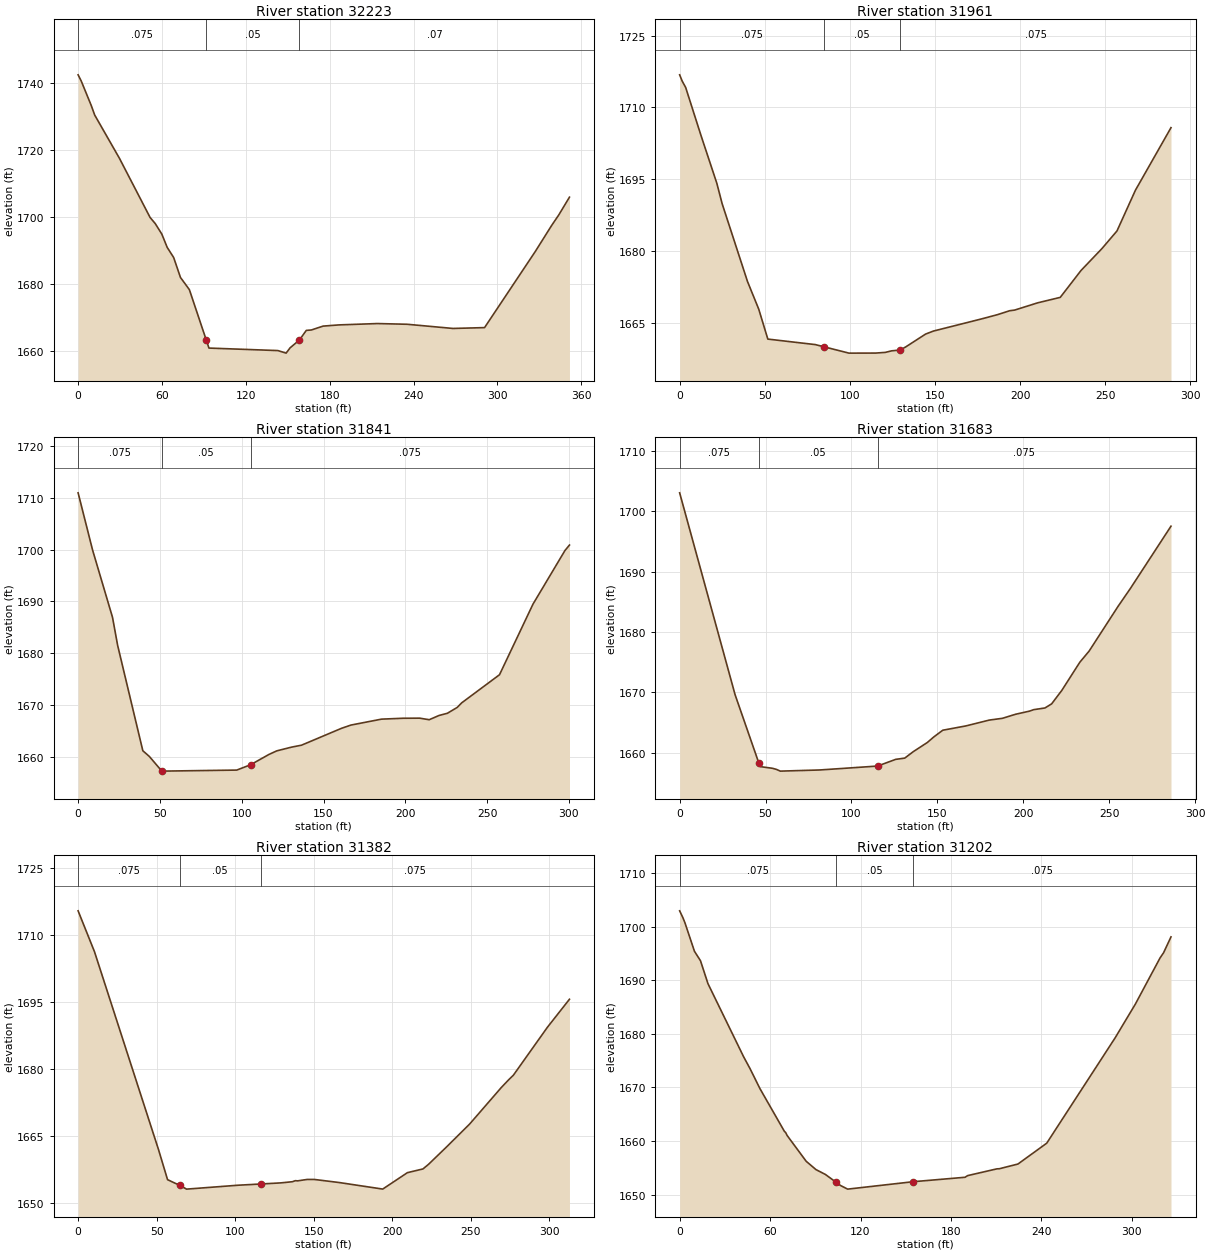
Type RM Length L Ch R = 1 ,32223   ,253.97,262.35,238.99
BEGIN DESCRIPTION:
32145.31
END DESCRIPTION:
XS GIS Cut Line= 6
  889507.5078743  809026.4688632  889593.4454257    809048.34423
  889654.3828504  809062.4061612  889718.4460591  809093.6568316
  889757.5081169  809129.5941297  889802.8207185  809190.5315544
#Sta/Elev= 30
       0 1742.53    2.24 1740.68    9.35 1733.42   11.88 1730.51   29.61 1717.57
   51.48 1699.94   55.18  1698.1   59.88 1694.97   63.73    1691   68.36 1687.97
   73.22 1682.02    79.6 1678.37   91.761663.224   93.61 1660.92  142.93 1660.17
  148.81 1659.41  151.67    1661   158.3 1663.31  163.25  1666.2  166.83 1666.32
  175.29 1667.48   186.7 1667.84  214.14 1668.24  235.37 1668.03  268.18 1666.78
  290.77 1667.03  327.12  1689.8  338.69 1697.49  343.85 1700.67  351.51 1705.99
#Mann= 3 , 0 , 0
       0    .075       0   91.76     .05       0   158.3     .07       0
Bank Sta=91.76,158.3
Exp/Cntr=0.3,0.1

Type RM Length L Ch R = 1 ,31961   ,147.84,119.58,50.16
BEGIN DESCRIPTION:
31882.96
END DESCRIPTION:
XS GIS Cut Line= 6
  889413.7579114  809248.3442193  889465.3210567   809273.344346
  889548.1338483   809309.281644  889590.3206659  809326.4693591
  889620.0084443  809329.5941189  889685.6335208  809329.5941189
#Sta/Elev= 30
       0 1716.81    1.48 1715.51    3.53 1714.18   12.65 1704.03   21.86 1694.15
   24.94 1689.93   39.85 1673.67   46.47 1667.88    51.8 1661.64   79.72 1660.49
   84.81 1660.03   99.45 1658.71  114.99 1658.72  120.75 1658.86  124.57 1659.19
  129.45 1659.35  132.72 1659.99  144.43 1662.68     149 1663.31   177.3 1665.85
  186.67 1666.74  193.86 1667.56  196.81  1667.7   210.3 1669.21  223.56 1670.35
   235.8 1675.98  248.01 1680.52  256.89 1684.22  267.72 1692.72  288.61 1705.78
#Mann= 3 , 0 , 0
       0    .075       0   84.81     .05       0  129.45    .075       0
Bank Sta=84.81,129.45
Exp/Cntr=0.3,0.1

Type RM Length L Ch R = 1 ,31841   ,213.36,158.01,75.94
BEGIN DESCRIPTION:
31763.38
END DESCRIPTION:
XS GIS Cut Line= 6
  889391.8835686  809415.5316703  889429.3837587  809406.1563667
  889529.3832412  809404.5934747   889571.571083  809395.2191954
  889613.7579006  809379.5943722  889687.1953886  809379.5943722
#Sta/Elev= 27
       0 1710.93    8.85  1699.9   21.04 1686.92   24.15 1681.55   39.56 1661.22
   43.54 1660.12   51.19 1657.29   96.95 1657.49  105.44 1658.52  116.62  1660.5
  121.38 1661.19  130.39 1661.91  136.56 1662.29  160.99 1665.54   166.8 1666.17
  185.45 1667.31  198.65 1667.48  208.72  1667.5  214.61  1667.2  220.62 1668.02
  225.72 1668.44  231.76 1669.58  234.42 1670.44  257.57 1675.87  278.04 1689.48
  297.55  1699.8  300.32 1700.86
#Mann= 3 , 0 , 0
       0    .075       0   51.19     .05       0  105.44    .075       0
Bank Sta=51.19,105.44
Exp/Cntr=0.3,0.1

Type RM Length L Ch R = 1 ,31683   ,273.99,301.15,331.36
BEGIN DESCRIPTION:
31605.37
END DESCRIPTION:
XS GIS Cut Line= 6
  889502.8212467  809612.4068997  889524.6955894  809571.7819499
  889563.7586714  809509.2816332  889602.8207292  809468.6566834
  889666.8829137  809435.8441452   889699.695452  809417.0935381
#Sta/Elev= 29
       0 1703.07   32.28 1669.59   46.14 1658.23   46.81 1657.68   54.02  1657.4
    56.4 1657.21   58.59 1656.93   81.52 1657.12  115.18 1657.77  125.74 1658.88
  131.02 1659.09  135.99 1660.16  144.12 1661.67  147.97 1662.61  153.15 1663.71
  166.68 1664.43  180.17 1665.39  187.93 1665.69  195.53 1666.36  203.67 1666.88
  206.04 1667.12  212.61  1667.4  216.49 1668.08  222.44 1670.32   232.9 1674.98
  238.34 1676.84  255.24 1684.28  262.37 1687.23  285.97 1697.54
#Mann= 3 , 0 , 0
       0    .075       0   46.14     .05       0  115.18    .075       0
Bank Sta=46.14,115.18
Exp/Cntr=0.3,0.1

Type RM Length L Ch R = 1 ,31382   ,144.72,180.27,266.85
BEGIN DESCRIPTION:
31304.22
END DESCRIPTION:
XS GIS Cut Line= 6
  889677.8211093  809798.3439336  889735.6337742   809754.594224
  889796.5711989  809724.9064456  889857.5086236  809687.4062556
  889885.6335101  809668.6566726   889940.320391  809629.5935906
#Sta/Elev= 26
       0 1715.47   10.44  1706.3   51.21 1661.97   56.95 1655.25   64.59 1653.99
   69.08 1653.13   102.1 1654.01  116.481654.281  129.13 1654.53  136.47 1654.79
  138.27 1655.02  139.76 1654.98  145.87  1655.3  150.57 1655.29  166.16 1654.61
  193.96 1653.14  209.67 1656.82  219.56 1657.65  223.19 1658.71  234.99 1662.72
  249.29 1667.71  269.45 1675.89  274.35  1677.7   277.1 1678.63  298.83  1689.4
  312.84 1695.66
#Mann= 3 , 0 , 0
       0    .075       0   64.59     .05       0  116.48    .075       0
Bank Sta=64.59,116.48
Exp/Cntr=0.3,0.1

Type RM Length L Ch R = 1 ,31202   ,82.74,139.89,191.57
BEGIN DESCRIPTION:
31123.95
END DESCRIPTION:
XS GIS Cut Line= 6
  889695.0088244  809881.1567252  889763.7586606  809903.0310679
  889807.5083702  809907.7187197  889935.6337634  809910.8434795
   889979.383473  809924.9064348  890012.1960112  809938.9693901
#Sta/Elev= 30
       0 1702.94    2.13 1701.68    3.53  1700.7    9.82  1695.4   13.83 1693.63
   18.79 1689.36   42.49  1675.7   46.76 1673.48   53.23 1669.81   69.51 1661.81
   70.29 1661.61   71.33 1661.04   83.97 1656.23   90.47 1654.68   96.68 1653.78
  103.43  1652.4  106.73 1651.72  111.48 1651.04  154.931652.422  189.37 1653.25
   191.1 1653.56  210.49 1654.82  212.12 1654.84  224.47 1655.72  243.57 1659.61
  289.04 1679.29   302.4 1685.56  318.75 1694.15  321.13 1695.14  326.02 1698.08
#Mann= 3 , 0 , 0
       0    .075       0  103.43     .05       0  154.93    .075       0
Bank Sta=103.43,154.93
Exp/Cntr=0.3,0.1

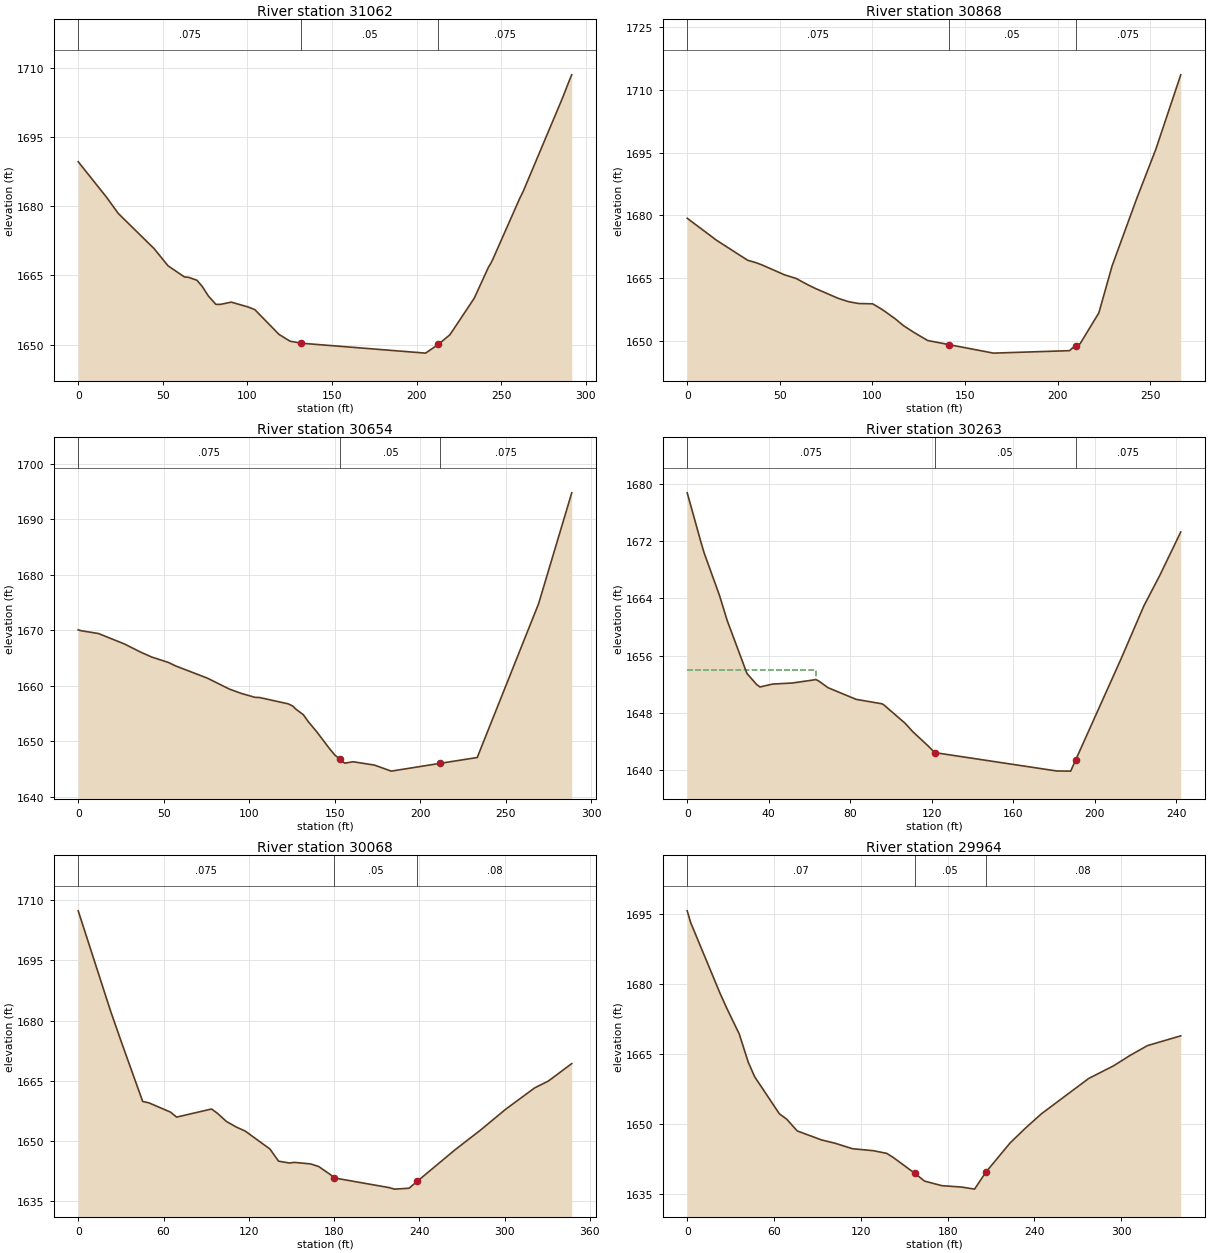
Type RM Length L Ch R = 1 ,31062   ,131.76,194.36,225.58
BEGIN DESCRIPTION:
30984.06
END DESCRIPTION:
XS GIS Cut Line= 6
  889677.8211093  809932.7188464  889729.3832304  809981.1562077
  889759.0710089  810006.1563344  889795.0083069  810026.4688093
  889854.3838638  810067.0937591  889907.5078528  810110.8434687
#Sta/Elev= 30
       0 1689.64   16.81 1681.91   23.63 1678.45   44.91 1670.79   53.06  1667.1
   62.78 1664.68   65.13 1664.61   70.16 1663.97   73.33 1662.61   76.91 1660.56
   81.36 1658.75   83.93 1658.74   90.45 1659.23  100.48 1658.17  104.34 1657.61
  118.69 1652.23  125.13 1650.78  131.68 1650.34  205.25 1648.19  212.68 1650.06
  219.65 1652.18  233.97 1660.07   242.4  1666.8  243.74  1667.6  244.99 1668.53
  260.81 1681.65  262.91 1683.21  286.09 1703.39  290.59 1707.61   291.6 1708.45
#Mann= 3 , 0 , 0
       0    .075       0  131.68     .05       0  212.68    .075       0
Bank Sta=131.68,212.68
Exp/Cntr=0.3,0.1

Type RM Length L Ch R = 1 ,30868   ,199.72,213.41,233.78
BEGIN DESCRIPTION:
30789.71
END DESCRIPTION:
XS GIS Cut Line= 6
  889595.0083177  809990.5315113  889621.5713363  810057.7194798
  889641.8838112  810107.7187089  889654.3828504   810143.656007
  889674.6963495  810184.2819809  889704.3831037  810232.7193423
#Sta/Elev= 30
       0 1679.28   15.79 1674.03   32.66 1669.22   37.14 1668.65   40.53 1668.08
   52.58 1665.73   58.88 1664.86      65 1663.38   69.33 1662.45   81.63 1660.09
   86.97 1659.33   92.46 1658.87  100.14 1658.79  104.48 1657.66  106.67 1657.01
  112.37 1655.19   116.7 1653.59  122.59  1651.9  129.86 1650.01  141.111649.048
  165.36 1646.99  206.48 1647.58  207.89 1648.16  209.69 1648.61  212.17 1649.25
  222.28 1656.62  229.41 1667.83  242.78 1684.06  253.02 1695.75   266.5 1713.62
#Mann= 3 , 0 , 0
       0    .075       0  141.11     .05       0  209.69    .075       0
Bank Sta=141.11,209.69
Exp/Cntr=0.3,0.1

Type RM Length L Ch R = 1 ,30654   ,413.17,391.11,373.79
BEGIN DESCRIPTION:
30576.30
END DESCRIPTION:
XS GIS Cut Line= 5
   889404.383632   810013.968746  889424.6961069  810085.8443662
  889448.1333416  810160.8437221  889457.5086451   810218.656387
  889463.7581647  810295.2186348
#Sta/Elev= 30
       0 1670.08    1.87 1669.92   11.84 1669.42   27.05 1667.54   36.52 1666.07
      43 1665.19   52.69 1664.22   56.97 1663.59    75.6 1661.38   88.35 1659.43
   95.31 1658.65   103.4 1657.93  105.97 1657.91  122.83 1656.76  125.48 1656.37
  127.13 1655.85  131.71 1654.79  134.51 1653.58  139.54 1651.72     147 1648.69
  150.17 1647.52  153.27 1646.77  155.84 1646.08  160.83 1646.34  173.34 1645.73
  183.07 1644.65  211.83 1646.06  233.37  1647.1  269.25 1674.78  288.65 1694.75
#Mann= 3 , 0 , 0
       0    .075       0  153.27     .05       0  211.83    .075       0
Bank Sta=153.27,211.83
Exp/Cntr=0.3,0.1

Type RM Length L Ch R = 1 ,30263   ,264.48,194.73,162.57
BEGIN DESCRIPTION:
30185.19
END DESCRIPTION:
XS GIS Cut Line= 3
    888995.00835  810110.8434687   889066.882946  810237.4059699
  889116.8831994  810320.2187615
#Sta/Elev= 27
       0 1678.76    6.73 1671.89    8.29 1670.38   15.88  1664.4   19.63 1660.92
   29.33 1653.52      34    1652   35.69 1651.63   42.01 1652.04   51.48 1652.18
   63.26 1652.66   64.63 1652.45   69.13 1651.53   82.93  1649.9   95.58 1649.28
   96.48 1649.14  106.89 1646.58  110.75 1645.38   118.5 1643.33  121.47 1642.46
  181.41 1639.89  188.24 1639.87  190.631641.385  212.78 1655.43  224.18 1662.96
  232.05 1667.25  242.28 1673.28
#Mann= 3 , 0 , 0
       0    .075       0  121.47     .05       0  190.63    .075       0
#XS Ineff= 2 , 0
       0   63.26    1654               0
Permanent Ineff=
       F       F
Bank Sta=121.47,190.63
Exp/Cntr=0.3,0.1

Type RM Length L Ch R = 1 ,30068   ,181.28,104.82,82.01
BEGIN DESCRIPTION:
29990.46
END DESCRIPTION:
XS GIS Cut Line= 5
  888743.4462396   810254.593685  888871.5706086  810328.0311731
  888926.2585137  810365.5313631  888973.1329831  810390.5314898
  889049.6962551  810413.9687244
#Sta/Elev= 30
       0 1707.35   22.64 1682.51   30.71 1674.31   45.37 1659.83    49.7  1659.5
   64.95 1657.18   69.24 1655.94    93.8 1657.96   98.06 1656.85  104.24 1654.86
  111.27 1653.45  117.44 1652.47  134.86 1647.99  140.92 1644.96  148.53  1644.5
   152.1 1644.66  163.55 1644.27   169.2 1643.62  177.95 1641.47   179.8  1640.8
  218.68 1638.37  222.54 1637.99   232.7 1638.21  238.611639.979  265.33 1647.86
  282.71 1652.62  300.81 1657.93  321.06 1663.21  330.79 1664.94  347.18 1669.28
#Mann= 3 , 0 , 0
       0    .075       0   179.8     .05       0  238.61     .08       0
Bank Sta=179.8,238.61
Exp/Cntr=0.3,0.1

Type RM Length L Ch R = 1 ,29964   ,216.71,122.34,35.88
BEGIN DESCRIPTION:
29885.64
END DESCRIPTION:
XS GIS Cut Line= 6
  888709.0708094  810470.2184974  888874.6953684   810460.844218
  888898.1336272  810456.1565662  888940.3204448  810468.6566296
  888984.0711786  810468.6566296  889040.3209515  810438.9688511
#Sta/Elev= 30
       0 1695.68    2.43 1693.13   22.84  1677.9   27.63 1674.63   35.95 1669.31
   42.18 1663.26   46.64 1660.12    63.7 1652.19   68.82 1651.02   76.07 1648.51
   92.79 1646.59  102.25 1645.87  114.24  1644.7   128.6 1644.28  137.95  1643.7
  142.15 1642.89  157.27 1639.45  164.06 1637.76  176.04 1636.78   189.8 1636.48
  198.64 1636.04  206.38 1639.65  223.24 1645.95   233.8 1649.11  244.83 1652.18
  277.55 1659.76  294.63 1662.45  306.26 1664.72  318.17  1666.8  341.15 1668.89
#Mann= 3 , 0 , 0
       0     .07       0  157.27     .05       0  206.38     .08       0
Bank Sta=157.27,206.38
Exp/Cntr=0.3,0.1

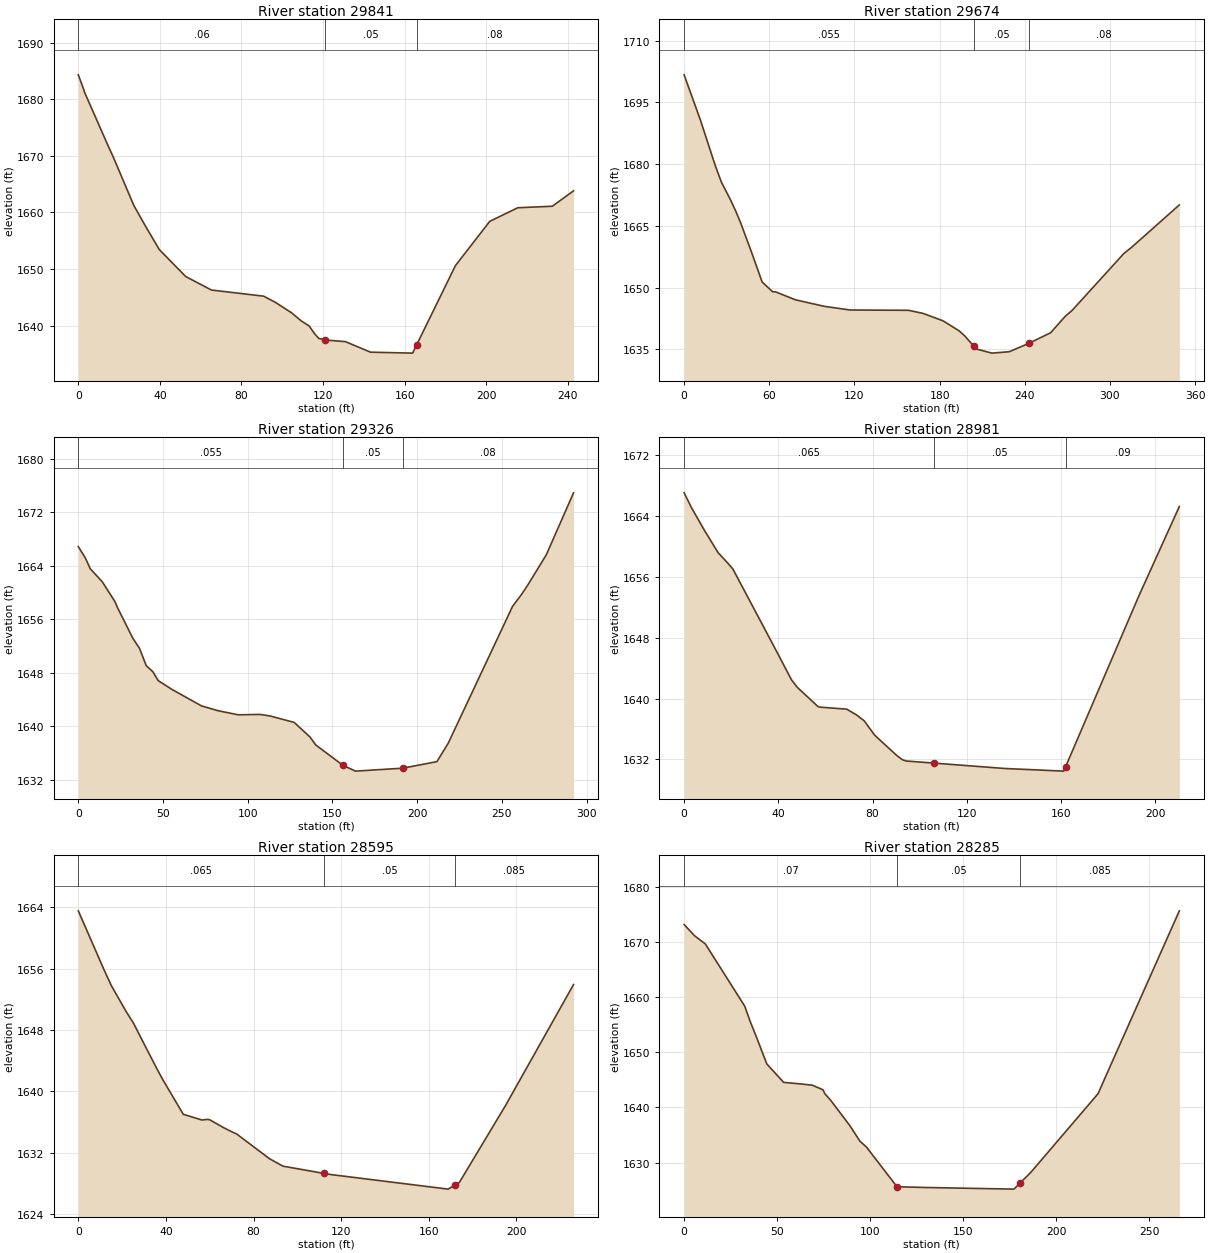
Type RM Length L Ch R = 1 ,29841   ,279.46,166.84,150.48
BEGIN DESCRIPTION:
29763.30
END DESCRIPTION:
XS GIS Cut Line= 6
  888871.5706086  810654.5936635  888923.1337539  810582.7190674
  888959.0710519  810551.4694212  888968.4463555  810529.5940543
  888974.6958751  810501.4691678  889013.7579329  810463.9689778
#Sta/Elev= 27
       0 1684.34    2.69 1681.72    2.96 1681.34   15.05 1671.44   16.96 1669.97
   27.22 1661.24   33.22 1657.41   39.76 1653.42   52.66 1648.67   65.29 1646.28
   90.94 1645.19   96.66  1644.1  104.64 1642.24  109.33 1640.82  113.16 1639.94
  115.89 1638.54  117.93 1637.72  121.12 1637.44  131.01 1637.15  143.29 1635.29
  163.94 1635.12  165.991636.631  184.94  1650.6  201.75 1658.42   215.5 1660.83
  232.44  1661.1  242.85 1663.82
#Mann= 3 , 0 , 0
       0     .06       0  121.12     .05       0  165.99     .08       0
Bank Sta=121.12,165.99
Exp/Cntr=0.3,0.1

Type RM Length L Ch R = 1 ,29674   ,371.97,348.58,334.86
BEGIN DESCRIPTION:
29596.46
END DESCRIPTION:
XS GIS Cut Line= 6
  889163.7586929  810781.1561647  889138.7585663  810732.7188033
  889129.3832627  810681.1566821  889126.2585029  810545.2188774
  889127.8203707  810499.9062758  889115.3213316  810440.5317431
#Sta/Elev= 30
       0 1701.72   11.42  1690.8   22.02 1679.58   26.27 1675.64   32.66 1671.35
   36.46 1668.52   39.81 1665.76   47.44 1658.67   54.97 1651.37   62.32    1649
    64.5 1648.95   78.45 1647.03   98.84 1645.44  116.94 1644.55  158.07 1644.48
  168.34 1643.73  182.44 1641.92  193.76 1639.49  197.93 1638.18  204.121635.743
  206.02 1635.06  216.87 1634.07  229.12 1634.42   242.9 1636.45   258.2 1639.02
  268.74  1643.1   273.2 1644.39  309.85  1658.3  314.95 1659.69  348.92  1670.1
#Mann= 3 , 0 , 0
       0    .055       0  204.12     .05       0   242.9     .08       0
Bank Sta=204.12,242.9
Exp/Cntr=0.3,0.1

Type RM Length L Ch R = 1 ,29326   ,264.21,344.76,403.02
BEGIN DESCRIPTION:
29247.88
END DESCRIPTION:
XS GIS Cut Line= 6
  889518.4460698  810695.2186133   889476.258228  810603.0315423
  889473.1334683  810523.3435105  889466.8829245  810490.5309723
  889454.3828612  810445.2193949  889462.1962969  810415.5316164
#Sta/Elev= 30
       0 1666.85    4.15 1665.17    7.05 1663.55    14.1 1661.62   21.63 1658.64
   23.03  1657.8   32.16 1653.18   36.11 1651.66   40.12 1649.06   43.96 1648.18
   47.15 1646.84   55.17 1645.54   72.73 1643.06   82.57 1642.34   94.43 1641.73
  107.08 1641.79  112.97 1641.57  127.39  1640.6  136.76 1638.41  140.07 1637.24
  156.09  1634.2  163.58 1633.32  191.43 1633.76  211.63 1634.74  218.28 1637.48
  256.29 1657.95  261.54 1659.71  265.28 1661.13  276.21 1665.65  292.24 1674.89
#Mann= 3 , 0 , 0
       0    .055       0  156.09     .05       0  191.43     .08       0
Bank Sta=156.09,191.43
Exp/Cntr=0.3,0.1

Type RM Length L Ch R = 1 ,28981   ,375.32,386.35,395.38
BEGIN DESCRIPTION:
28903.12
END DESCRIPTION:
XS GIS Cut Line= 2
  889735.6337742  810713.9692204  889854.3838638  810540.5312256
#Sta/Elev= 25
       0 1667.07     3.2 1665.08    8.71 1662.09   14.41 1659.21   18.79 1657.74
   20.74 1657.03   39.08 1646.32   45.56 1642.49   48.01  1641.5   56.42 1639.08
   56.86 1638.96   57.53 1638.89   69.02 1638.62   73.14 1637.87    76.4  1637.1
   80.87  1635.2   90.25 1632.53   92.66 1631.97   94.29  1631.8  106.25 1631.52
  135.94 1630.82  161.13 1630.47  161.951631.063  193.08 1653.56   210.2 1665.27
#Mann= 3 , 0 , 0
       0    .065       0  106.25     .05       0  161.95     .09       0
Bank Sta=106.25,161.95
Exp/Cntr=0.3,0.1

Type RM Length L Ch R = 1 ,28595   ,298.01,310.18,327.69
BEGIN DESCRIPTION:
28516.77
END DESCRIPTION:
XS GIS Cut Line= 2
  890049.6962013  810913.9692096  890196.5711773  810742.0941068
#Sta/Elev= 26
       0 1663.54   11.53    1656   15.05 1653.81   21.85 1650.41   25.25 1648.87
   30.81 1645.76   36.07 1642.86   38.47 1641.59   47.93 1637.02   56.45 1636.28
   58.91 1636.36   59.94 1636.32   66.13 1635.31   70.59 1634.67   72.32 1634.46
   74.01 1634.09    87.4 1631.21   87.82 1631.15   93.47 1630.26  112.34 1629.31
  115.53 1629.16  168.87 1627.27  172.051627.818  173.98 1628.15  194.94 1638.12
  226.08 1653.93
#Mann= 3 , 0 , 0
       0    .065       0  112.34     .05       0  172.05    .085       0
Bank Sta=112.34,172.05
Exp/Cntr=0.3,0.1

Type RM Length L Ch R = 1 ,28285   ,190.32,254.18,293.79
BEGIN DESCRIPTION:
28206.59
END DESCRIPTION:
XS GIS Cut Line= 4
   890257.508602  811120.2187184  890343.4461534  811038.9688188
  890427.8208128  810971.7818745  890462.1962431  810951.4693996
#Sta/Elev= 28
       0 1673.23    5.59  1671.2   11.19 1669.76   11.54 1669.63    11.9 1669.44
   32.57  1658.4   35.37 1655.74   38.81 1652.84   44.43 1647.91   53.44 1644.57
   53.52 1644.56   63.83 1644.24   68.94 1644.04   74.62 1643.21   75.62  1642.5
   78.67 1641.34   89.15 1636.65   94.48 1633.86   97.87 1632.85  114.38  1625.6
   131.8 1625.45  132.73 1625.45  177.18 1625.17  180.291626.214  186.29 1628.23
   222.4 1642.51  226.12 1645.37  266.05 1675.72
#Mann= 3 , 0 , 0
       0     .07       0  114.38     .05       0  180.29    .085       0
Bank Sta=114.38,180.29
Exp/Cntr=0.3,0.1

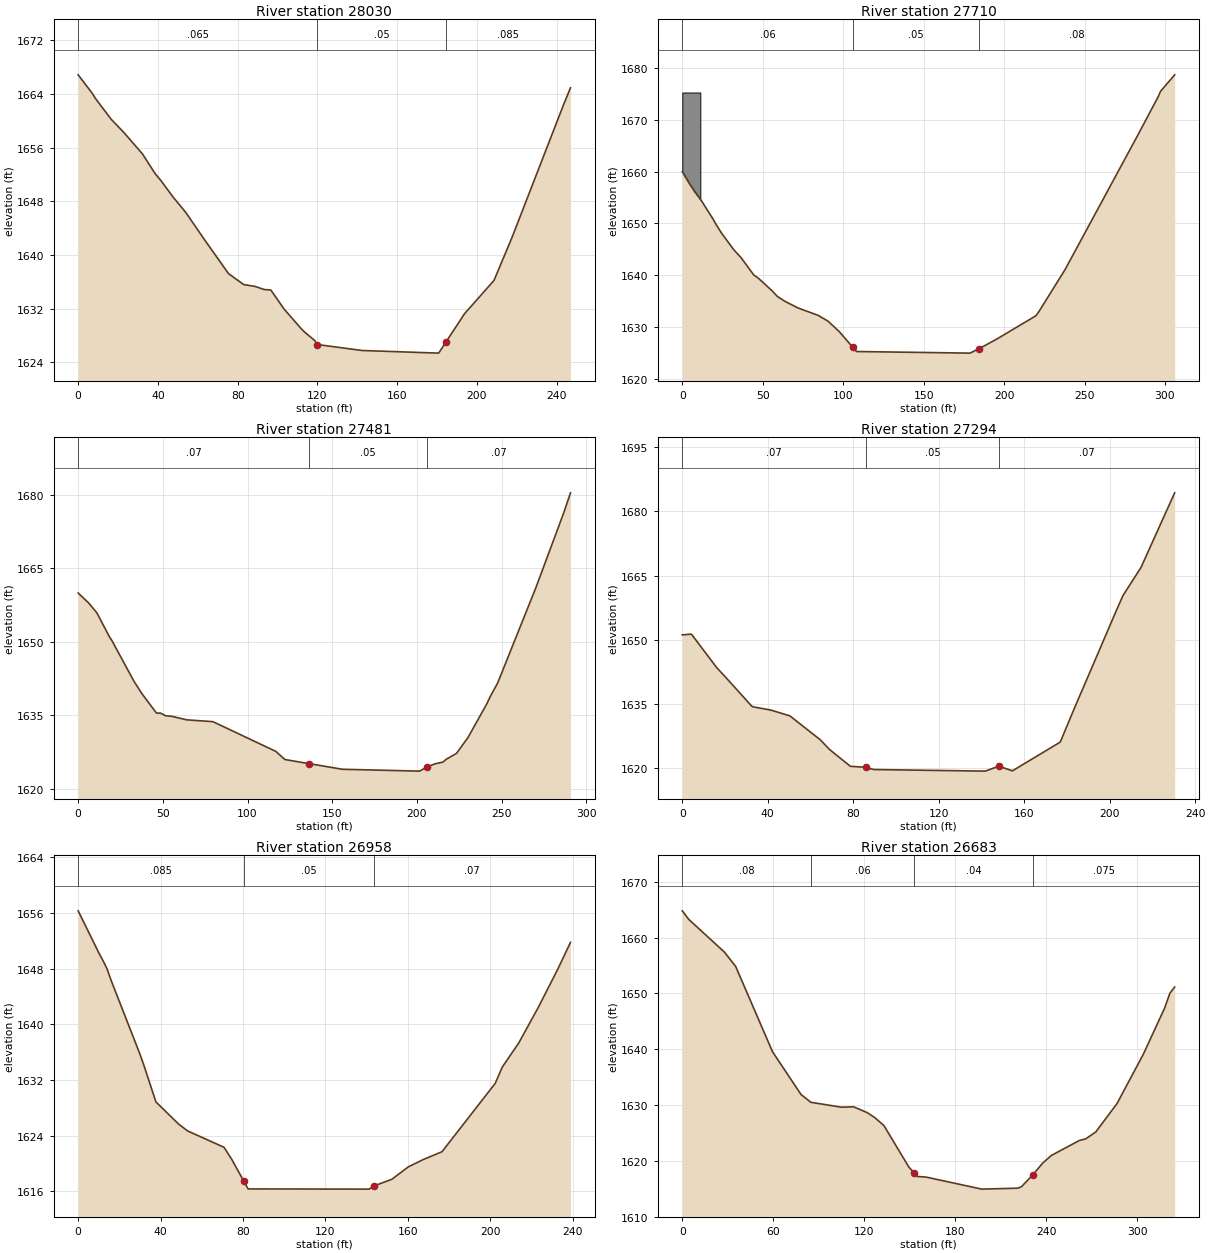
Type RM Length L Ch R = 1 ,28030   ,274.27,320.45,345.76
BEGIN DESCRIPTION:
27952.41
END DESCRIPTION:
XS GIS Cut Line= 4
  890321.5707865  811263.9689347  890398.1330344  811251.4688714
  890451.2580475  811245.2193518  890566.8833774  811237.4069402
#Sta/Elev= 29
       0 1666.84    6.99 1664.12     8.8 1663.27   16.54 1660.22   22.97 1658.23
   32.21 1655.07   38.65  1652.1   41.69 1651.01   47.64 1648.61   53.99 1646.33
   63.28 1642.31   75.42 1637.21   83.03 1635.58   88.78  1635.3   93.33 1634.84
   96.64 1634.77  103.31 1631.92  111.95 1628.98  113.58  1628.5  118.71 1627.23
  119.95 1626.64  142.51 1625.75  180.84 1625.36  184.571627.049   193.8 1631.23
  208.59  1636.2  217.69 1642.65  243.45 1662.37  246.96 1664.91
#Mann= 3 , 0 , 0
       0    .065       0  119.95     .05       0  184.57    .085       0
Bank Sta=119.95,184.57
Exp/Cntr=0.3,0.1

Type RM Length L Ch R = 1 ,27710   ,171.24,229.37,266.72
BEGIN DESCRIPTION:
27631.96
END DESCRIPTION:
XS GIS Cut Line= 4
  890279.3829448  811503.0309818  890377.8205595  811542.0940638
  890487.1963697  811578.0313618  890568.4462693  811603.0314885
#Sta/Elev= 30
       0    1660    4.65 1657.59    7.46 1656.26   12.33 1654.19   19.32 1650.75
   20.72 1649.95   24.28 1648.19   31.92 1644.95   36.62 1643.36   44.39 1640.06
   47.26 1639.43   56.08 1636.91   59.03 1635.92   63.55 1634.99      72 1633.66
   84.52 1632.23   90.57 1631.12   97.56  1629.1  105.91 1626.09  108.28 1625.25
   178.8 1624.94  184.55 1625.81  195.49 1627.66  219.75 1632.16  221.46 1632.87
  237.85 1641.05  283.08 1667.05  296.09 1674.68  297.23 1675.54  306.04 1678.74
#Mann= 3 , 0 , 0
       0     .06       0  105.91     .05       0  184.55     .08       0
#Block Obstruct= 1 ,-1
       0    11.21675.326
Bank Sta=105.91,184.55
Exp/Cntr=0.3,0.1

Type RM Length L Ch R = 1 ,27481   ,94.59,186.13,226.85
BEGIN DESCRIPTION:
27402.60
END DESCRIPTION:
XS GIS Cut Line= 3
  890188.7587658  811628.0316152  890271.5705332  811715.5310343
   890388.758755  811838.9687757
#Sta/Elev= 30
       0 1659.95    6.22 1657.91   11.12 1655.86   18.34 1651.07   20.07 1650.14
   32.99 1641.89   37.48 1639.46   46.26  1635.4   48.63 1635.41    51.5 1634.88
   55.43 1634.74    64.1 1634.03   79.57 1633.66  116.67 1627.59  122.07 1625.92
  136.19 1625.09  156.01 1623.93  201.55 1623.55  206.08 1624.42  210.55 1625.03
  215.41  1625.4  217.24 1625.96  223.37 1627.17  230.17 1630.42  241.35 1637.36
  243.33 1638.82  247.64 1641.53  270.23 1661.03  286.49 1676.16  290.68 1680.42
#Mann= 3 , 0 , 0
       0     .07       0  136.19     .05       0  206.08     .07       0
Bank Sta=136.19,206.08
Exp/Cntr=0.3,0.1

Type RM Length L Ch R = 1 ,27294   ,354.44,336.78,336.29
BEGIN DESCRIPTION:
27216.47
END DESCRIPTION:
XS GIS Cut Line= 3
  890134.0708607   811667.093673  890126.2584491  811795.2190662
   890146.570924  811895.2185487
#Sta/Elev= 24
       0 1651.13    3.94 1651.31    4.35 1651.26   16.05 1643.51    20.9 1640.89
   32.56 1634.42   33.23  1634.3    41.5 1633.54   50.36 1632.19   64.57  1626.6
   68.88 1624.34   78.66  1620.4   85.98 1620.16   89.54 1619.64   141.8 1619.27
  148.15 1620.43  154.45 1619.33  176.53 1625.96  176.98 1626.18     183  1633.4
   203.4 1657.15  206.21 1660.32  214.66 1666.91  230.41 1684.36
#Mann= 3 , 0 , 0
       0     .07       0   85.98     .05       0  148.15     .07       0
Bank Sta=85.98,148.15
Exp/Cntr=0.3,0.1

Type RM Length L Ch R = 1 ,26958   ,303.41,274.77,270.32
BEGIN DESCRIPTION:
26879.69
END DESCRIPTION:
XS GIS Cut Line= 3
    889773.13294   811667.093673  889785.6330033   811743.656945
    889810.63313  811903.0319844
#Sta/Elev= 26
       0 1656.29    9.97 1650.29   12.69 1648.77   14.02 1647.95   16.14 1646.19
   29.78 1635.87   31.73 1634.26   37.74 1628.85   48.71 1625.68   53.09 1624.69
   70.81 1622.33   74.57 1620.58   80.371617.478   82.46 1616.36  141.15 1616.33
  143.47 1616.78  152.26 1617.75  160.22 1619.53  167.41 1620.57  176.54  1621.7
  202.37 1631.52  205.84 1633.88  213.71 1637.28  223.19 1642.38  232.67 1647.88
   238.9 1651.77
#Mann= 3 , 0 , 0
       0    .085       0   80.37     .05       0  143.47     .07       0
Bank Sta=80.37,143.47
Exp/Cntr=0.5,0.3

Type RM Length L Ch R = 1 ,26683   ,83.76,99.86,77.95
BEGIN DESCRIPTION:
26604.92
END DESCRIPTION:
XS GIS Cut Line= 6
  889484.0706396  811631.1563749  889466.8829245  811695.2185594
  889487.1953994  811745.2188128  889513.7584181  811792.0943064
  889535.6337849  811882.7184853  889560.6328874  811934.2816307
#Sta/Elev= 30
       0 1664.82    4.21  1663.3   27.78 1657.42   35.19 1654.85    59.5 1639.55
    78.3 1631.88   84.78 1630.48  105.04  1629.6     113 1629.67  121.98 1628.63
  127.17 1627.69     133  1626.3  149.47 1618.84  152.92 1617.86  154.88 1617.18
  160.79 1617.07  197.53 1614.91  221.25 1615.08  223.71 1615.35  231.29 1617.51
  237.61 1619.56  243.35 1620.94   261.9 1623.64  265.91  1623.9   272.7 1625.16
  286.69 1630.25  304.03 1639.09  318.14  1647.4  321.52 1650.02  324.72 1651.15
#Mann= 4 ,-1 , 0
       0     .08       0   84.78     .06       0  152.92     .04       0
  231.29    .075       0
Bank Sta=152.92,231.29
Exp/Cntr=0.5,0.3