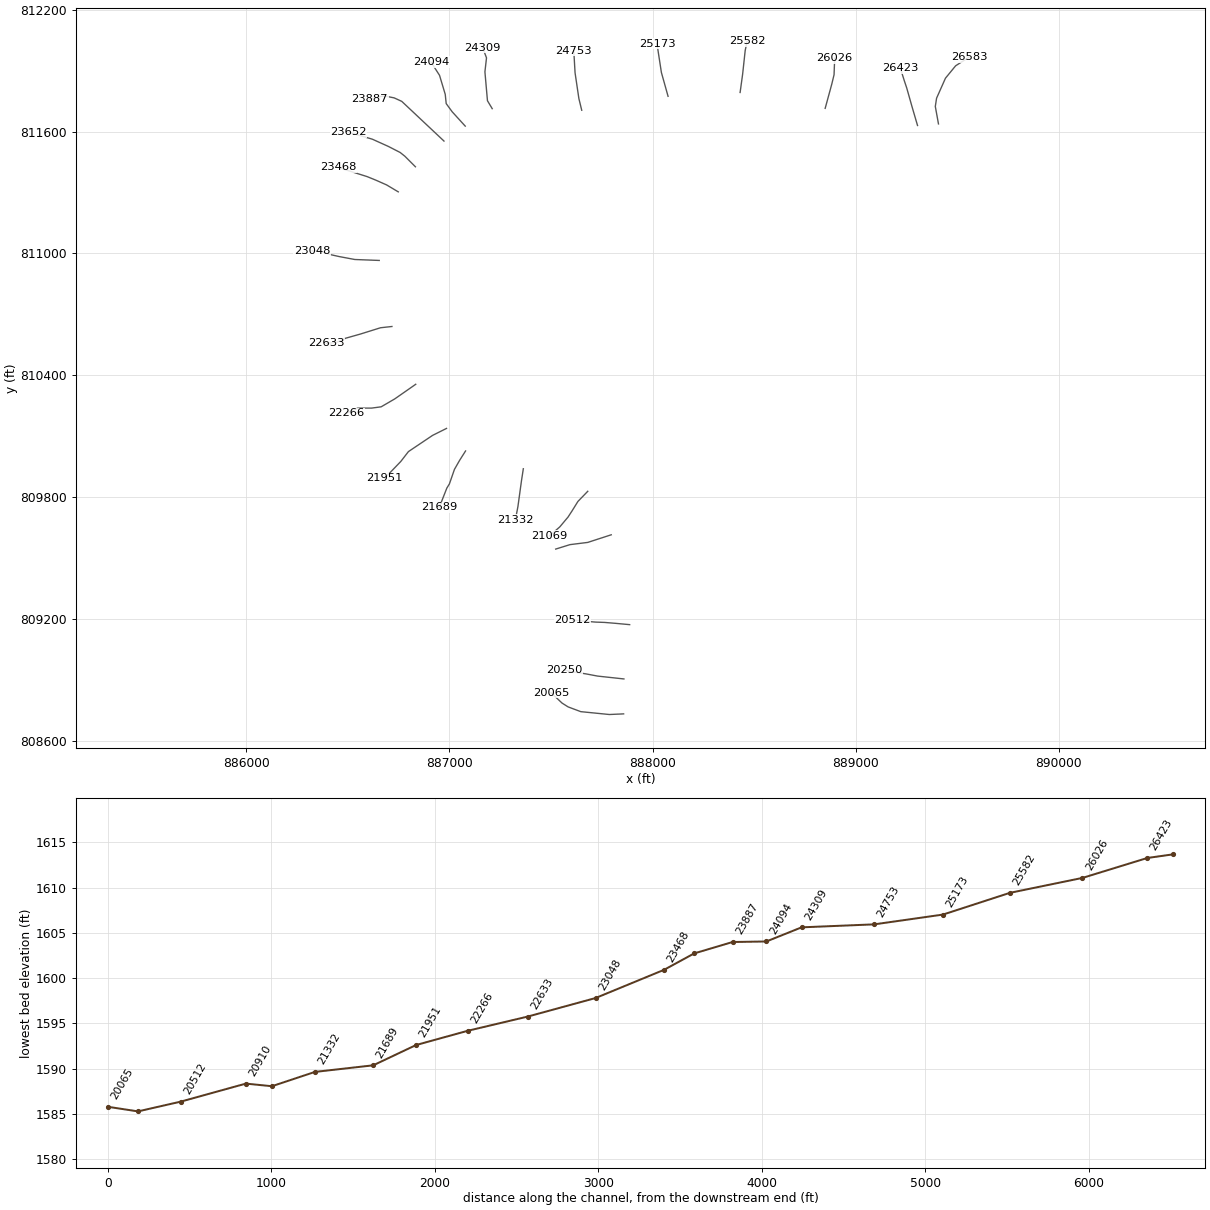
HEC-RAS study lds_big_laurel_crk.prj: lds_big_laurel_crk

--- lds_big_laurel_crk.g20 (geometry) --- (continued)

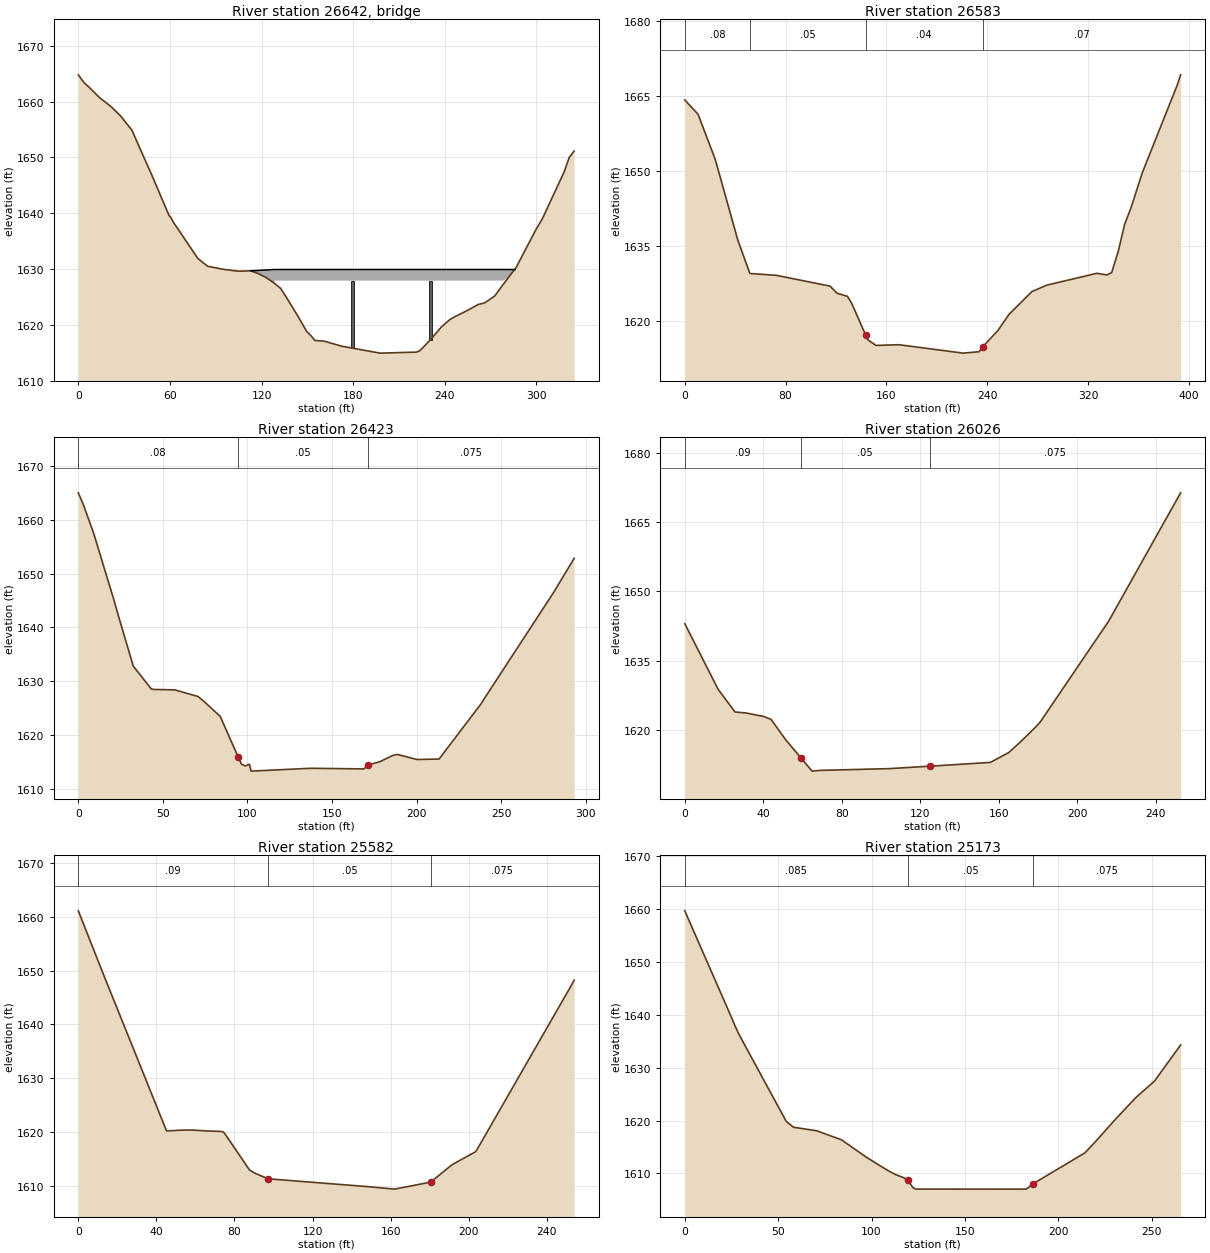
Type RM Length L Ch R = 3 ,26642   ,,,
BEGIN DESCRIPTION:
26569  FBSTR_1287  No Photo/Pier Data
END DESCRIPTION:
Bridge Culvert--1,0,-1,-1, 0
Deck Dist Width WeirC Skew NumUp NumDn MinLoCord MaxHiCord MaxSubmerge Is_Ogee
15,42,2.6,0, 5, 5, , , 0.95, 0, 0,0,,
     113   128.5     205   281.5     286
 1629.67 1629.91 1629.91 1629.91  1629.9
         1627.91 1627.91 1627.91
   63.29   123.5     200   276.5   339.5
 1629.57 1629.91 1629.91 1629.91  1629.9
         1627.91 1627.91 1627.91
Pier Skew, UpSta & Num, DnSta & Num=  ,179.5, 2 ,174.5, 2 , 0 , 0 , 0 ,,
       2       2
    1613    1628
       2       2
    1613    1628
Pier Skew, UpSta & Num, DnSta & Num=  ,230.5, 2 ,225.5, 2 , 0 , 0 , 0 ,,
       2       2
    1613    1628
       2       2
    1613    1628
BR Coef=-1 , 0 , 0 ,, 0 ,,,0.8,0,,0,
WSPro=,,,, 1 ,,,, 0 ,,,, 0 ,,,,-1 ,-1 ,-1 , 0 , 0 , 0 , 0 , 0
BR U #Sta/Elev= 61
       0 1664.82    2.61 1663.82    4.21  1663.3    7.17 1662.56   14.03  1660.7
   20.03 1659.43    22.3 1658.91   23.61 1658.54   27.78 1657.42   35.19 1654.85
   41.09 1651.16   47.76 1647.08   55.48 1642.12    59.5 1639.55   60.45 1639.31
   62.28 1638.36   66.33 1636.74    78.3 1631.88   84.78 1630.48   85.13 1630.45
   85.42 1630.44   86.38  1630.4   95.71 1629.91  105.04  1629.6     113 1629.67
  118.32 1629.11   120.3 1628.82  121.98 1628.63  127.17 1627.69  132.15 1626.61
     133  1626.3  135.38  1625.3  143.62 1621.62  149.47 1618.84  152.92 1617.86
  154.88 1617.18  160.79 1617.07   172.6 1616.15  197.53 1614.91  202.36 1614.94
  217.76 1615.07  221.25 1615.08  223.71 1615.35  225.611615.891  231.29 1617.51
  237.61 1619.56  243.35 1620.94  246.93 1621.49  251.81 1622.15  256.77 1622.85
   261.9 1623.64  265.91  1623.9  267.41 1624.15   272.7 1625.16  278.21 1627.22
  286.69 1630.25  299.58 1637.01  304.03 1639.09  318.14  1647.4  321.52 1650.02
  324.72 1651.15
BR U #Mann= 3
       0    .065   172.6     .04  225.61    .065
BR D #Sta/Elev= 82
       0 1664.27    1.73 1663.65    7.85 1662.16   10.54 1661.41   15.77    1658
   22.89 1653.22   23.76 1652.63    24.2 1652.36   25.47 1651.22   33.07 1644.59
   41.09 1637.14   42.16  1636.2   50.66 1630.41   51.68 1629.59   52.27 1629.37
   54.95 1629.41   63.29 1629.57   68.81 1629.35   72.55 1629.23   86.09 1628.62
    87.8 1628.53   91.63 1628.34   98.93  1628.1  104.08 1627.71  107.52 1627.44
  112.26 1627.26  113.52 1627.19  115.28 1627.07  120.83 1625.65  128.91 1625.03
  129.11 1625.03   132.5 1623.62  143.461617.342  145.14 1616.38  149.21 1615.76
  151.71 1615.22  169.98 1615.36  194.17 1614.55  196.32 1614.47  202.42 1614.17
  212.42 1613.89  220.88 1613.68  220.97 1613.68  227.43 1614.02   233.6 1613.96
  236.63 1614.99  244.42  1617.4   248.4 1618.17   257.4 1621.44  266.44 1623.85
  275.51 1625.98  275.69    1626  279.96 1626.41  284.79 1626.95  287.28 1627.26
  294.15 1627.52  296.71 1627.61  300.05 1627.86  303.69 1628.11  308.27 1628.34
  314.12 1628.58  314.21 1628.59   314.5  1628.6  315.53 1628.67  323.95 1629.35
  327.01 1629.63  330.69 1629.54  335.14  1629.3  338.82 1629.78  340.72 1631.06
  344.01 1633.99  349.14 1639.45  354.22 1642.76  357.01 1644.94   363.1 1649.71
  368.24 1653.16  374.84 1657.18  375.85 1658.09  376.99 1658.94  379.85 1660.81
   390.8  1667.2  393.54 1669.29
BR D #Mann= 3
       0    .065  143.46     .04  236.63    .065
BC Design=,, 0 ,, 0 ,,,,,,

Type RM Length L Ch R = 1 ,26583   ,107.86,160.29,225.39
BEGIN DESCRIPTION:
26505.06
END DESCRIPTION:
XS GIS Cut Line= 6
  889407.5083918  811637.4069187  889391.8835686  811723.3444701
  889398.1330882  811763.9694199   889441.883822  811862.4060104
  889491.8830512  811923.3444593  889557.5081277  811965.5312769
#Sta/Elev= 30
       0 1664.27   10.54 1661.41    24.2 1652.36   42.16  1636.2   51.68 1629.59
   72.55 1629.23  115.28 1627.07  120.83 1625.65  129.11 1625.03   132.5 1623.62
  143.461617.342  145.14 1616.38  151.71 1615.22  169.98 1615.36  220.88 1613.68
   233.6 1613.96  236.63 1614.99   248.4 1618.17   257.4 1621.44  275.51 1625.98
  287.28 1627.26  327.01 1629.63  335.14  1629.3  338.82 1629.78  344.01 1633.99
  349.14 1639.45  354.22 1642.76   363.1 1649.71   390.8  1667.2  393.54 1669.29
#Mann= 4 ,-1 , 0
       0     .08       0   51.68     .05       0  143.46     .04       0
  236.63     .07       0
Bank Sta=143.46,236.63
Exp/Cntr=0.5,0.3

Type RM Length L Ch R = 1 ,26423   ,433.54,396.29,342.77
BEGIN DESCRIPTION:
26344.76
END DESCRIPTION:
XS GIS Cut Line= 6
  889304.3831253   811629.593483  889277.8211308  811720.2186861
  889251.2581121  811813.9686491  889240.3209408  811846.7811873
  889229.3837694  811881.1566175  889221.5713579   811910.844396
#Sta/Elev= 29
       0 1665.03    2.98 1662.83    9.09 1657.49   21.14 1645.01   23.36 1642.52
   32.49  1632.8   43.17 1628.55   44.66 1628.46   57.11 1628.38   70.78 1627.15
   74.19 1626.27   83.93 1623.45   94.44 1615.97   96.47 1614.58   98.68 1614.24
   101.2 1614.55  102.17 1613.27  137.28  1613.8  169.01 1613.68  171.06 1614.38
  178.31 1615.02   186.1 1616.21  188.74 1616.37  200.32 1615.43  213.36 1615.52
  238.37 1625.87  240.15 1626.78  281.17 1646.54  293.24 1652.85
#Mann= 3 , 0 , 0
       0     .08       0   94.44     .05       0  171.06    .075       0
Bank Sta=94.44,171.06
Exp/Cntr=0.3,0.1

Type RM Length L Ch R = 1 ,26026   ,431.28,443.95,450.99
BEGIN DESCRIPTION:
25948.48
END DESCRIPTION:
XS GIS Cut Line= 4
  888849.6962659  811713.9691665  888882.5088041   811834.281124
  888893.4459755  811879.5937256  888896.5707352  811960.8436252
#Sta/Elev= 23
       0 1642.98   16.94 1628.81   25.57 1623.88   31.36 1623.65   33.16 1623.49
   40.17  1622.9   43.93 1622.28   51.44 1617.84   59.131613.958   64.85 1611.07
   68.85 1611.23  104.17 1611.61  119.29    1612  124.71 1612.13   155.7 1612.96
  165.12  1615.1  171.31 1617.52  178.88 1620.66  181.22 1621.78  207.72 1638.38
  215.84 1643.44  244.46 1665.13  252.63 1671.31
#Mann= 3 , 0 , 0
       0     .09       0   59.13     .05       0  124.71    .075       0
Bank Sta=59.13,124.71
Exp/Cntr=0.3,0.1

Type RM Length L Ch R = 1 ,25582   ,376.69,409.02,432.49
BEGIN DESCRIPTION:
25504.53
END DESCRIPTION:
XS GIS Cut Line= 4
  888430.9456803  811792.0943064  888443.4457436  811882.7184853
   888455.945807  811998.3438152  888465.3211105  812043.6564168
#Sta/Elev= 23
       0 1661.11   12.43  1649.7   45.18 1620.25   48.31 1620.28   51.22 1620.35
   55.84  1620.4    58.7 1620.39   65.46 1620.23   73.61 1620.13   74.54 1619.95
    75.5 1619.49   87.79 1612.94   90.75 1612.33   91.48 1612.22   97.23 1611.34
  148.45 1609.88  162.06 1609.42  180.52 1610.72  191.45 1613.95  203.65 1616.39
  207.78 1618.97  251.73 1646.71  254.05 1648.23
#Mann= 3 , 0 , 0
       0     .09       0   97.23     .05       0  180.52    .075       0
Bank Sta=97.23,180.52
Exp/Cntr=0.3,0.1

Type RM Length L Ch R = 1 ,25173   ,429.82,420.51,414.72
BEGIN DESCRIPTION:
25095.50
END DESCRIPTION:
XS GIS Cut Line= 3
  888076.2583034  811773.3436993  888043.4457652  811890.5319211
  888021.5703983  812032.7192454
#Sta/Elev= 26
       0 1659.69   25.04 1639.49   26.82 1637.98   29.03  1636.3   54.38 1619.81
   58.25 1618.73    70.7 1618.06   83.88 1616.36   97.11  1613.1  104.13 1611.54
  109.71 1610.36  113.01 1609.76  117.38 1609.16  119.36  1608.7  122.23  1607.3
  123.65 1607.03  179.46 1607.02  182.83 1607.03  186.59 1607.97  189.17 1608.59
  214.24 1613.87  219.44 1615.81  230.81  1620.3  241.72  1624.4  251.53 1627.45
  265.56 1634.31
#Mann= 3 , 0 , 0
       0    .085       0  119.36     .05       0  186.59    .075       0
Bank Sta=119.36,186.59
Exp/Cntr=0.3,0.1

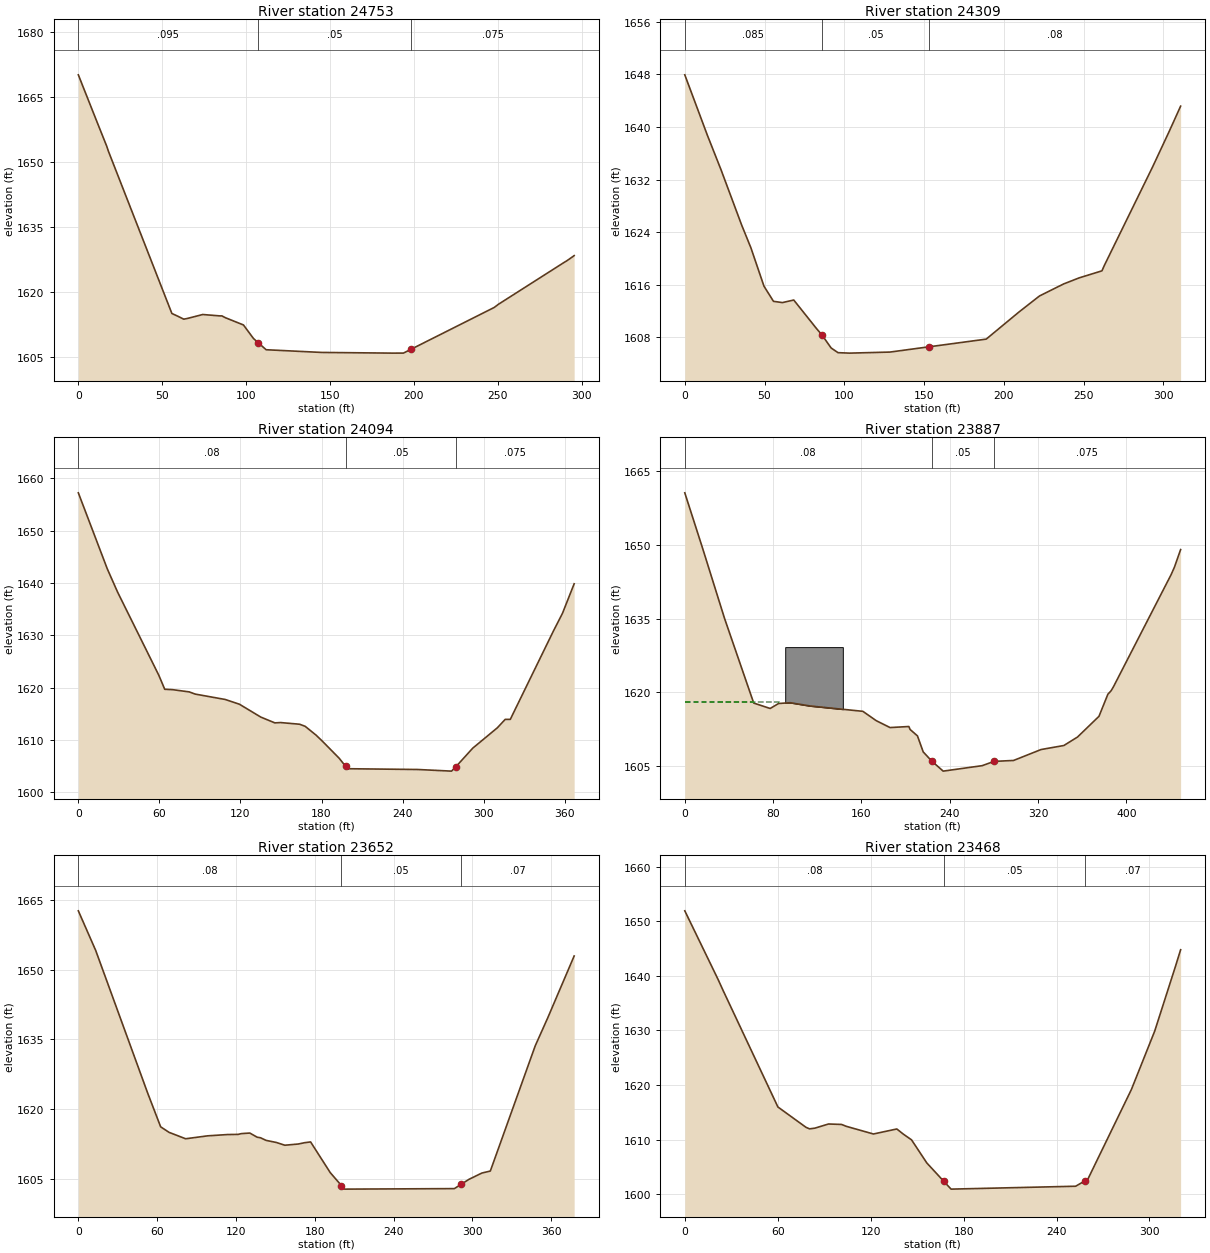
Type RM Length L Ch R = 1 ,24753   ,452.4,444.3,433.74
BEGIN DESCRIPTION:
24675.00
END DESCRIPTION:
XS GIS Cut Line= 4
  887651.2581983   811704.593863  887637.1962671  811762.4065279
    887618.44566  811888.9690291  887612.1961405  811996.7819474
#Sta/Elev= 29
       0 1670.15   10.89 1659.52    16.9  1653.7   17.51    1653   18.02 1652.43
   55.74 1615.09    59.5 1614.41   62.83 1613.77    63.2 1613.81    64.8 1613.92
   74.12 1614.85   84.31 1614.53   85.55 1614.53   87.63 1614.11   98.39 1612.44
  104.38 1609.31  107.111608.371  111.91 1606.72  144.95  1606.1  187.32 1605.94
  187.44 1605.94  193.73 1605.95  198.221606.824  247.77 1616.47  250.28  1617.2
  289.87 1626.97  290.83 1627.18  294.28 1628.11  295.44 1628.44
#Mann= 3 , 0 , 0
       0    .095       0  107.11     .05       0  198.22    .075       0
Bank Sta=107.11,198.22
Exp/Cntr=0.3,0.1

Type RM Length L Ch R = 1 ,24309   ,186.11,215.13,253.85
BEGIN DESCRIPTION:
24230.70
END DESCRIPTION:
XS GIS Cut Line= 5
    887210.63327  811712.4062746  887187.1960353  811751.4693566
   887174.695972  811893.6566809  887182.5083835  811962.4065171
  887163.7588006  812012.4067705
#Sta/Elev= 26
       0 1647.95   14.14 1638.77   22.81 1633.45   35.61 1625.12   41.47 1621.62
   49.64  1615.8    55.6 1613.49   61.23  1613.3   68.32 1613.69   82.41  1609.4
   85.94 1608.39   91.77 1606.39   96.07 1605.68  103.38 1605.61  128.63 1605.77
  153.08 1606.57  188.98 1607.74   209.5 1611.86  222.41 1614.31  237.58 1616.14
  247.28 1617.06  261.57 1618.13  262.97 1618.91  293.17 1633.87  303.45  1639.2
  310.88 1643.18
#Mann= 3 , 0 , 0
       0    .085       0   85.94     .05       0  153.08     .08       0
Bank Sta=85.94,153.08
Exp/Cntr=0.3,0.1

Type RM Length L Ch R = 1 ,24094   ,136.6,206.59,296.31
BEGIN DESCRIPTION:
24015.57
END DESCRIPTION:
XS GIS Cut Line= 6
  887077.8212492  811626.4687232  887013.7580406  811696.7814514
  886984.0712863  811737.4064012  886979.3836345  811782.7190028
  886951.2587481  811876.4689658  886909.0709063  811942.0940422
#Sta/Elev= 30
       0 1657.23   21.36 1642.75   28.98  1638.3    59.6 1622.35   63.94 1619.69
    69.7 1619.62   82.09 1619.19    86.5 1618.77  108.73 1617.74  119.25 1616.83
  135.01 1614.38  145.44 1613.27  149.67 1613.33  163.78 1613.01  167.89 1612.61
  176.02 1610.91  180.65 1609.76  193.05 1606.51  197.741604.987  199.21 1604.51
  251.25 1604.36  276.21 1604.05  279.161604.816  291.86 1608.43   310.1 1612.33
  315.92 1613.94  319.68 1613.94  351.66 1630.86  358.29  1634.2  366.94 1639.85
#Mann= 3 , 0 , 0
       0     .08       0  197.74     .05       0  279.16    .075       0
Bank Sta=197.74,279.16
Exp/Cntr=0.3,0.1

Type RM Length L Ch R = 1 ,23887   ,188.12,235.01,229.63
BEGIN DESCRIPTION:
23808.98
END DESCRIPTION:
XS GIS Cut Line= 6
  886973.1330908  811553.0312351    886765.32069  811748.3435726
     886727.8205  811765.5312877  886688.7584421  811773.3436993
  886666.8830753  811773.3436993  886607.5085425  811759.2817681
#Sta/Elev= 30
       0 1660.58   15.83 1649.52   36.09 1634.99   62.44 1617.83   77.33 1616.73
      85 1617.74   95.47  1617.9  113.37 1617.24  161.32 1616.15  173.36 1614.26
  185.95 1612.85     203 1613.06  204.11 1612.46  210.78 1611.16  215.99  1607.9
  223.79 1606.02  234.08 1603.99  269.41  1605.1  280.12 1605.97  297.88 1606.16
  322.75 1608.38  343.44  1609.2  355.83 1610.93  375.25 1615.14  383.29 1619.62
  386.21 1620.33  388.18 1621.07  440.62 1643.96  443.52 1645.42   449.2 1649.04
#Mann= 3 , 0 , 0
       0     .08       0  223.79     .05       0  280.12    .075       0
#XS Ineff= 2 , 0
       0      85    1618               0
Permanent Ineff=
       F       F
#Block Obstruct= 1 ,-1
   90.97  143.171629.205
Bank Sta=223.79,280.12
Exp/Cntr=0.3,0.1

Type RM Length L Ch R = 1 ,23652   ,173.81,184.05,182.35
BEGIN DESCRIPTION:
23573.98
END DESCRIPTION:
XS GIS Cut Line= 6
  886832.5086584  811426.4687339  886780.9455131  811478.0318793
  886757.5082784  811496.7814622  886699.6956135  811526.4692406
  886620.0086059  811562.4065387   886502.820384  811596.7819689
#Sta/Elev= 30
       0 1662.63   13.24 1654.09   52.81 1623.39   62.66 1616.15   69.06 1614.95
   81.69 1613.57   98.44  1614.2  113.81 1614.48  121.62 1614.51  124.12 1614.68
  130.54  1614.8  136.14 1613.91  138.71 1613.78  142.96 1613.22   150.8 1612.77
  157.22 1612.18  167.48 1612.44  172.21 1612.72  176.83 1612.89   191.8 1606.28
  200.32 1603.49   202.7 1602.73  286.29 1602.84  291.41 1603.76  297.43 1604.84
  307.21 1606.19  313.66 1606.62  347.81 1633.55  357.41 1639.62  377.48 1652.91
#Mann= 3 , 0 , 0
       0     .08       0  200.32     .05       0  291.41     .07       0
Bank Sta=200.32,291.41
Exp/Cntr=0.3,0.1

Type RM Length L Ch R = 1 ,23468   ,385.2,419.37,424
BEGIN DESCRIPTION:
23389.93
END DESCRIPTION:
XS GIS Cut Line= 6
  886748.1329749  811303.0309925  886690.3213341  811337.4064228
   886637.196321  811360.8436575  886595.0084792  811378.0313726
  886476.2583896  811415.5315626  886452.8211549  811423.3439742
#Sta/Elev= 24
       0  1651.9   21.51 1639.32   24.65 1637.36   60.11 1615.97   78.21 1612.25
   80.55 1611.96   83.98 1612.09   92.77 1612.85  101.22 1612.77   104.2 1612.43
  121.77 1611.02  136.88 1611.94  141.21 1610.97  146.38 1609.95  156.25 1605.72
  167.311602.318  171.93 1600.92  252.34 1601.45   258.7 1602.49  260.45 1602.87
  288.34 1619.17   303.4 1629.88  316.84 1641.77  320.12 1644.77
#Mann= 3 , 0 , 0
       0     .08       0  167.31     .05       0   258.7     .07       0
Bank Sta=167.31,258.7
Exp/Cntr=0.3,0.1

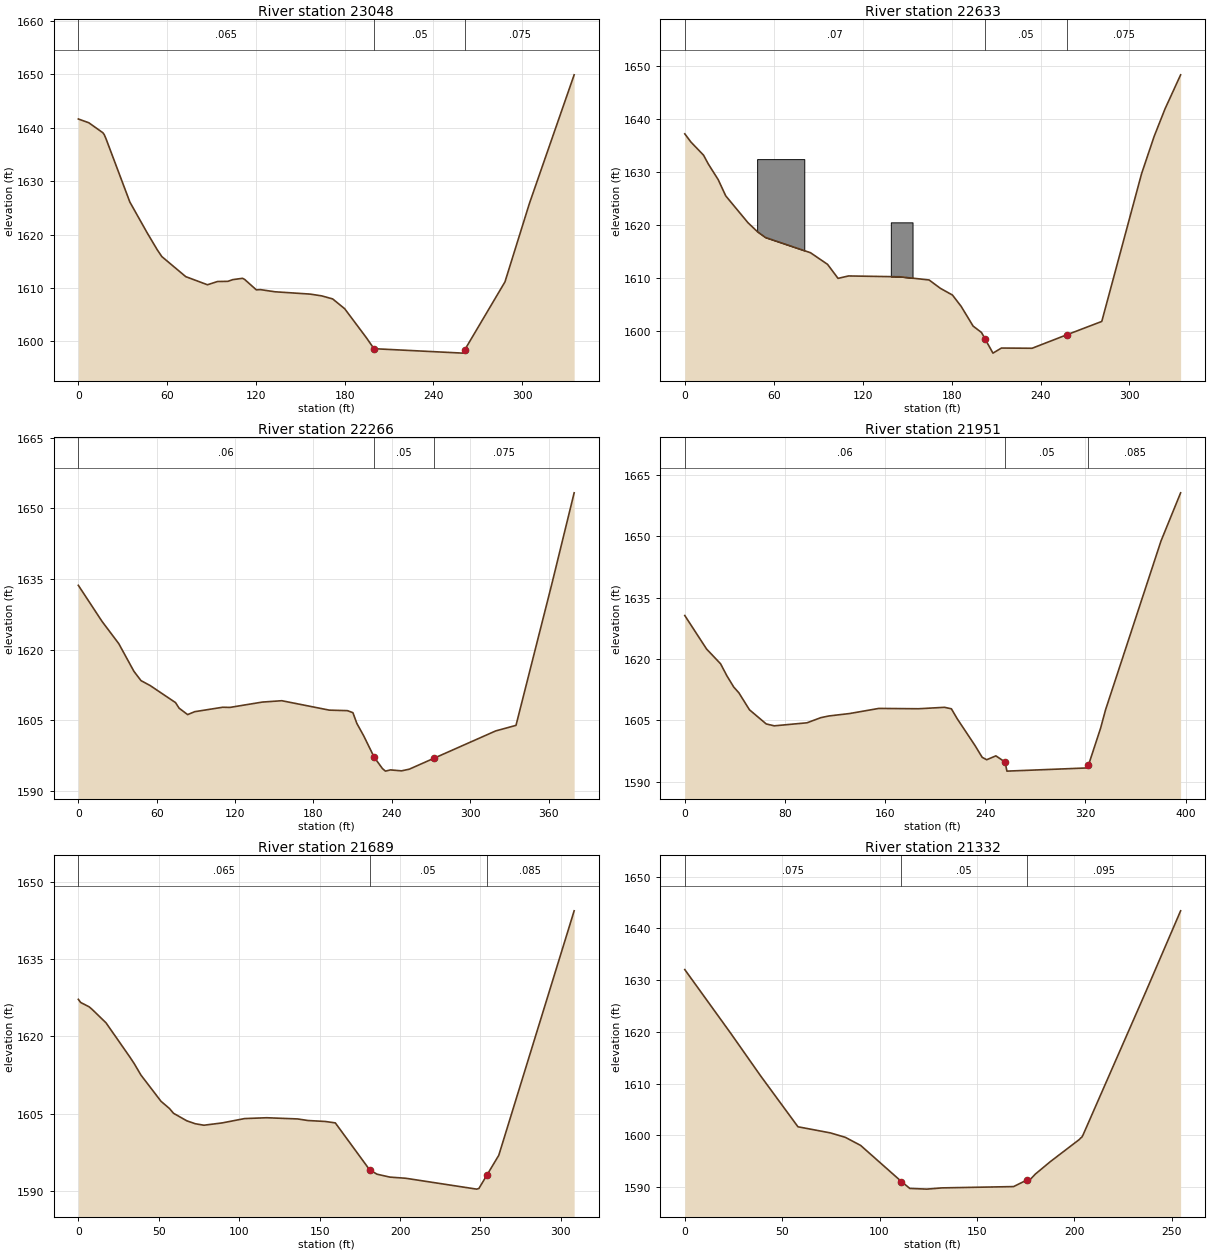
Type RM Length L Ch R = 1 ,23048   ,348.09,415.62,461.5
BEGIN DESCRIPTION:
22970.56
END DESCRIPTION:
XS GIS Cut Line= 6
  886654.3830119  810965.5313308  886534.0710545  810970.2189825
  886459.0706745  810984.2819379  886416.8838568  810993.6562172
  886360.6330597  811012.4068243  886324.6957617  811012.4068243
#Sta/Elev= 30
       0 1641.64    7.06 1640.94   16.56 1639.07   17.47 1638.74   18.72 1637.94
   34.83 1626.09    46.4 1620.39   53.28 1617.18   56.47 1615.87   72.62 1612.12
   87.28  1610.6   94.09 1611.21  101.08 1611.24  104.38 1611.56  110.99 1611.81
  112.45 1611.59  120.33 1609.65  123.16 1609.69  132.83 1609.29  156.79 1608.85
  164.52 1608.52  171.92 1607.95  180.03 1606.12  194.73 1600.68  199.85 1598.63
  259.89  1597.8  261.231598.427   288.4 1611.14  304.93 1625.83  335.17 1649.91
#Mann= 3 , 0 , 0
       0    .065       0  199.85     .05       0  261.23    .075       0
Bank Sta=199.85,261.23
Exp/Cntr=0.3,0.1

Type RM Length L Ch R = 1 ,22633   ,337.07,366.68,352.95
BEGIN DESCRIPTION:
22554.93
END DESCRIPTION:
XS GIS Cut Line= 6
  886716.8833286  810640.5317323  886660.6335557  810634.2811886
   886560.633049  810603.0315423  886488.7584529  810582.7190674
  886445.0087433  810562.4065925    886395.00849  810557.7189407
#Sta/Elev= 30
       0  1637.2    4.15 1635.65   12.65 1633.17   15.89 1631.49   22.49 1628.57
   27.65 1625.47   42.63  1620.4    49.1 1618.68    54.4 1617.61   84.81 1614.73
   96.32 1612.53  103.39 1609.88  110.47 1610.34  145.31 1610.18   164.8 1609.58
  172.49 1607.99  180.58 1606.73  186.44 1604.59  194.52 1600.86  200.19 1599.65
  202.49 1598.47  207.91 1595.75  213.61 1596.71  234.31 1596.67  257.57  1599.2
  281.32 1601.74  308.16 1629.66  316.59 1636.68  323.98 1641.92  334.51 1648.36
#Mann= 3 , 0 , 0
       0     .07       0  202.49     .05       0  257.57    .075       0
#Block Obstruct= 2 ,-1
    48.8   80.611632.423  138.99  153.641620.472
Bank Sta=202.49,257.57
Exp/Cntr=0.3,0.1

Type RM Length L Ch R = 1 ,22266   ,255.49,315.34,359.57
BEGIN DESCRIPTION:
22188.26
END DESCRIPTION:
XS GIS Cut Line= 6
  886834.0705262  810356.1560595  886730.9462839  810284.2814635
  886663.7583155  810245.2194056  886616.8838461  810238.9688619
  886548.1329856  810238.9688619  886493.4461047  810213.9687352
#Sta/Elev= 30
       0 1633.63   18.18 1625.96   30.98 1621.24   42.54 1615.38   47.97  1613.4
   55.05 1612.34   74.41 1608.73   77.14 1607.55   83.67 1606.18   89.08  1606.8
  110.43 1607.74  116.11 1607.71  140.82 1608.84  155.79 1609.13  192.14 1607.13
  206.04 1607.02  210.21 1606.59  213.24  1604.3  218.45 1601.69  226.51 1597.13
  232.82 1594.72  235.12 1594.18  238.95 1594.44  247.45 1594.24  253.33 1594.59
  272.59 1596.95  319.46 1602.71  335.07  1603.9  362.59 1634.02  379.59 1653.27
#Mann= 3 , 0 , 0
       0     .06       0  226.51     .05       0  272.59    .075       0
Bank Sta=226.51,272.59
Exp/Cntr=0.3,0.1

Type RM Length L Ch R = 1 ,21951   ,179.06,261.91,293.33
BEGIN DESCRIPTION:
21872.91
END DESCRIPTION:
XS GIS Cut Line= 5
  886985.6331541  810138.9693794  886916.8833178  810104.5939491
  886798.1332282  810024.9069415  886760.6330382   809976.468556
  886680.9460306  809893.6567886
#Sta/Elev= 30
       0  1630.6    17.4 1622.42    28.6 1618.81   33.65 1615.87   39.14 1613.12
    43.2 1611.73   51.67 1607.58   65.05 1604.13   71.46 1603.67   97.63 1604.41
  108.71 1605.67  115.13 1606.08  131.58 1606.67     155 1607.92  186.58 1607.84
  207.43 1608.19  212.95 1607.83  217.66 1605.37  231.72 1598.91  237.56 1595.98
  241.15 1595.39   248.5 1596.34   255.91594.808  257.29 1592.61  321.71 1593.39
  322.461594.077  332.17 1603.13  336.06 1607.55  380.36 1648.78  396.06 1660.56
#Mann= 3 , 0 , 0
       0     .06       0   255.9     .05       0  322.46    .085       0
Bank Sta=255.9,322.46
Exp/Cntr=0.3,0.1

Type RM Length L Ch R = 1 ,21689   ,326.14,356.73,375.04
BEGIN DESCRIPTION:
21611.00
END DESCRIPTION:
XS GIS Cut Line= 6
  887079.3831171  810028.0317013  887049.6963628  809981.1562077
  887024.6962361  809937.4064981  886999.6961094  809865.5319021
  886987.1960461  809845.2194272  886949.6958561  809749.9065723
#Sta/Elev= 30
       0 1627.17    1.46 1626.56    6.71 1625.72    8.49 1625.25   17.22 1622.61
   32.04 1615.98   34.72 1614.72   38.92 1612.49   51.43 1607.39   56.66    1606
   59.16 1605.08   67.41 1603.62   72.68 1603.05   78.07 1602.76   89.48 1603.21
  103.34 1604.05  117.15 1604.21  136.28 1603.98  142.82 1603.67  153.49 1603.49
  159.77 1603.21  181.21 1594.07  185.75 1593.26  193.69  1592.7  203.47 1592.48
  247.61 1590.37  249.01 1590.49  253.881593.023  261.39 1596.93  308.25 1644.33
#Mann= 3 , 0 , 0
       0    .065       0  181.21     .05       0  253.88    .085       0
Bank Sta=181.21,253.88
Exp/Cntr=0.3,0.1

Type RM Length L Ch R = 1 ,21332   ,296.92,263.06,226.15
BEGIN DESCRIPTION:
21254.27
END DESCRIPTION:
XS GIS Cut Line= 4
  887363.7587899  809940.5312579  887354.3834863  809879.5938332
  887337.1957712   809754.594224  887324.6957079  809688.9691475
#Sta/Elev= 22
       0 1632.04   23.72 1619.67   38.81 1611.58   58.12 1601.68   74.77  1600.5
   82.48 1599.64   90.31 1598.08  111.25 1591.11  115.53 1589.78   124.3 1589.64
  132.18 1589.88  168.86 1590.13  175.57 1591.38  176.68 1591.22   180.1 1592.57
  187.83 1594.98   202.6 1599.22  203.38 1599.54  203.85 1599.64  204.56 1600.13
  236.67 1627.68  254.64 1643.39
#Mann= 3 , 0 , 0
       0    .075       0  111.25     .05       0  175.57    .095       0
Bank Sta=111.25,175.57
Exp/Cntr=0.3,0.1

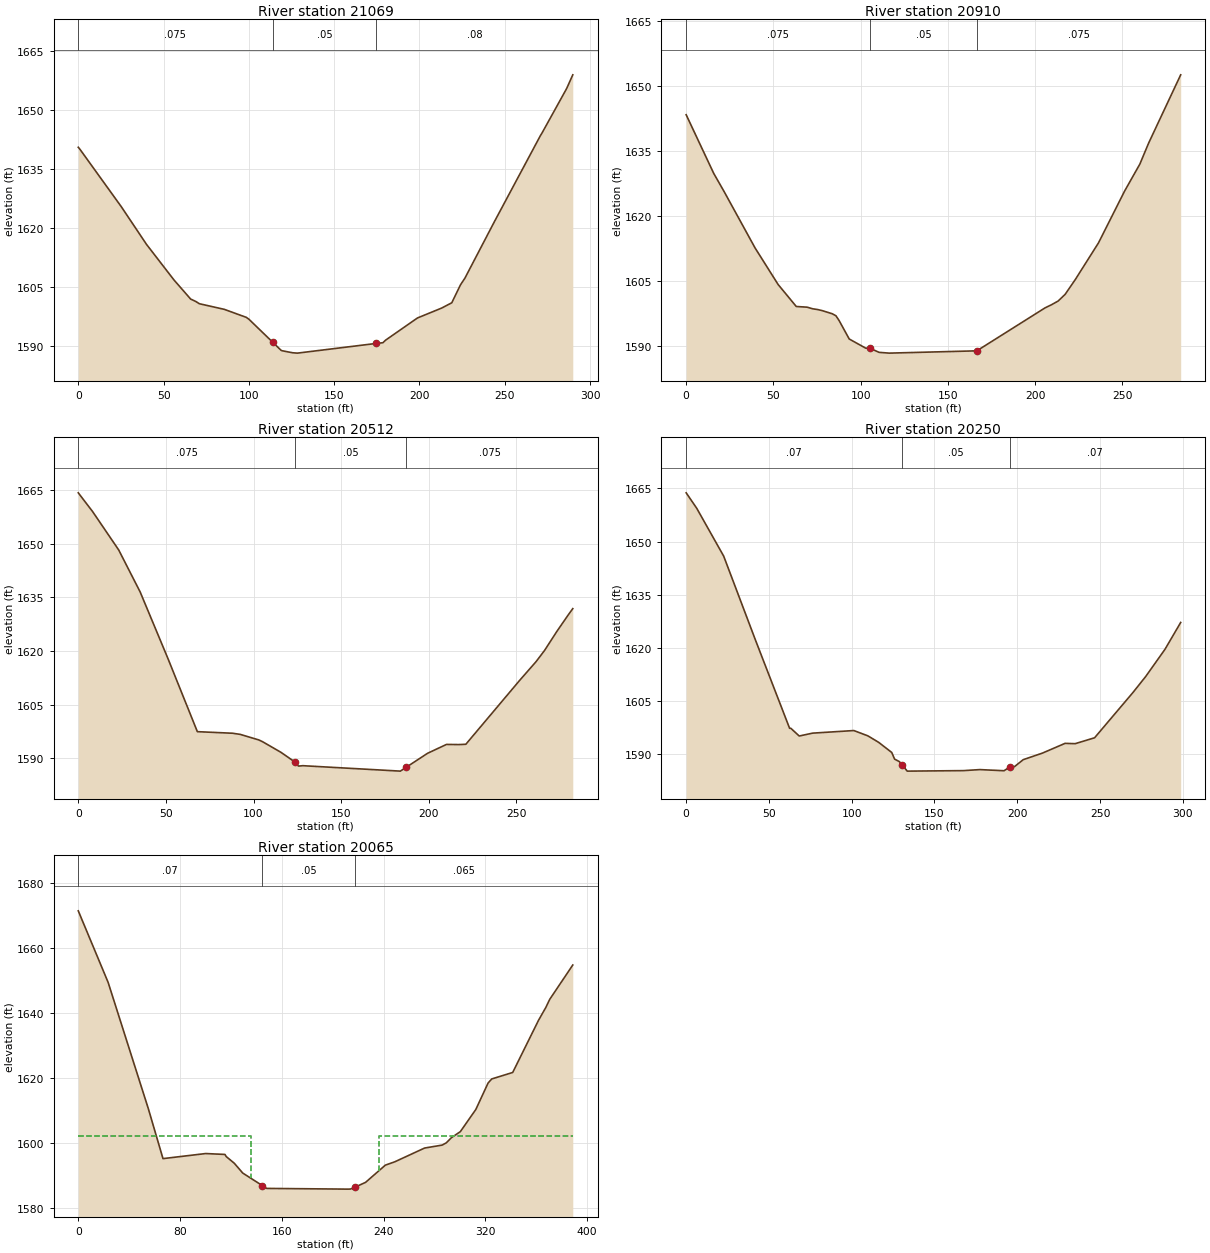
Type RM Length L Ch R = 1 ,21069   ,218.2,159.01,98.68
BEGIN DESCRIPTION:
20991.21
END DESCRIPTION:
XS GIS Cut Line= 6
  887680.9459767  809829.5935799  887632.5086154  809779.5943507
  887604.3837289  809734.2817491   887584.071254  809703.0310787
  887543.4463042  809654.5937173  887493.4460508  809610.8440077
#Sta/Elev= 30
       0 1640.56     .99 1640.04   25.27 1625.37   39.99  1615.8   56.21 1606.66
   65.85 1601.86   68.97 1601.21   70.98 1600.66   85.62 1599.22   98.51 1597.18
  100.09 1596.68  113.891590.878  118.81 1588.81  119.36 1588.68  125.67 1588.15
  128.45 1588.06  174.63 1590.53  178.57 1590.71  180.13 1591.36   198.8 1597.02
  213.06 1599.56  218.94  1600.9  224.04 1605.47  226.63 1607.17  243.91 1621.57
  270.91 1643.54  271.72  1644.1  285.94 1655.27  286.45  1655.7  289.87 1659.03
#Mann= 3 , 0 , 0
       0    .075       0  113.89     .05       0  174.63     .08       0
Bank Sta=113.89,174.63
Exp/Cntr=0.3,0.1

Type RM Length L Ch R = 1 ,20910   ,431.77,398.1,378.54
BEGIN DESCRIPTION:
20832.20
END DESCRIPTION:
XS GIS Cut Line= 4
  887796.5713066  809615.5316595  887680.9459767  809578.0314695
  887593.4455334  809567.0942981  887523.1338293  809545.2189312
#Sta/Elev= 29
       0  1643.4   15.81 1629.84   21.85 1625.58   39.47 1612.65    52.7 1604.19
   63.09 1599.12   69.34 1598.96   72.58 1598.58   75.28 1598.42   77.92 1598.17
   83.72 1597.44   85.84 1596.97   87.68 1595.84   93.44 1591.61  102.87  1589.5
  105.42 1589.45  110.56 1588.53  116.33 1588.35  166.56 1588.88  205.69 1598.81
  209.13 1599.48  213.12 1600.37  217.17 1601.93  223.04 1605.38   236.3 1613.83
   251.2 1625.75  259.99 1632.02  265.01 1636.86  283.37 1652.62
#Mann= 3 , 0 , 0
       0    .075       0  105.42     .05       0  166.56    .075       0
Bank Sta=105.42,166.56
Exp/Cntr=0.3,0.1

Type RM Length L Ch R = 1 ,20512   ,268.14,261.72,252.84
BEGIN DESCRIPTION:
20434.10
END DESCRIPTION:
XS GIS Cut Line= 6
  887887.1954855  809173.3438393  887820.0085413   809179.594383
  887763.7587683  809184.2810106  887720.0080346  809185.8439026
  887663.7582616  809190.5315544  887605.9455967  809195.2192061
#Sta/Elev= 26
       0 1664.22    8.13 1659.01   23.07 1648.24   35.31 1636.49   51.21 1617.81
   67.95  1597.4   88.03 1596.96   92.41 1596.64  103.01 1595.09  105.24 1594.57
  115.62 1591.63  123.57 1588.92  125.64 1587.77  128.15 1587.88  183.77 1586.36
  187.081587.424   199.3 1591.35  210.09 1593.83  217.15 1593.79  221.13 1593.87
  251.79 1611.72  261.22    1617  266.07 1620.14  273.07 1625.45  279.58 1630.08
  282.15 1631.82
#Mann= 3 , 0 , 0
       0    .075       0  123.57     .05       0  187.08    .075       0
Bank Sta=123.57,187.08
Exp/Cntr=0.3,0.1

Type RM Length L Ch R = 1 ,20250   ,181.21,184.99,170.38
BEGIN DESCRIPTION:
20172.38
END DESCRIPTION:
XS GIS Cut Line= 5
  887859.0705991  808906.1569057  887729.3833381  808920.2188369
  887671.5706732  808931.1560082  887610.6332485  808940.5313118
  887563.7587791  808949.9066153
#Sta/Elev= 30
       0 1663.74    6.36  1659.4   22.66  1645.9   41.94 1622.13   62.48 1597.36
   63.22 1597.36   68.29 1595.18   76.39 1595.99  101.28 1596.72  109.78 1595.22
  116.24 1593.41  124.19 1590.54  125.92 1588.66  128.79 1587.96  130.45 1587.03
  133.56 1585.28  167.41 1585.42  177.41 1585.71  192.04 1585.39  195.57 1586.48
  198.35 1586.55  203.61 1588.51  215.21 1590.36  228.91 1593.11  235.01 1593.02
  246.72 1594.68  269.81 1607.39  277.66 1611.99  289.23 1619.61  298.74 1627.19
#Mann= 3 , 0 , 0
       0     .07       0  130.45     .05       0  195.57     .07       0
Bank Sta=130.45,195.57
Exp/Cntr=0.5,0.3

Type RM Length L Ch R = 1 ,20065   ,110.67,101.44,100.93
BEGIN DESCRIPTION:
19987.39
END DESCRIPTION:
XS GIS Cut Line= 6
  887857.5087313   808734.281803   887787.196003   808731.156019
  887646.5705465  808745.2189743   887584.071254   808768.656209
  887554.3834755  808787.4068161  887499.6955704  808838.9689373
#Sta/Elev= 30
       0 1671.37   23.48 1649.36   54.99 1610.64    66.6 1595.17  100.11 1596.73
   115.3 1596.46  116.29 1595.81  122.62 1593.76   129.3 1590.73  144.64 1586.89
   148.1 1586.01  211.71 1585.79  213.91 1585.81  217.69 1586.41  225.84 1587.87
  241.41 1593.17  248.92 1594.21  272.23 1598.42  286.03 1599.33  289.26 1600.01
  293.25 1601.58  300.36 1603.48  312.51 1610.28  322.18 1618.44  325.05 1619.67
  341.52 1621.67  361.82 1637.72  367.52 1641.64  370.59 1644.14  388.73 1654.71
#Mann= 3 , 0 , 0
       0     .07       0  144.64     .05       0  217.69    .065       0
#XS Ineff= 2 , 0
       0  135.45    1602  236.37       0    1602
Permanent Ineff=
       F       F
Bank Sta=144.64,217.69
Exp/Cntr=0.5,0.3