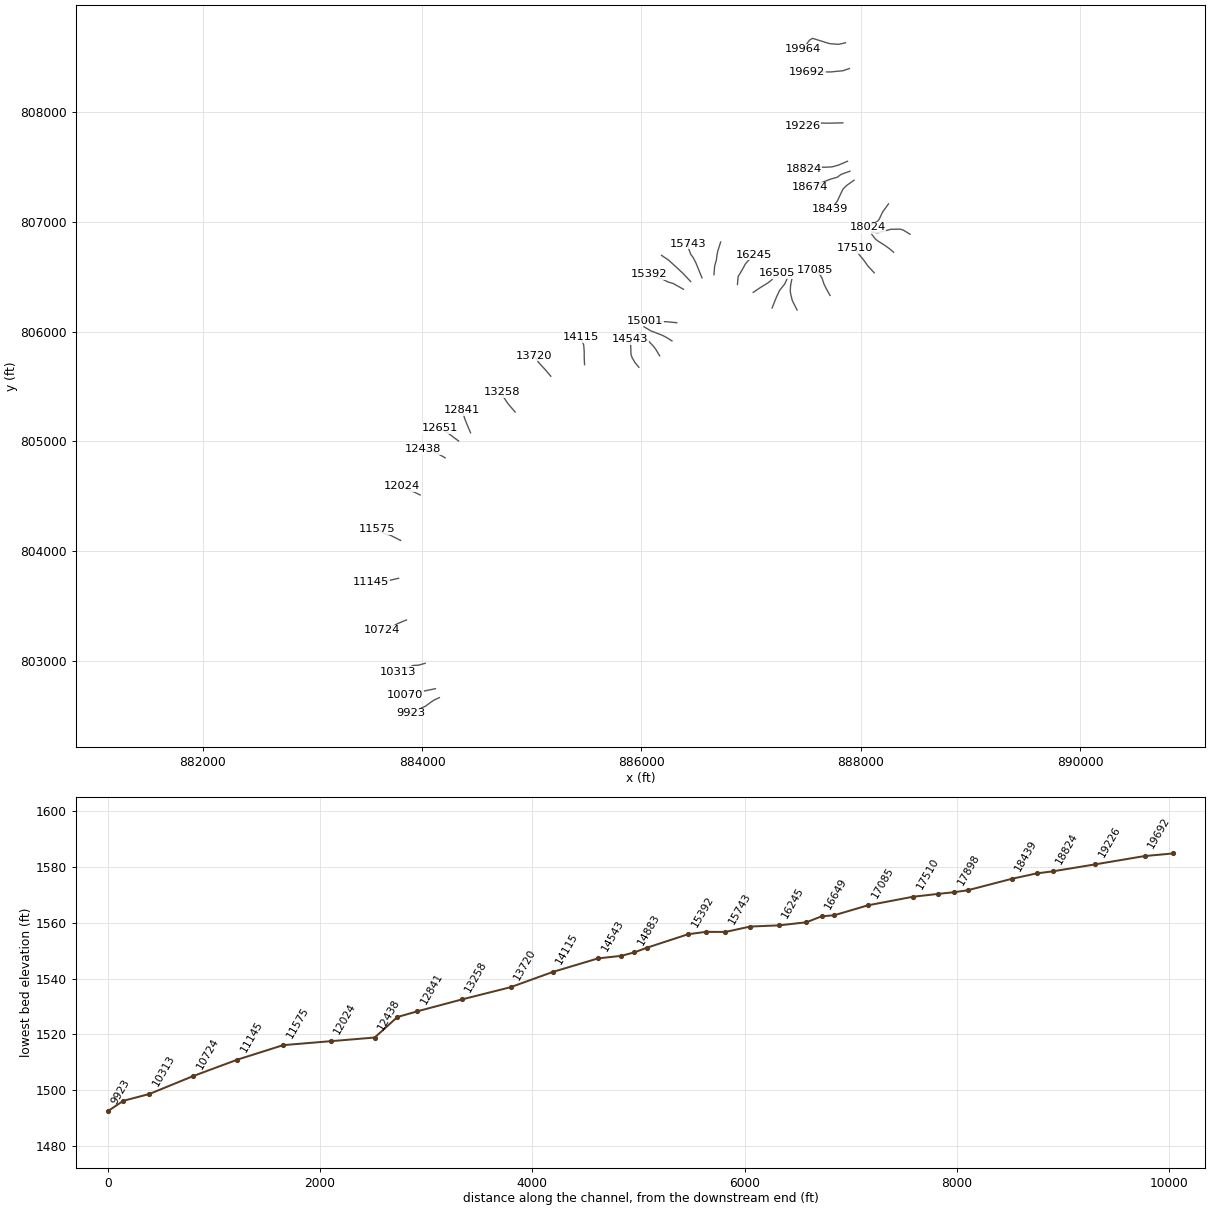
HEC-RAS study lds_big_laurel_crk.prj: lds_big_laurel_crk

--- lds_big_laurel_crk.g20 (geometry) --- (continued)

Type RM Length L Ch R = 3 ,20003   ,,,
BEGIN DESCRIPTION:
19931  FBSTR_1272
END DESCRIPTION:
Bridge Culvert--1,0,-1,-1, 0
Deck Dist Width WeirC Skew NumUp NumDn MinLoCord MaxHiCord MaxSubmerge Is_Ogee
34,44,2.6,0, 7, 7, , , 0.95, 0, 1,1,,
   61.44     141     141     186     231     231     295
 1602.04    1602    1602    1602    1602    1602    1602
                    1599    1599    1599
   50.22     142     142     187     232     232  357.33
 1601.99    1602    1602    1602    1602    1602 1602.01
                    1599    1599    1599
BR Coef=-1 , 0 , 0 ,, 0 ,,,0.8,0,,0,
WSPro=,,,, 1 ,,,, 0 ,,,, 0 ,,,,-1 ,-1 ,-1 , 0 , 0 , 0 , 0 , 0
BC Design=,, 0 ,, 0 ,,,,,,

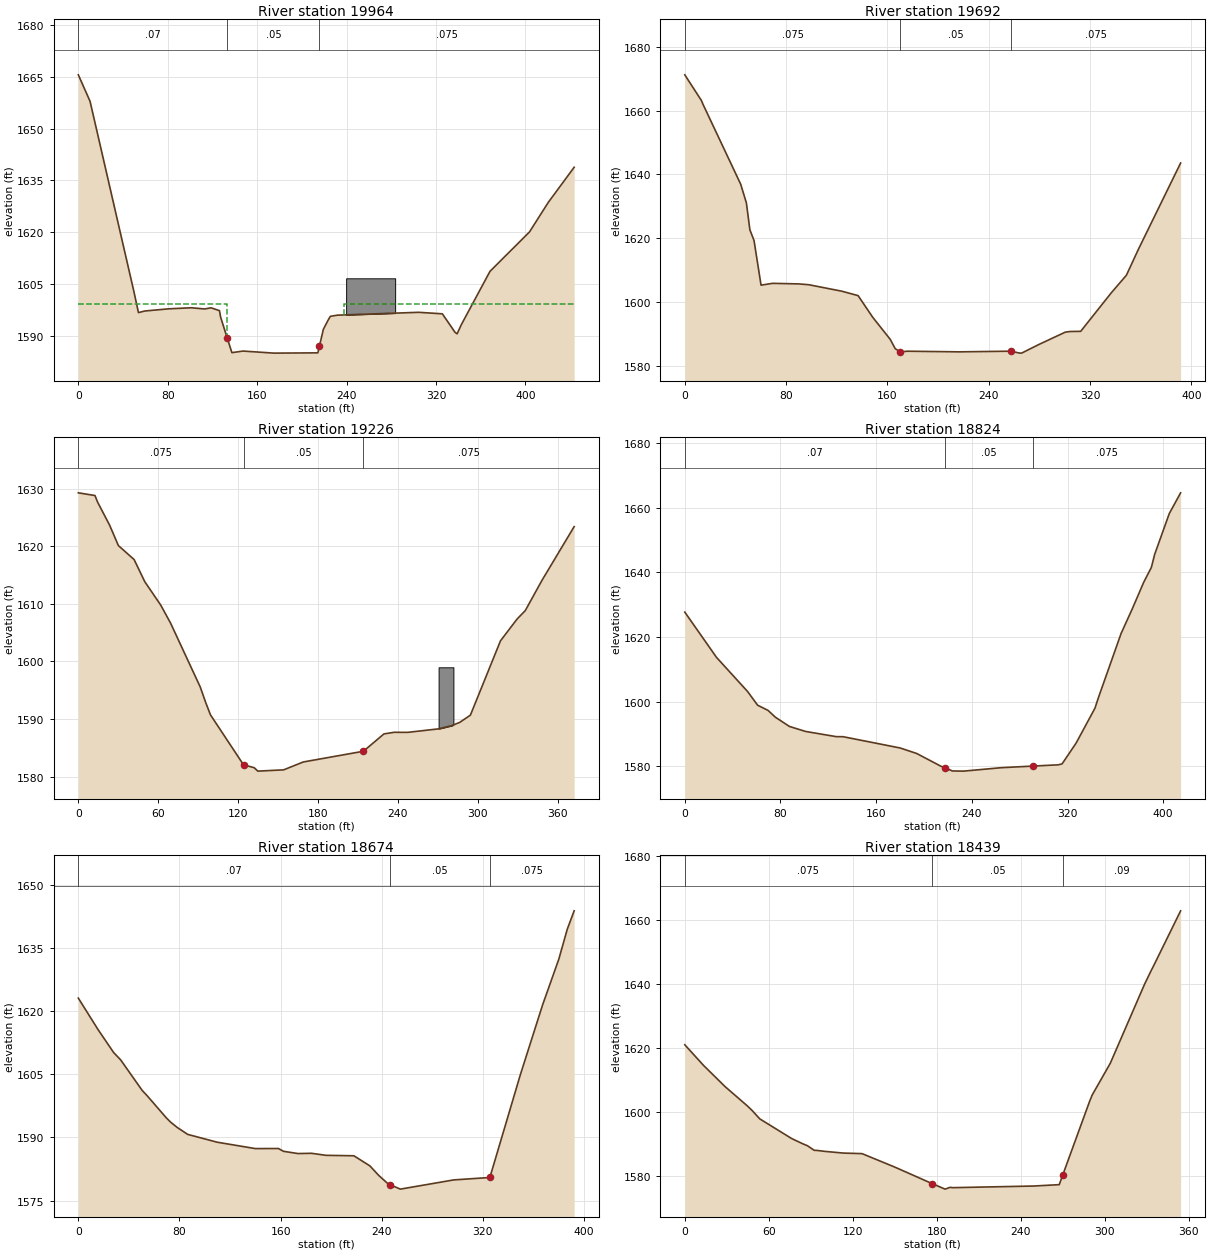
Type RM Length L Ch R = 1 ,19964   ,248.54,271.4,304.46
BEGIN DESCRIPTION:
19885.95
END DESCRIPTION:
XS GIS Cut Line= 6
  887859.0705991  808634.2812963  887796.5713066  808620.2193651
  887715.3203828  808626.4688847  887559.0711273  808674.9062461
  887530.9462409   808657.718531   887471.570684  808576.4686313
#Sta/Elev= 30
       0 1665.56    10.5 1657.88   49.66 1602.82   53.79 1596.65   59.49 1597.11
   81.03 1597.74  101.02 1598.05  113.04  1597.7  118.77 1598.03  126.26 1597.21
   127.3 1595.31  133.281589.211  137.37 1585.04  147.39  1585.5  174.97  1584.9
  214.28 1584.98  215.671586.902  219.22 1591.81  223.32 1594.38   225.5 1595.57
  231.73  1595.9  304.46 1596.73  325.67 1596.29  336.97 1590.95  338.86  1590.5
  342.71  1593.2  368.24 1608.59  403.61 1620.03  420.39 1628.58  443.56 1638.77
#Mann= 3 , 0 , 0
       0     .07       0  133.28     .05       0  215.67    .075       0
#XS Ineff= 2 , 0
       0  133.28    1599  237.24       0    1599
Permanent Ineff=
       F       F
#Block Obstruct= 1 ,-1
  239.58  283.431606.585
Bank Sta=133.28,215.67
Exp/Cntr=0.5,0.3

Type RM Length L Ch R = 1 ,19692   ,470.87,466.69,469.56
BEGIN DESCRIPTION:
19614.55
END DESCRIPTION:
XS GIS Cut Line= 6
  887895.0078971   808399.906901  887837.1962564  808379.5944261
  887724.6956863  808368.6562306  887635.6333752  808368.6562306
  887588.7578816  808370.2191225   887507.507982  808370.2191225
#Sta/Elev= 30
       0  1671.2   13.09 1663.17    14.6 1661.77   44.12 1636.93   48.65 1631.03
   51.38 1622.63   54.67 1619.26   60.21 1605.26   69.39 1605.83   90.03 1605.65
      98 1605.39  124.05 1603.36  136.84 1601.98  148.41 1595.18  162.28 1588.24
  166.18 1585.33  170.11 1584.36  175.98 1584.55  216.82 1584.35  257.32 1584.56
  264.58 1583.95  266.12 1583.98  279.28  1586.6  300.43 1590.52  304.22 1590.73
  312.61 1590.78  336.81 1602.88  348.71 1608.37  358.28 1616.58  391.52 1643.55
#Mann= 3 , 0 , 0
       0    .075       0  170.11     .05       0  257.32    .075       0
Bank Sta=170.11,257.32
Exp/Cntr=0.3,0.1

Type RM Length L Ch R = 1 ,19226   ,386.02,401.29,403.65
BEGIN DESCRIPTION:
19147.86
END DESCRIPTION:
XS GIS Cut Line= 6
  887835.6333644  807904.5940676  887707.5079712  807901.4693078
  887616.8837922  807903.0311756  887541.8834122  807904.5940676
  887513.7585257  807901.4693078  887470.0088161  807876.4691811
#Sta/Elev= 30
       0 1629.28    12.5 1628.81   14.45 1627.68   23.52 1623.66    30.1 1620.12
   41.92 1617.69   49.92 1613.85   61.88  1609.8   69.32 1606.65   91.63 1595.55
   95.61 1592.92   99.25 1590.74  124.13 1582.05  132.08 1581.56  134.85 1580.96
  154.24 1581.18  169.02 1582.55  214.18 1584.41  229.58 1587.42   237.3  1587.7
  247.44 1587.69  270.35 1588.29  280.23 1588.84  286.51 1589.42  294.55 1590.68
  317.17 1603.59  329.67 1607.38  335.78 1608.83  348.33 1614.09   372.5 1623.41
#Mann= 3 , 0 , 0
       0    .075       0  124.13     .05       0  214.18    .075       0
#Block Obstruct= 1 ,-1
  270.66  281.781598.987
Bank Sta=124.13,214.18
Exp/Cntr=0.3,0.1

Type RM Length L Ch R = 1 ,18824   ,88.86,150.36,179.82
BEGIN DESCRIPTION:
18746.57
END DESCRIPTION:
XS GIS Cut Line= 6
  887877.8212062  807554.5943425  887793.4455226  807518.6560203
  887735.6328577  807503.0311971  887670.0088054  807499.9064374
  887537.1957604  807504.5940891  887476.2583357  807484.2816142
#Sta/Elev= 30
       0 1627.72   26.57 1613.67   52.53 1603.11   60.88 1598.88   69.59 1597.27
   75.75 1595.15   87.46  1592.3  100.95 1590.75   126.7 1589.13  132.31 1589.12
   180.1 1585.62  193.88 1583.92  214.17 1579.97   217.3 1579.57  223.72  1578.5
  233.14 1578.45  264.41 1579.51  290.97 1580.01  312.17  1580.4  315.46 1580.69
  327.23 1587.16  342.96 1597.95  345.88 1601.26  364.82 1621.11  374.34 1628.88
  383.63  1636.9  390.14 1641.59  392.83 1645.56   405.1 1658.25  414.58 1664.68
#Mann= 3 , 0 , 0
       0     .07       0   217.3     .05       0  290.97    .075       0
Bank Sta=217.3,290.97
Exp/Cntr=0.3,0.1

Type RM Length L Ch R = 1 ,18674   ,113.72,234.89,274.25
BEGIN DESCRIPTION:
18596.21
END DESCRIPTION:
XS GIS Cut Line= 6
  887899.6955489  807463.9691393  887818.4456493  807434.2813609
   887785.633111  807409.2812342  887724.6956863  807392.0935191
  887635.6333752   807357.719113  887538.7586524  807315.5312713
#Sta/Elev= 30
       0 1623.15   15.53  1615.7   27.92 1610.21   33.47 1608.47   50.55 1601.18
   54.07 1600.06   69.49 1594.71   72.96 1593.66   78.27 1592.38    86.5 1590.74
  109.84 1588.88   140.1 1587.36  158.26 1587.38  162.27 1586.72  173.72 1586.18
   184.4 1586.24  195.95 1585.76  217.98 1585.65  230.62 1583.25  237.49 1581.02
  244.28 1579.18   246.7 1578.77  254.68 1577.72  296.92 1579.91  325.53 1580.49
  349.74 1605.03  367.25 1621.55  380.06 1632.41  386.76 1639.54   392.2 1643.91
#Mann= 3 , 0 , 0
       0     .07       0   246.7     .05       0  325.53    .075       0
Bank Sta=246.7,325.53
Exp/Cntr=0.3,0.1

Type RM Length L Ch R = 1 ,18439   ,416.49,415.64,390.09
BEGIN DESCRIPTION:
18361.32
END DESCRIPTION:
XS GIS Cut Line= 6
  887937.1957389  807381.1563477  887868.4459026  807332.7189864
  887837.1962564  807301.4693401  887784.0712432   807190.531662
   887751.258705  807143.6561685  887715.3203828   807115.531282
#Sta/Elev= 30
       0 1620.99   13.27 1614.58   28.78 1607.88   44.51 1601.91   48.02 1600.44
   53.56 1597.78   76.25 1591.64    84.1 1590.01   87.64 1589.36   92.51 1587.92
   94.19 1587.91  100.16 1587.59  113.35 1587.06  126.62 1586.89  150.01 1582.68
  176.55 1577.53  186.01 1575.77  189.55 1576.33  191.57 1576.23  249.34 1576.74
  267.55 1577.17  270.111580.248  289.71 1603.81  289.99    1604     291 1605.17
  304.03 1615.19  328.51 1639.94  333.42 1644.38  334.87 1645.61  354.29 1662.94
#Mann= 3 , 0 , 0
       0    .075       0  176.55     .05       0  270.11     .09       0
Bank Sta=176.55,270.11
Exp/Cntr=0.3,0.1

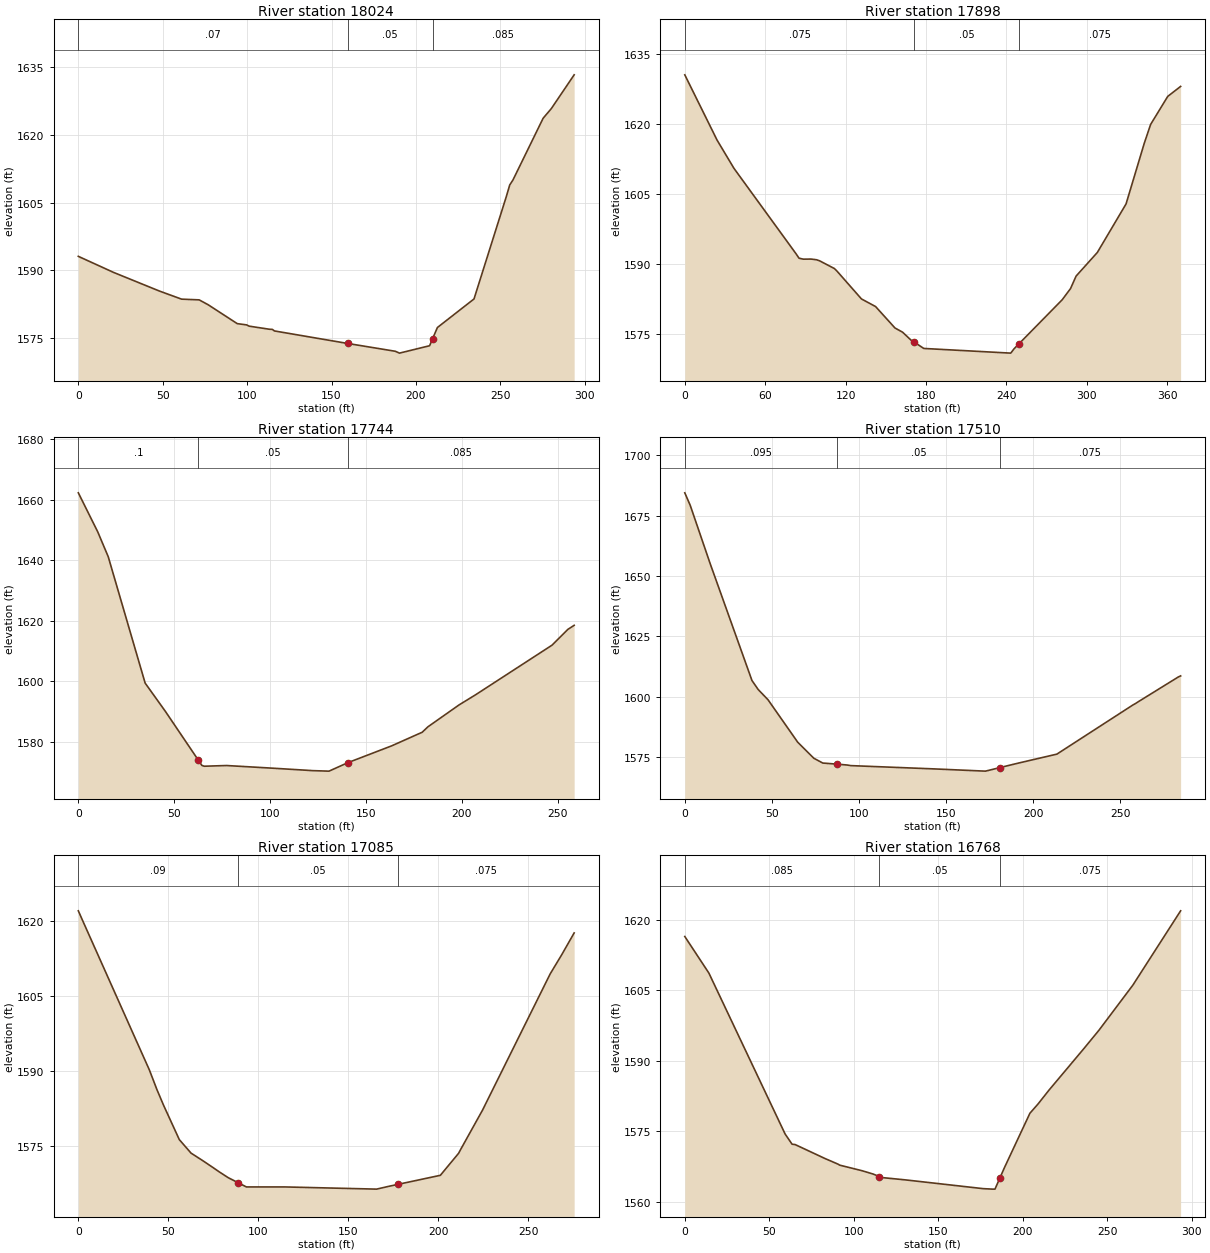
Type RM Length L Ch R = 1 ,18024   ,267.17,125.96,97.04
BEGIN DESCRIPTION:
17945.68
END DESCRIPTION:
XS GIS Cut Line= 5
   888251.258166  807165.5315354  888198.1331528  807092.0940473
  888165.3206146  807023.3442111  888151.2586834  807007.7193879
  888060.6334803  806953.0314828
#Sta/Elev= 25
       0 1593.12   20.81 1589.57   47.93 1585.44   61.17 1583.63   71.58 1583.47
   76.85  1582.4   94.13  1578.2   99.66 1577.92  101.21 1577.64  113.12 1576.96
  114.93 1576.92  116.17 1576.58  159.44 1573.81  187.78 1572.07  190.22 1571.66
  208.07  1573.3  209.851574.857  212.69 1577.34  234.37 1583.67  253.57 1606.45
  255.52 1608.94  257.44 1610.05  275.31 1623.74  280.16 1625.88  293.69 1633.37
#Mann= 3 , 0 , 0
       0     .07       0  159.44     .05       0  209.85    .085       0
Bank Sta=159.44,209.85
Exp/Cntr=0.3,0.1

Type RM Length L Ch R = 1 ,17898   ,217.81,153.31,64.42
BEGIN DESCRIPTION:
17819.71
END DESCRIPTION:
XS GIS Cut Line= 6
  888448.1333954  806888.9692983  888387.1959707  806926.4684641
  888357.5081923  806935.8437677  888273.1335329  806934.2818999
  888155.9463352  806903.0312294  888095.0078863  806909.2817732
#Sta/Elev= 30
       0 1630.51   24.07 1616.56   36.72  1610.5   83.13  1592.2   85.27 1591.29
   88.46 1591.08   94.27  1591.1   98.37 1590.95  100.68 1590.72   111.7 1589.07
  113.63 1588.52  131.89 1582.57  142.43 1580.94   156.9 1576.36  162.57 1575.46
  168.85 1573.77  171.44  1573.3  178.42 1571.98  243.32 1570.98  245.79  1571.9
  249.431572.962  281.73 1582.39  287.97 1584.79  292.12 1587.46  307.97 1592.51
  329.41 1602.89  342.91 1615.78  347.74 1619.89  360.55  1625.9  370.15 1628.03
#Mann= 3 , 0 , 0
       0    .075       0  171.44     .05       0  249.43    .075       0
Bank Sta=171.44,249.43
Exp/Cntr=0.3,0.1

Type RM Length L Ch R = 1 ,17744   ,254.21,234.83,203.7
BEGIN DESCRIPTION:
17666.41
END DESCRIPTION:
XS GIS Cut Line= 6
  888298.1336595  806724.9066071  888263.7582293  806754.5943856
  888218.4456277  806787.4069238  888154.3834432  806828.0318736
  888130.9462085  806846.7814565  888099.6955381  806887.4064063
#Sta/Elev= 23
       0 1662.31   10.11 1649.43   15.58 1641.22   34.83 1599.45   45.42 1590.07
   62.521574.024   64.41 1572.25   65.64 1571.98   77.27 1572.21  101.37 1571.33
  122.25 1570.52  130.21 1570.36  130.71 1570.36   140.5 1573.15  163.39 1578.72
  177.22 1582.63  179.26  1583.2  182.29 1585.02  198.45 1592.22  207.24 1595.64
  246.96 1611.98  255.19 1617.18  258.49 1618.54
#Mann= 3 , 0 , 0
       0      .1       0   62.52     .05       0   140.5    .085       0
Bank Sta=62.52,140.5
Exp/Cntr=0.3,0.1

Type RM Length L Ch R = 1 ,17510   ,439.96,424.41,404.63
BEGIN DESCRIPTION:
17431.57
END DESCRIPTION:
XS GIS Cut Line= 6
   888121.570905  806537.4066812  888062.1963723  806601.4688657
  888030.9457018  806646.7814673  887999.6960556  806684.2816573
  887976.2588209  806713.9694357  887946.5710424  806760.8439051
#Sta/Elev= 27
       0 1684.39    3.15 1679.15   14.53 1655.18   38.55 1606.79   42.12 1603.07
   47.74 1598.86   64.84 1581.25   74.03 1574.67   79.17 1572.68   87.35 1572.23
   93.09 1571.87   94.12 1571.76   95.18 1571.62  142.39 1570.28  170.98 1569.38
  172.52 1569.34  172.72 1569.37  180.781570.792  186.44 1571.79   191.2 1572.62
  191.42 1572.66  213.52 1576.37  257.18 1596.71   258.7 1597.32  260.31 1598.07
  283.06 1608.21  284.51 1608.71
#Mann= 3 , 0 , 0
       0    .095       0   87.35     .05       0  180.78    .075       0
Bank Sta=87.35,180.78
Exp/Cntr=0.3,0.1

Type RM Length L Ch R = 1 ,17085   ,327.83,316.81,278.42
BEGIN DESCRIPTION:
17007.17
END DESCRIPTION:
XS GIS Cut Line= 6
  887718.4461667  806331.1561482  887682.5088687  806396.7812247
  887662.1953696  806437.4061745  887646.5705465  806487.4064279
  887626.2580716  806521.7818581   887582.508362  806567.0944597
#Sta/Elev= 24
       0 1622.07    2.52 1620.01    39.5 1590.15   43.73 1586.18   47.38 1583.08
   56.11  1576.2   62.64 1573.49   69.11 1571.99   74.82  1570.6   78.61 1569.66
   83.28 1568.57   88.691567.576    93.4 1566.71  114.75 1566.71  165.73 1566.27
  172.63 1566.84  177.871567.244  201.18 1569.04  211.34 1573.46  212.55 1574.28
  224.62 1582.11  262.21 1609.42   268.6 1613.25  275.54 1617.64
#Mann= 3 , 0 , 0
       0     .09       0   88.69     .05       0  177.87    .075       0
Bank Sta=88.69,177.87
Exp/Cntr=0.3,0.1

Type RM Length L Ch R = 1 ,16768   ,188.9,118.87,52.9
BEGIN DESCRIPTION:
16690.36
END DESCRIPTION:
XS GIS Cut Line= 6
  887418.4456708  806198.3441275  887374.6959612  806284.2816788
  887359.0711381  806348.3438633  887355.9453541   806374.906882
  887359.0711381  806421.7813514  887370.0083094  806478.0311243
#Sta/Elev= 25
       0 1616.42   14.25 1608.65   59.38 1574.43    63.5 1572.26   65.33 1572.18
   83.03 1569.21   90.84    1568   91.68 1567.81  104.85 1566.63  111.45 1565.92
  113.38 1565.64     115 1565.23  130.45 1564.68  176.68 1562.81  182.15 1562.71
   183.6 1562.71  186.59 1565.15   189.2 1567.28  204.27 1578.84  209.06  1580.8
  215.44  1583.7  236.17 1592.57  245.14 1596.49  265.23 1606.09  293.48 1621.88
#Mann= 3 , 0 , 0
       0    .085       0     115     .05       0  186.59    .075       0
Bank Sta=115,186.59
Exp/Cntr=0.3,0.1

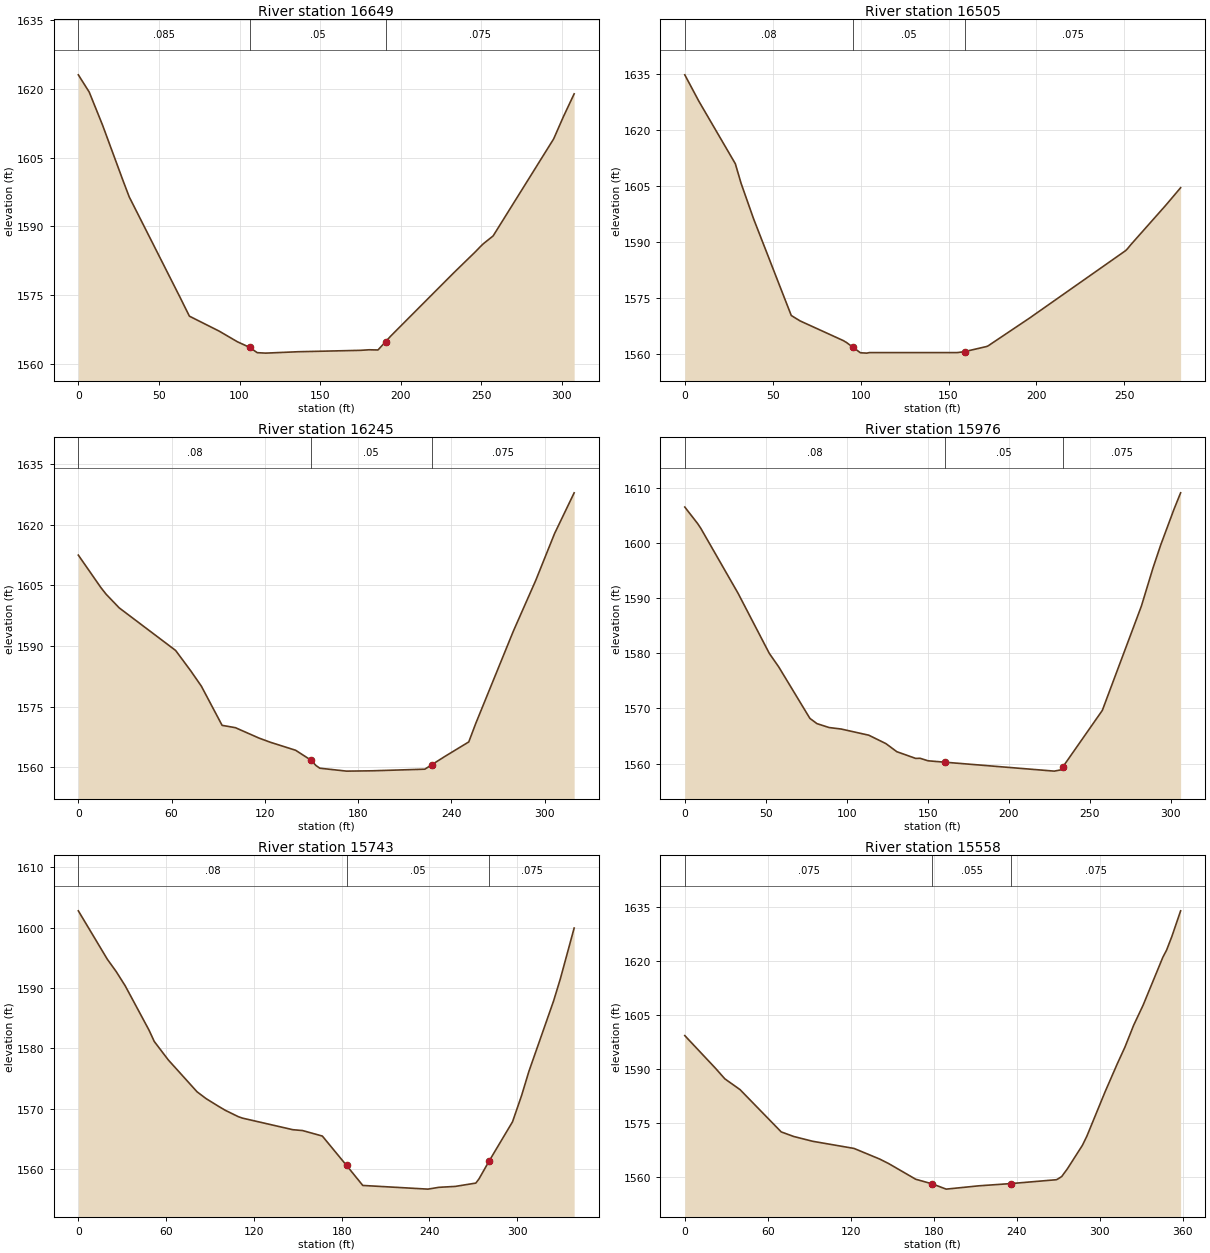
Type RM Length L Ch R = 1 ,16649   ,199.02,143.99,118.84
BEGIN DESCRIPTION:
16571.49
END DESCRIPTION:
XS GIS Cut Line= 5
  887190.3207951  806217.0937104  887227.8209851  806310.8436733
  887259.0706314  806378.0316418  887305.9461249  806435.8443067
  887329.3833596  806488.9693198
#Sta/Elev= 26
       0 1623.09    6.75 1619.33   15.04  1612.1   27.87 1599.86   31.57 1596.44
   63.06 1574.54    68.9  1570.4   87.44 1567.12   98.62 1564.82  106.18  1563.6
  110.98 1562.43  116.23 1562.33  136.07 1562.63  175.07 1562.94  180.37 1563.06
  185.89 1563.02  190.551564.811  193.75 1566.04  232.58 1579.76  246.08 1584.38
   249.5 1585.62  251.33 1586.24  257.31 1587.92  294.85  1609.1  300.91 1613.96
  307.57 1618.94
#Mann= 3 , 0 , 0
       0    .085       0  106.18     .05       0  190.55    .075       0
Bank Sta=106.18,190.55
Exp/Cntr=0.3,0.1

Type RM Length L Ch R = 1 ,16505   ,215.43,260.27,274.16
BEGIN DESCRIPTION:
16427.50
END DESCRIPTION:
XS GIS Cut Line= 6
  887018.4456923  806359.2810347  887071.5707055  806395.2193569
  887098.1337241  806412.4060478  887149.6958453  806443.6567183
  887182.5083835  806468.6568449  887234.0705047  806535.8437892
#Sta/Elev= 30
       0 1634.75    7.96 1627.71   28.74 1610.93      32  1605.7   39.13 1596.16
   60.56 1570.26   65.63  1568.8   90.33  1563.5    90.9 1563.32   91.21 1563.23
   91.88 1563.06   95.78  1561.7   99.88 1560.28  103.52 1560.18  104.92 1560.32
  154.89 1560.32  156.07 1560.39  159.32  1560.6  171.46 1561.93  172.22 1562.05
  172.78 1562.21  196.84 1569.81  197.32 1569.98  250.69 1587.63  251.74 1588.12
  253.86 1589.33  272.85 1599.42  273.67 1599.86  273.73 1599.89  282.01  1604.5
#Mann= 3 , 0 , 0
       0     .08       0   95.78     .05       0  159.32    .075       0
Bank Sta=95.78,159.32
Exp/Cntr=0.3,0.1

Type RM Length L Ch R = 1 ,16245   ,234.9,269.64,309.66
BEGIN DESCRIPTION:
16167.23
END DESCRIPTION:
XS GIS Cut Line= 6
   886874.695476  806431.1566549  886880.9460198   806503.031251
   886913.758558  806557.7191561  886948.1329641  806620.2194728
   886971.571223  806646.7814673  887023.1333441  806703.0312402
#Sta/Elev= 26
       0 1612.47   14.41  1604.5   17.84 1602.82   26.29 1599.43    62.6  1588.9
   72.36 1583.84   79.14 1580.08   92.49 1570.39  101.05 1569.81  116.24 1567.24
  123.74 1566.18  139.78 1564.23  149.64 1561.79  152.92 1560.44  155.36 1559.79
  172.57 1559.07  189.16 1559.15  222.92 1559.55   227.31560.632  235.89 1562.72
  251.18 1566.29  255.72  1570.9  279.82 1593.64  294.33 1606.28  306.34 1617.77
  318.98 1627.87
#Mann= 3 , 0 , 0
       0     .08       0  149.64     .05       0   227.3    .075       0
Bank Sta=149.64,227.3
Exp/Cntr=0.3,0.1

Type RM Length L Ch R = 1 ,15976   ,143.26,232.96,287.99
BEGIN DESCRIPTION:
15897.59
END DESCRIPTION:
XS GIS Cut Line= 6
  886660.6335557  806520.2189661  886666.8830753  806599.9059737
  886682.5078984  806653.0309869  886687.1955502  806693.6569608
  886695.0079617  806734.2819107  886721.5709804  806818.6565701
#Sta/Elev= 26
       0  1606.5    7.82 1603.55    9.77  1602.7   32.91 1590.86   52.17 1579.98
   57.95 1577.55   77.21 1568.21   81.55 1567.26   89.05 1566.55   96.48 1566.28
  113.56 1565.16  124.11 1563.64  130.87 1562.17  142.55 1560.95  145.18 1560.98
  150.17 1560.52  160.581560.267  228.04 1558.65  232.16 1558.88  233.21 1559.36
  257.71 1569.66  281.82 1588.56  288.97 1595.46  293.75 1599.64  301.93  1606.1
  306.03 1609.08
#Mann= 3 , 0 , 0
       0     .08       0  160.58     .05       0  233.21    .075       0
Bank Sta=160.58,233.21
Exp/Cntr=0.3,0.1

Type RM Length L Ch R = 1 ,15743   ,132.79,184.56,242.93
XS GIS Cut Line= 6
  886551.2587696  806492.0940796  886496.5708645  806626.4689924
  886473.1336298  806673.3434618  886448.1335031   806707.718892
   886429.382896  806760.8439051  886423.1333764  806803.0317469
#Sta/Elev= 30
       0  1602.8   19.88 1594.76   25.86 1592.75      32  1590.4   48.36 1583.03
    51.9 1581.17   61.46 1578.12   81.16 1572.83   87.34  1571.7   95.28 1570.51
  100.35 1569.78  109.45  1568.7  112.36 1568.46  146.69 1566.55  153.31 1566.41
  166.82  1565.5  183.35 1560.64  194.47 1557.32  238.98 1556.71  246.59 1557.01
  257.71 1557.16  271.76 1557.71  273.93 1558.41  280.82 1561.35  296.84 1567.86
  303.08 1572.24  308.04 1576.21  324.94 1587.89  329.51 1591.52  338.98 1599.95
#Mann= 3 , 0 , 0
       0     .08       0  183.35     .05       0  280.82    .075       0
Bank Sta=183.35,280.82
Exp/Cntr=0.3,0.1

Type RM Length L Ch R = 1 ,15558   ,114.21,166.46,199.39
BEGIN DESCRIPTION:
15480.07
END DESCRIPTION:
XS GIS Cut Line= 6
  886448.1335031  806457.7186494  886376.2578829  806534.2819214
  886309.0709386  806596.7812139  886274.6955084  806628.0318844
  886245.0087541  806654.5938788  886182.5084374  806696.7817206
#Sta/Elev= 30
       0 1599.33   22.26 1590.24   28.93 1587.35   39.94 1584.35   69.71 1572.62
   78.77 1571.35   92.45 1570.02  122.35 1568.04  140.97 1565.08  147.39 1563.84
  166.96 1559.49     1791558.193  188.98 1556.75  212.67 1557.67  236.14  1558.3
  268.68 1559.36  270.01 1559.63  272.52 1560.25  276.59 1562.37  287.51 1568.93
   290.7 1571.44  303.83 1583.71  312.66 1591.49  318.21 1596.13  324.58 1602.26
  331.29 1607.71  345.65 1621.08  348.35 1623.06  352.15 1626.83  358.48 1633.94
#Mann= 3 , 0 , 0
       0    .075       0     179    .055       0  236.14    .075       0
Bank Sta=179,236.14
Exp/Cntr=0.3,0.1

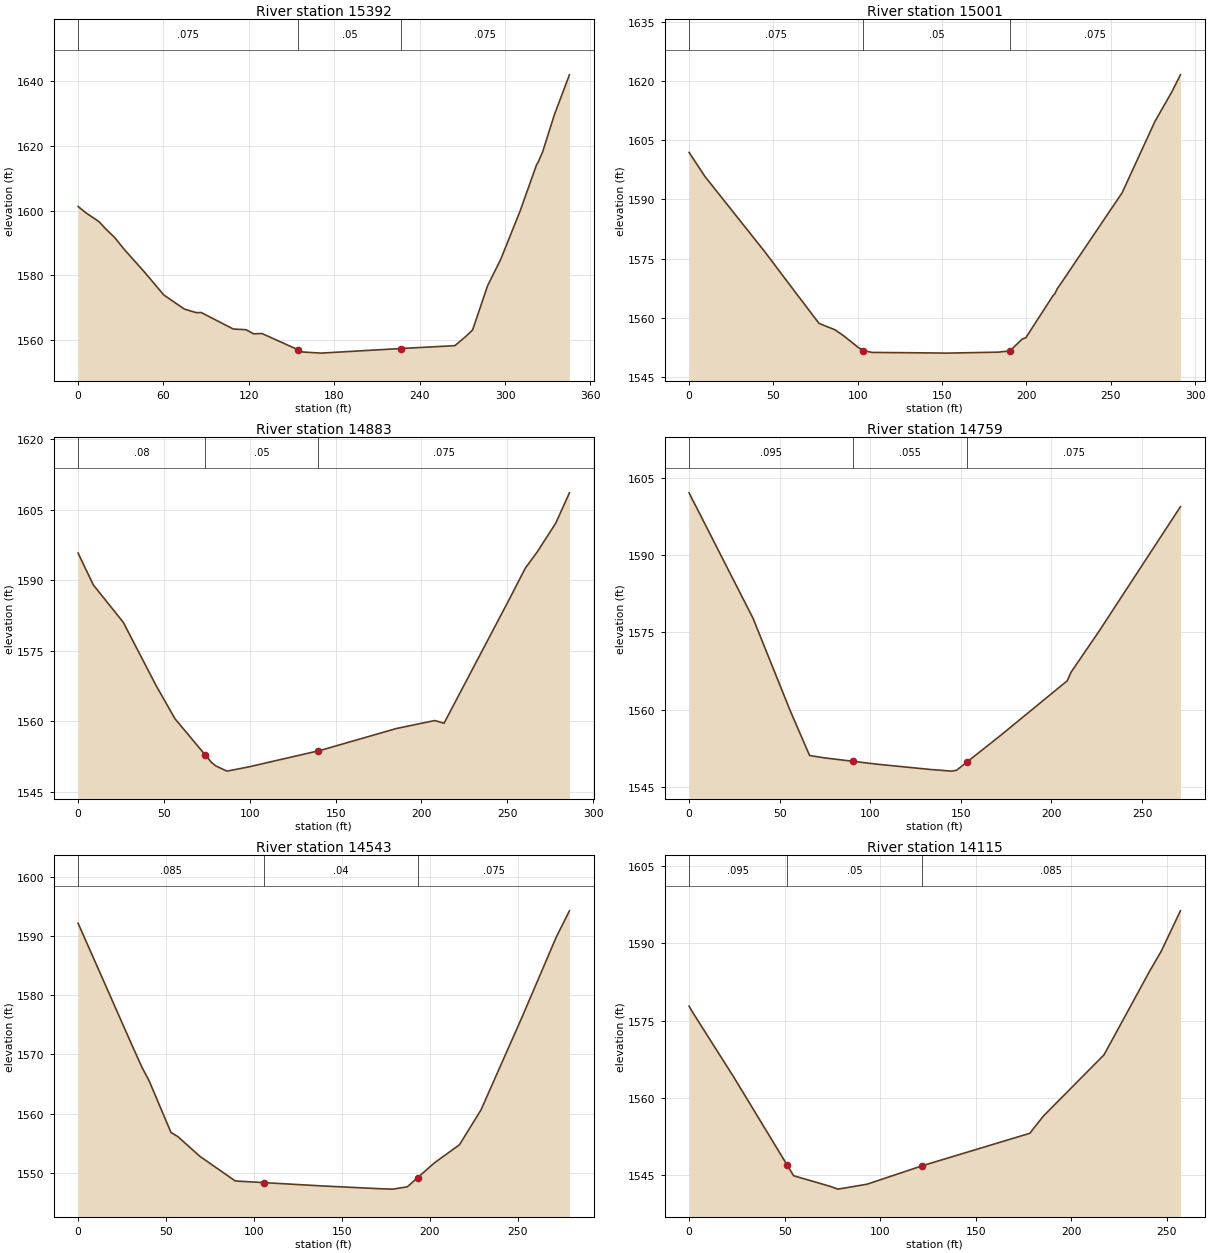
Type RM Length L Ch R = 1 ,15392   ,341.76,390.59,418.3
BEGIN DESCRIPTION:
15313.61
END DESCRIPTION:
XS GIS Cut Line= 6
  886382.5084266  806387.4069453  886288.7584637  806440.5319585
  886243.4458621  806453.0309976  886179.3836776  806485.8435359
  886148.1330072  806493.6569716  886068.4459995  806526.4684857
#Sta/Elev= 30
       0 1601.29    5.67 1599.28   14.73 1596.58   19.33 1594.39   25.76 1591.66
   32.36 1588.04   46.69 1580.97   60.21 1573.91   74.72 1569.53   83.08 1568.43
   86.58 1568.46     109 1563.37  118.08 1563.14  123.37 1561.88  129.24 1561.97
  154.78  1556.9     158 1556.25  170.59  1555.9  226.87 1557.33  264.75 1558.21
  272.26 1560.99  277.23 1563.07   287.8  1576.8  297.02 1584.96  310.59 1599.86
  322.12 1614.14  323.28    1615  326.45  1618.2  334.73 1629.73  345.28 1642.05
#Mann= 3 , 0 , 0
       0    .075       0  154.78     .05       0  226.87    .075       0
Bank Sta=154.78,226.87
Exp/Cntr=0.3,0.1

Type RM Length L Ch R = 1 ,15001   ,149.03,117.64,77.23
BEGIN DESCRIPTION:
14923.02
END DESCRIPTION:
XS GIS Cut Line= 6
  886321.5710019  806082.7187976  886224.6962792  806092.0941012
  886176.2578936  806092.0941012  886120.0081207   806095.218861
  886073.1336513  806096.7817529  886030.9458095  806099.9065127
#Sta/Elev= 28
       0 1601.88    9.39 1595.79   44.91  1576.7   64.06 1565.85   77.05 1558.56
   86.43 1556.95   91.35 1555.51   97.33 1553.49  100.29 1552.45  103.34 1551.68
  108.44 1551.21  145.77 1551.07  152.83 1551.03   183.5 1551.28  186.65 1551.44
  190.12 1551.55  197.52 1554.61  199.62 1554.91  215.55 1565.45  216.89  1566.1
  218.28 1567.36  220.59 1568.76     249 1586.76  256.75 1591.65  262.59 1597.09
  276.13 1609.67  286.19 1617.21  291.31 1621.54
#Mann= 3 , 0 , 0
       0    .075       0  103.34     .05       0  190.12    .075       0
Bank Sta=103.34,190.12
Exp/Cntr=0.3,0.1

Type RM Length L Ch R = 1 ,14883   ,159.23,124.56,80.34
BEGIN DESCRIPTION:
14805.37
END DESCRIPTION:
XS GIS Cut Line= 6
  886277.8212923  805917.0942386   886227.821039  805948.3438849
  886191.8837409  805967.0934678  886112.1957091  805998.3441382
  886088.7584744  806006.1565498   886023.133398  806045.2186076
#Sta/Elev= 22
       0 1595.74    8.86 1588.97   26.32 1581.01    45.4 1567.58   56.42 1560.51
   74.151552.772   77.66 1551.24   80.23 1550.47    86.7 1549.37    99.5 1550.28
  139.55 1553.65  141.12 1553.78   185.1  1558.4   185.4 1558.43  207.77 1560.13
  213.13 1559.55  251.54 1586.19  260.52 1592.55  267.43 1595.99  278.21  1602.1
  283.67 1606.51  286.18 1608.55
#Mann= 3 , 0 , 0
       0     .08       0   74.15     .05       0  139.55    .075       0
Bank Sta=74.15,139.55
Exp/Cntr=0.3,0.1

Type RM Length L Ch R = 1 ,14759   ,226.14,215.74,139.62
BEGIN DESCRIPTION:
14680.82
END DESCRIPTION:
XS GIS Cut Line= 6
  886165.3207223  805781.1564339  886130.9463162  805838.9690988
  886109.0709493  805868.6568772  886062.1954558  805917.0942386
  886035.6334613  805938.9685813  885988.7579677  805984.2811829
#Sta/Elev= 21
       0 1602.07    1.05 1601.33   35.33 1577.72   55.66 1559.95   66.49 1551.16
   67.26 1551.11   74.53  1550.7   90.731550.013  103.07 1549.49  104.14 1549.45
  133.17 1548.44  144.88 1548.12  147.44 1548.28  147.62 1548.29  153.151549.827
  171.55 1554.94  205.96 1564.85  208.68 1565.61  210.73 1567.26  226.27 1575.25
  271.16 1599.38
#Mann= 3 , 0 , 0
       0    .095       0   90.73    .055       0  153.15    .075       0
Bank Sta=90.73,153.15
Exp/Cntr=0.3,0.1

Type RM Length L Ch R = 1 ,14543   ,469.1,427.57,444.64
BEGIN DESCRIPTION:
14465.07
END DESCRIPTION:
XS GIS Cut Line= 6
  885976.2579044  805676.4692996  885940.3206064  805720.2190092
  885915.3204797   805762.406851  885904.3833083  805793.6564972
  885902.8204164   805835.844339  885899.6956566  805934.2819537
#Sta/Elev= 23
       0 1592.19   30.89 1571.41   36.28 1567.86    40.4 1565.55   52.82 1556.82
   56.62 1556.14   56.68 1556.13   69.25 1552.78   81.761550.192   89.41 1548.61
  105.66 1548.33  138.76 1547.77  173.03 1547.28  179.17 1547.23  180.98 1547.32
  187.24 1547.62  193.161549.175  202.58 1551.65  216.91 1554.73  229.14 1560.61
  252.79  1576.5  272.03 1589.88  279.47 1594.29
#Mann= 3 , 0 , 0
       0    .085       0  105.66     .04       0  193.16    .075       0
Bank Sta=105.66,193.16
Exp/Cntr=0.3,0.1

Type RM Length L Ch R = 1 ,14115   ,354.59,395.82,453.89
BEGIN DESCRIPTION:
14037.50
END DESCRIPTION:
XS GIS Cut Line= 5
  885480.9460952  805699.9065343  885477.8213354  805773.3440223
  885477.8213354  805821.7813837  885473.1336836  805879.5940486
  885445.0087972  805951.4686447
#Sta/Elev= 19
       0  1577.8    2.06  1576.5   23.31  1564.1   51.371546.983   54.72 1544.94
   69.91 1543.31    73.5 1542.92   73.71  1542.9   77.92 1542.35   93.01 1543.29
   93.93  1543.4  121.94 1546.87  178.38 1553.18  179.94 1553.96  185.62 1556.59
  217.14 1568.37  241.23 1584.73  247.07 1588.44  257.13 1596.28
#Mann= 3 , 0 , 0
       0    .095       0   51.37     .05       0  121.94    .085       0
Bank Sta=51.37,121.94
Exp/Cntr=0.3,0.1

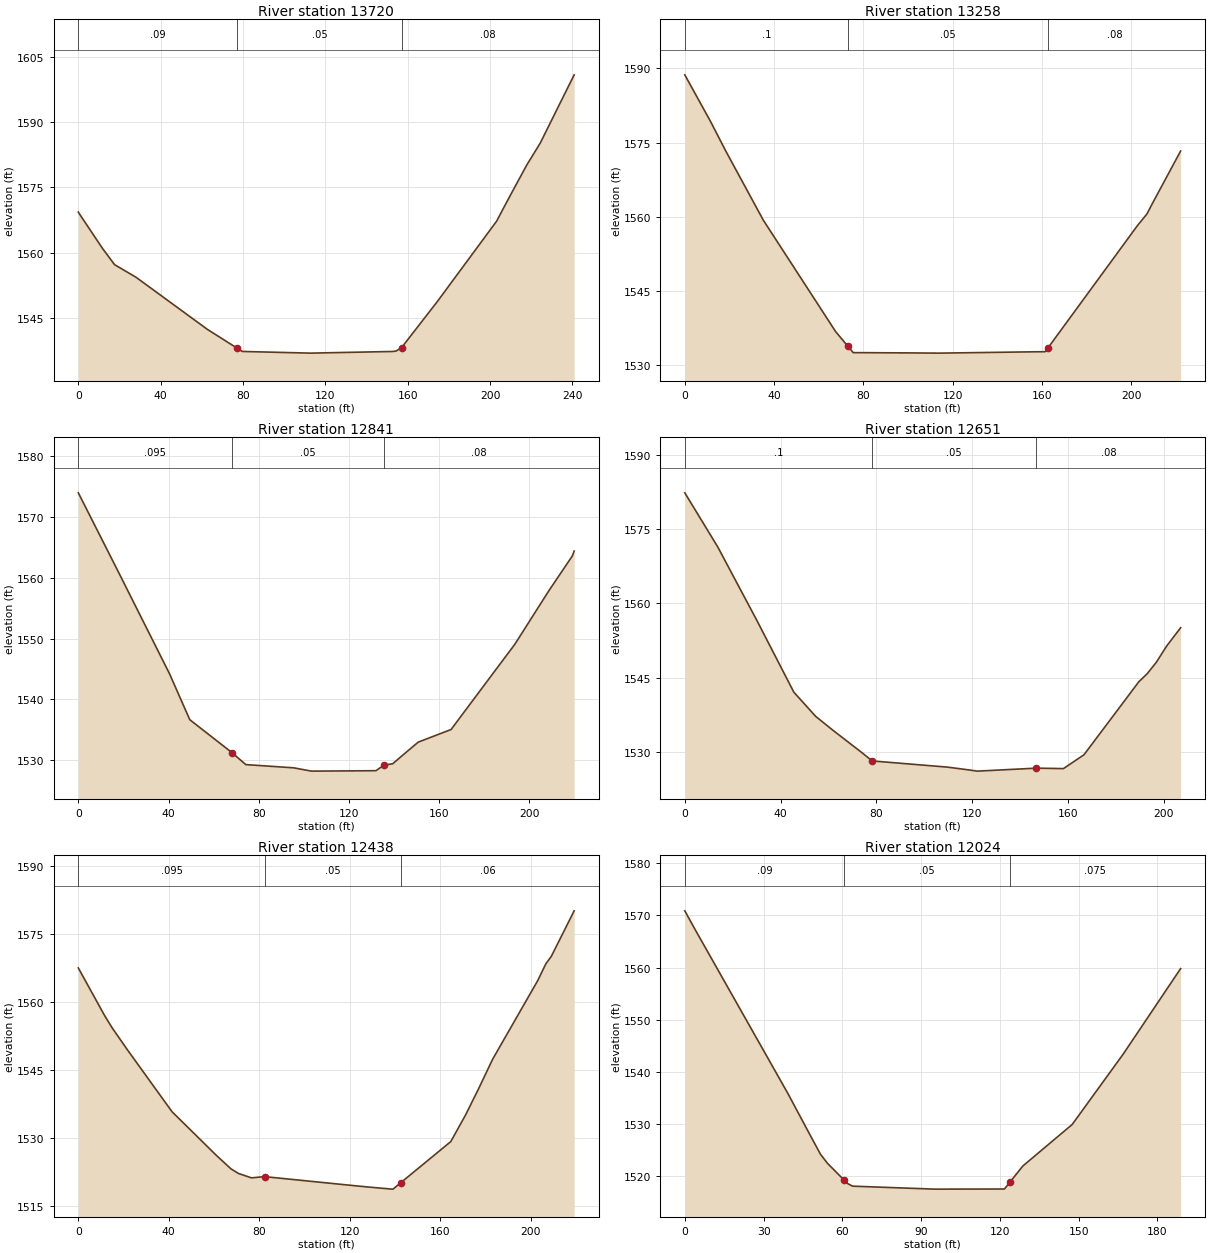
Type RM Length L Ch R = 1 ,13720   ,467.71,461.42,449.09
BEGIN DESCRIPTION:
13641.68
END DESCRIPTION:
XS GIS Cut Line= 6
  885173.1331877     805595.2194  885118.4463067  805659.2815845
  885080.9461167  805699.9065343  885059.0707498  805724.9066609
  885040.3211669  805756.1563072  885023.1334518  805782.7193259
#Sta/Elev= 22
       0 1569.33    1.47 1568.25   11.74 1560.98    17.6 1557.24   28.04 1554.34
   62.66 1542.37   77.141538.033   79.62 1537.29   84.23 1537.23  112.77  1536.9
  152.74 1537.28  154.38 1537.38  157.01 1538.17  172.74 1547.77  173.91 1548.47
  203.18 1567.25  206.97 1570.66  209.18  1572.6  210.36 1573.65  217.79 1580.14
  224.32 1585.17  240.82 1600.89
#Mann= 3 , 0 , 0
       0     .09       0   77.14     .05       0  157.01     .08       0
Bank Sta=77.14,157.01
Exp/Cntr=0.3,0.1

Type RM Length L Ch R = 1 ,13258   ,437.71,417.35,404.61
BEGIN DESCRIPTION:
13180.26
END DESCRIPTION:
XS GIS Cut Line= 4
  884848.1335892  805268.6569095  884784.0703806  805343.6562654
  884751.2588665  805392.0936268  884724.6958478  805451.4691837
#Sta/Elev= 17
       0 1588.72   11.59 1579.25   18.21 1573.45   35.17 1559.36   67.61 1536.82
    73.11533.858   75.47 1532.58   98.64 1532.53  113.94 1532.48  157.14 1532.75
  161.28 1532.76  161.61 1532.83  162.761533.539  202.82 1558.24  207.08 1560.59
  209.68 1562.84  222.19 1573.32
#Mann= 3 , 0 , 0
       0      .1       0    73.1     .05       0  162.76     .08       0
Bank Sta=73.1,162.76
Exp/Cntr=0.3,0.1

Type RM Length L Ch R = 1 ,12841   ,153.88,189.46,248.56
BEGIN DESCRIPTION:
12762.91
END DESCRIPTION:
XS GIS Cut Line= 4
   884441.883067  805079.5940917  884413.7581806  805145.2191682
  884387.1961861  805212.4061124  884366.8837112  805285.8436005
#Sta/Elev= 21
       0 1573.91   18.37 1560.48   40.47 1544.19   49.41 1536.68   68.29 1531.23
   69.21 1530.92    71.4 1530.22   74.28 1529.31   95.53 1528.78  103.34 1528.24
  131.94 1528.31  135.55 1529.23   139.4 1529.45  143.64  1530.8  150.72    1533
  165.27 1535.07   186.6 1545.63  193.53 1549.05  208.55  1557.8  219.03 1563.55
  219.84 1564.35
#Mann= 3 , 0 , 0
       0    .095       0   68.29     .05       0  135.55     .08       0
Bank Sta=68.29,135.55
Exp/Cntr=0.3,0.1

Type RM Length L Ch R = 1 ,12651   ,201.22,213.44,235.19
BEGIN DESCRIPTION:
12573.45
END DESCRIPTION:
XS GIS Cut Line= 4
   884332.508281  805004.5937116  884263.7584447   805056.156857
   884237.195426  805076.4693319  884162.1960702  805121.7819335
#Sta/Elev= 20
       0 1582.31   13.78 1571.38   30.28 1556.39   45.51 1542.11   54.61 1537.23
   61.85 1534.41   74.18 1529.81   78.21 1528.23  109.85 1526.97  119.38 1526.36
  122.05 1526.17  122.16 1526.17  146.81 1526.77  158.08 1526.68  166.65 1529.47
  189.54 1544.19  193.03 1545.81  196.89 1548.15  201.16  1551.4     207 1555.09
#Mann= 3 , 0 , 0
       0      .1       0   78.21     .05       0  146.81     .08       0
Bank Sta=78.21,146.81
Exp/Cntr=0.3,0.1

Type RM Length L Ch R = 1 ,12438   ,409.44,414.14,408.77
BEGIN DESCRIPTION:
12360.01
END DESCRIPTION:
XS GIS Cut Line= 4
  884210.6334315   804851.469216  884116.8834686  804903.0313371
  884096.5709937  804913.9685085  884009.0705503  804931.1562236
#Sta/Elev= 25
       0 1567.54    11.6 1557.07   15.01 1554.31   21.65 1549.55   41.42 1535.88
   60.81 1526.36   67.49 1523.29   70.78 1522.28   76.57  1521.3   82.38 1521.58
   84.58 1521.46  117.82 1519.79  126.83 1519.35  130.06  1519.2  138.72 1518.82
  139.12 1518.82  142.571520.233   164.7  1529.3  171.21 1535.14  177.02 1540.97
  183.21 1547.45  203.19 1564.81   206.7 1568.44  209.15 1570.11  219.24 1580.13
#Mann= 3 , 0 , 0
       0    .095       0   82.38     .05       0  142.57     .06       0
Bank Sta=82.38,142.57
Exp/Cntr=0.3,0.1

Type RM Length L Ch R = 1 ,12024   ,451.72,448.37,455.33
BEGIN DESCRIPTION:
11945.86
END DESCRIPTION:
XS GIS Cut Line= 4
  883982.5085558  804512.4066622  883927.8206507  804538.9686567
  883885.6338331  804556.1563718  883812.1963451  804593.6565618
#Sta/Elev= 16
       0 1570.89    3.85 1567.37   39.25 1535.86   47.33 1528.25   51.68 1524.19
   54.32 1522.47    60.8 1519.17   62.02 1518.57    63.9 1518.08   95.04 1517.51
  121.71 1517.53  123.751518.812  128.76 1521.96  147.54 1529.92  167.03 1543.47
  188.81 1559.81
#Mann= 3 , 0 , 0
       0     .09       0    60.8     .05       0  123.75    .075       0
Bank Sta=60.8,123.75
Exp/Cntr=0.3,0.1

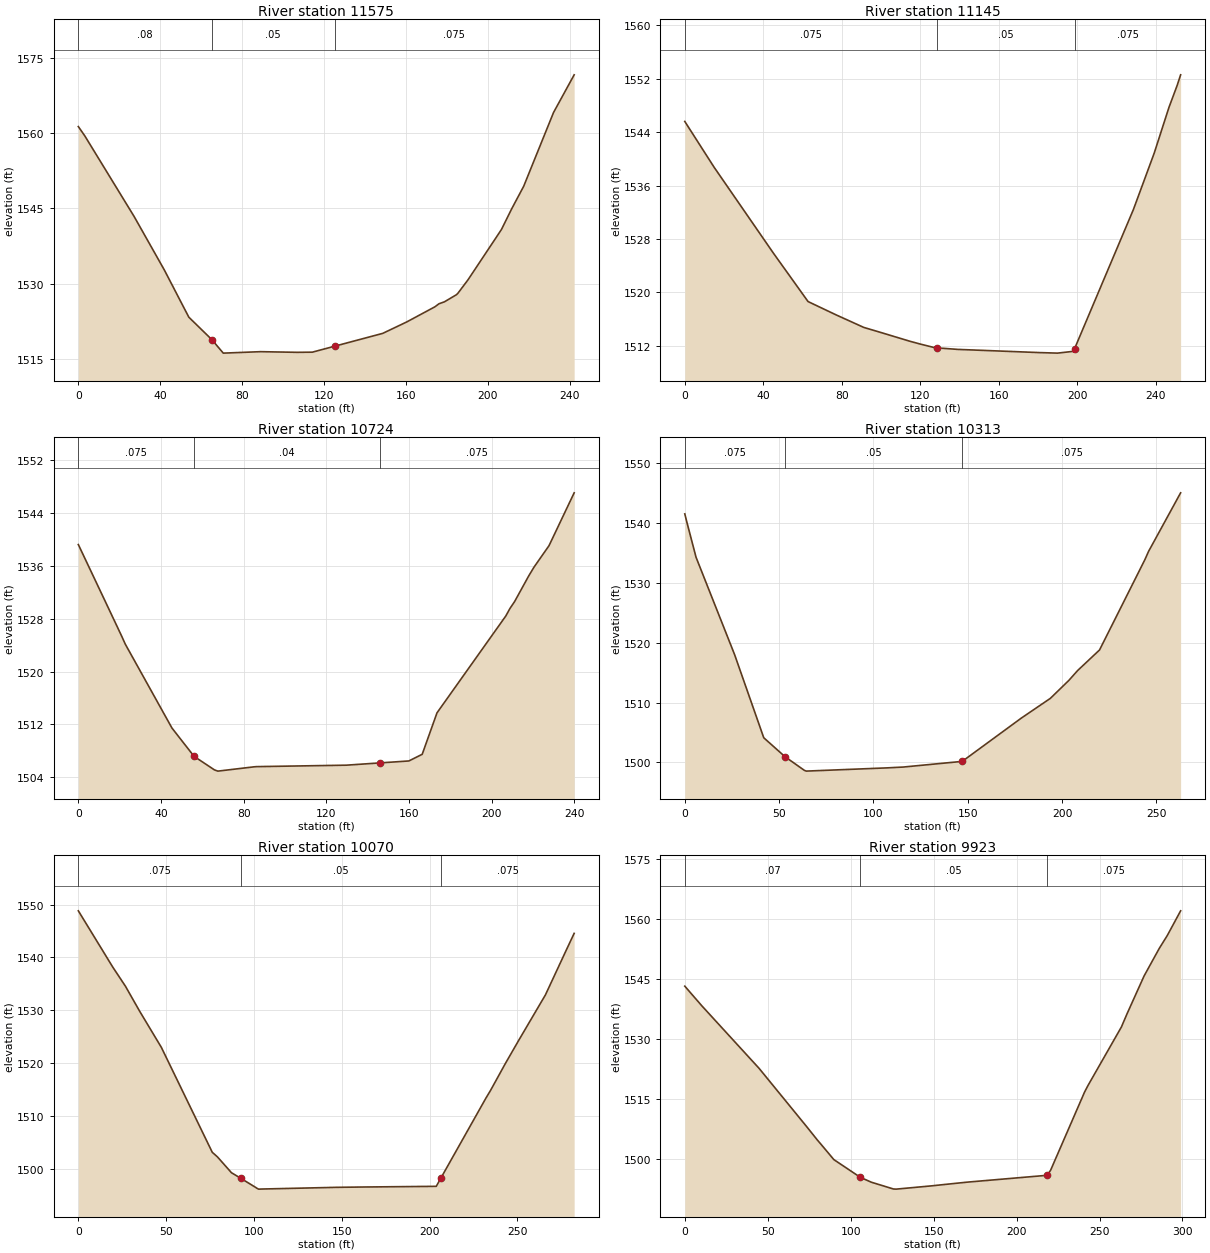
Type RM Length L Ch R = 1 ,11575   ,376.74,430.65,465.54
BEGIN DESCRIPTION:
11497.5
END DESCRIPTION:
XS GIS Cut Line= 6
  883804.3829093  804098.3437284   883738.758857  804131.1562667
  883709.0710786  804146.7810898  883657.5079332  804160.8440451
  883620.0087674   804182.719412  883585.6333372  804199.9061029
#Sta/Elev= 26
       0 1561.37    3.14 1559.52   27.21 1543.43   42.04 1532.69   53.98 1523.27
   65.22 1518.79    70.8 1516.09   89.04 1516.38  106.92 1516.25  114.31 1516.28
  114.57 1516.31   125.21517.471  148.72 1520.04  160.37 1522.31   174.2 1525.35
   176.2 1525.96  178.83 1526.34  184.69 1527.76  185.34 1528.01   190.4 1530.77
  203.78    1539  206.71 1540.81  211.67 1544.91  217.55 1549.43  232.15 1564.19
  242.21 1571.71
#Mann= 3 , 0 , 0
       0     .08       0   65.22     .05       0   125.2    .075       0
Bank Sta=65.22,125.2
Exp/Cntr=0.3,0.1

Type RM Length L Ch R = 1 ,11145   ,396.5,420.48,446.99
BEGIN DESCRIPTION:
11066.85
END DESCRIPTION:
XS GIS Cut Line= 5
  883785.6333264  803753.0316551  883710.6329464    803735.84394
  883655.9460654  803731.1562882  883607.5087041  803723.3438766
  883535.6330838  803721.7809847
#Sta/Elev= 23
       0 1545.61   14.92 1538.76   45.21 1525.86   62.84 1518.62   76.94 1516.65
   91.27 1514.74   98.19 1514.14  115.34 1512.62   115.4 1512.62  120.04 1512.25
   128.6 1511.62  130.74 1511.62  131.83 1511.61  139.08 1511.45   180.9 1510.97
  189.97 1510.89  198.16 1511.16  198.711511.543   228.7  1532.4  239.33 1540.87
  246.81 1547.69  251.07 1551.05  252.79  1552.6
#Mann= 3 , 0 , 0
       0    .075       0   128.6     .05       0  198.71    .075       0
Bank Sta=128.6,198.71
Exp/Cntr=0.3,0.1

Type RM Length L Ch R = 1 ,10724   ,428.93,410.85,405.9
BEGIN DESCRIPTION:
10646.37
END DESCRIPTION:
XS GIS Cut Line= 4
  883857.5079225  803373.3441515  883777.8209148  803340.5316133
  883740.3207248  803318.6562464  883637.1954583  803279.5941886
#Sta/Elev= 22
       0 1539.24   18.99 1526.69      21 1525.35   22.74 1524.15    45.3 1511.46
   56.01 1507.17   65.84 1505.13   67.51 1504.94      85 1505.59   86.18 1505.62
  129.59 1505.84   145.81506.182  159.91 1506.48  166.36 1507.49  173.51 1513.76
  206.81 1528.43  208.82 1529.57  211.03 1530.59  217.87 1534.48  220.47 1535.83
  227.71 1539.07  239.87 1547.07
#Mann= 3 , 0 , 0
       0    .075       0   56.01     .04       0   145.8    .075       0
Bank Sta=56.01,145.8
Exp/Cntr=0.3,0.1

Type RM Length L Ch R = 1 ,10313   ,244.69,243.7,227.78
BEGIN DESCRIPTION:
10235.52
END DESCRIPTION:
XS GIS Cut Line= 4
  884027.8211574  802978.0318248  883965.3208407  802960.8441097
  883923.1329989  802959.2812177  883777.8209148  802903.0314448
#Sta/Elev= 21
       0 1541.56    1.17 1540.09    5.97  1534.3   26.41 1518.02   41.86 1504.12
   53.14 1500.95   63.43 1498.66   64.46 1498.54   64.82 1498.55  106.98 1499.08
  107.04 1499.08  115.75 1499.22  147.09 1500.17  178.46 1507.42  193.81 1510.71
   203.6 1513.71  208.26 1515.36  219.87  1518.8  243.91  1533.9  245.86 1535.28
  262.86 1545.08
#Mann= 3 , 0 , 0
       0    .075       0   53.14     .05       0  147.09    .075       0
Bank Sta=53.14,147.09
Exp/Cntr=0.3,0.1

Type RM Length L Ch R = 1 ,10070   ,101.81,146.88,170.67
BEGIN DESCRIPTION:
9991.831
END DESCRIPTION:
XS GIS Cut Line= 5
  884121.5711204  802746.7811652  884030.9459172  802728.0315823
  883959.0713211  802717.0944109  883882.5080491  802703.0314556
  883846.5707511  802687.4066325
#Sta/Elev= 25
       0 1548.84   19.66 1538.15   26.84 1534.55   34.81 1529.88   47.26 1522.98
   76.25  1503.1   79.25 1502.21   87.17 1499.23   92.54 1498.16  100.98 1496.44
  101.72 1496.27  102.63 1496.12  105.95 1496.15  147.11 1496.46  164.57 1496.53
  165.25 1496.53  203.77 1496.65  206.46 1498.24  232.01 1513.34  234.75 1514.86
  243.09  1519.9  250.78 1524.34  265.92 1532.91  278.19 1541.68  282.28 1544.57
#Mann= 3 , 0 , 0
       0    .075       0   92.54     .05       0  206.46    .075       0
Bank Sta=92.54,206.46
Exp/Cntr=0.3,0.1

Type RM Length L Ch R = 1 ,9923    ,62.88,97.46,124.19
BEGIN DESCRIPTION:
9844.953
END DESCRIPTION:
XS GIS Cut Line= 6
  884157.5084184  802665.5312656   884107.508165  802642.0940309
   884073.133759  802618.6567962  884030.9459172  802587.4061258
  883970.0084925  802559.2812393  883896.5710045  802521.7810493
#Sta/Elev= 26
       0 1543.17   10.32 1538.23   44.79  1522.6   73.28 1508.11   79.92 1504.66
   82.31  1503.5   89.83 1499.77  105.72 1495.35  112.39 1494.11  125.81  1492.4
  127.45 1492.37  149.33 1493.21  153.81 1493.41  170.04 1494.11  216.44 1495.76
  218.41 1495.84  220.52 1497.09  241.01 1516.68  243.06 1518.31  263.26    1533
  263.98 1533.72  266.63 1536.28  276.87 1545.72  286.02 1552.62  290.86 1555.85
   298.9 1562.03
#Mann= 3 , 0 , 0
       0     .07       0  105.72     .05       0  218.41    .075       0
Bank Sta=105.72,218.41
Exp/Cntr=0.3,0.1