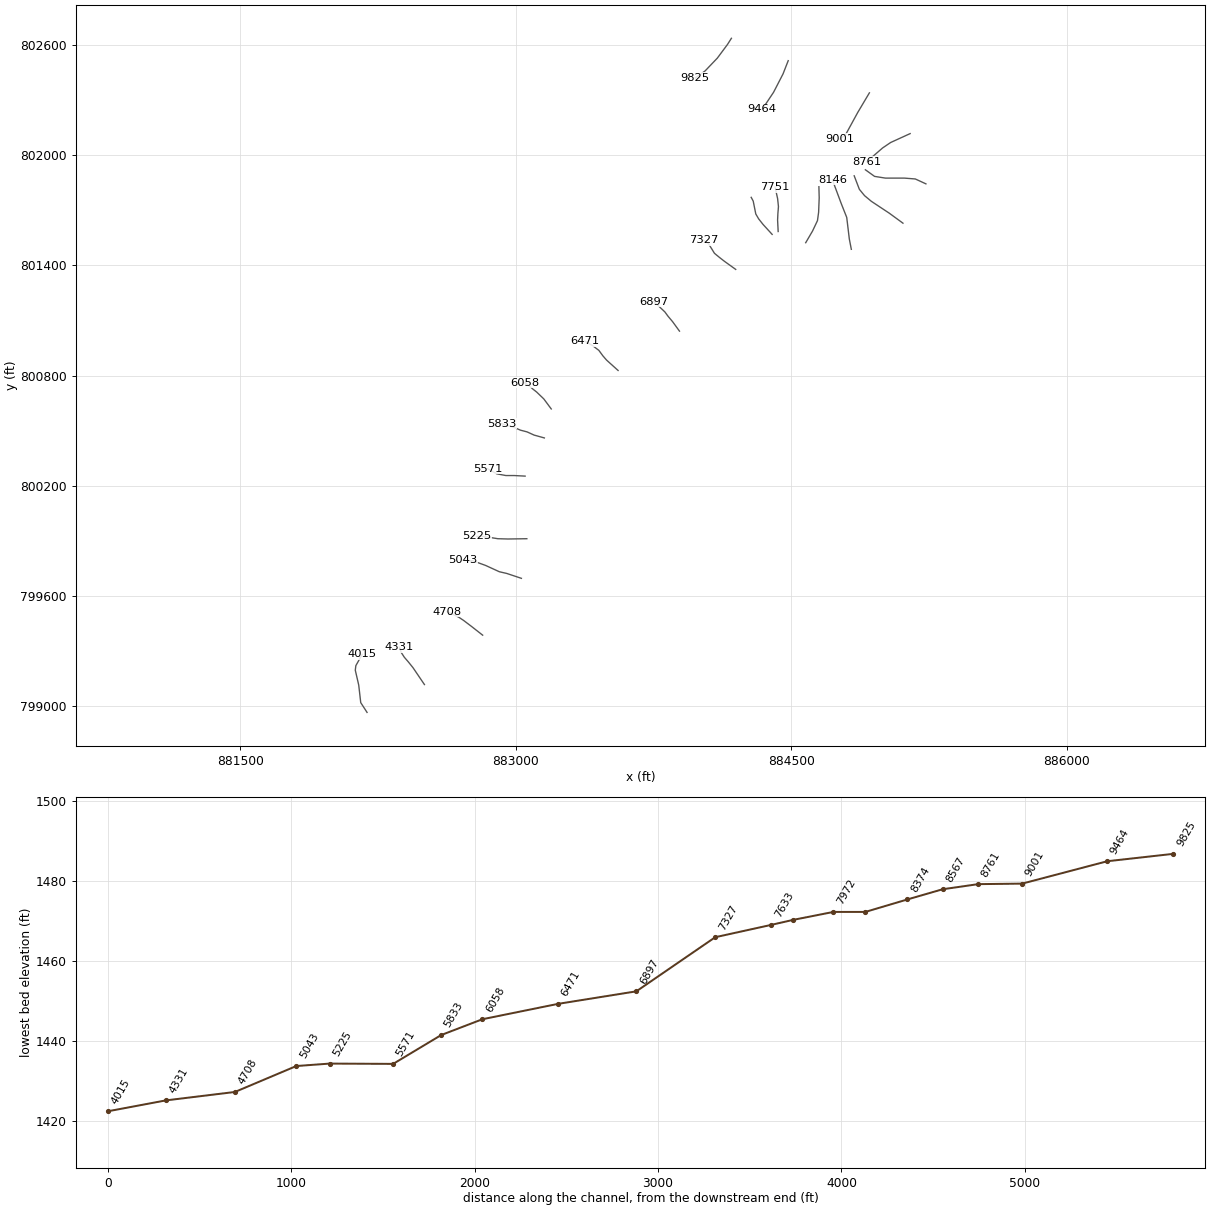
HEC-RAS study lds_big_laurel_crk.prj: lds_big_laurel_crk

--- lds_big_laurel_crk.g20 (geometry) --- (continued)

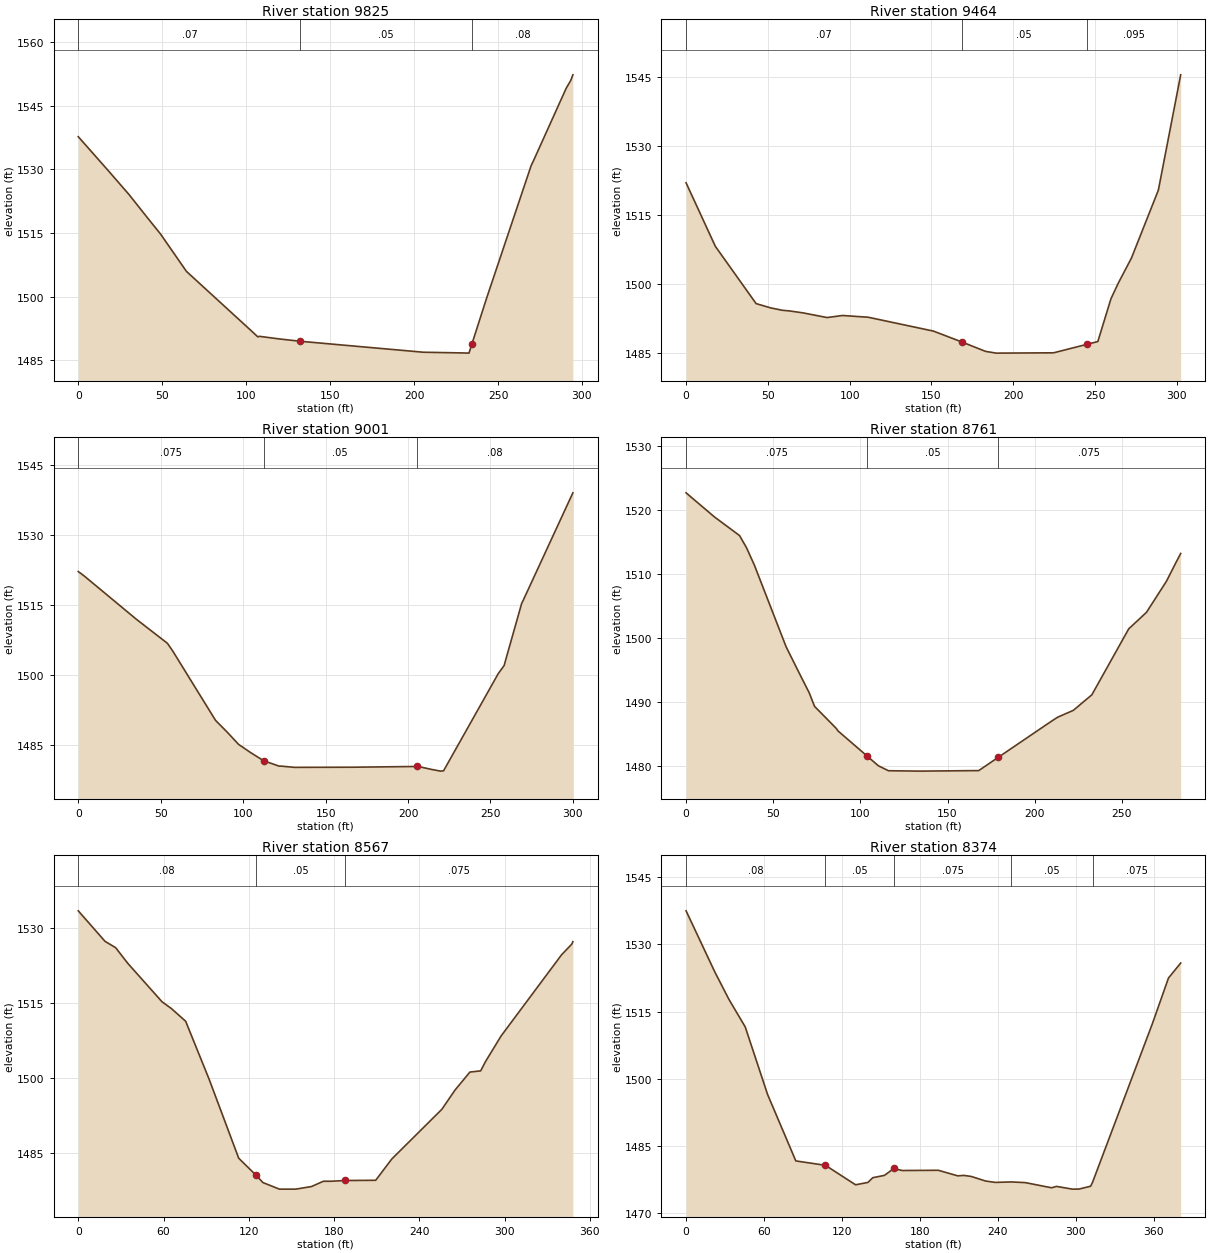
Type RM Length L Ch R = 1 ,9825    ,342.63,360.94,398.23
BEGIN DESCRIPTION:
9747.495
END DESCRIPTION:
XS GIS Cut Line= 5
  884174.6961335  802635.8434871  884152.8207666  802601.4690811
  884098.1328615   802528.031593  884030.9459172  802457.7188648
  883977.8209041  802420.2186748
#Sta/Elev= 22
       0 1537.73   18.53 1529.43   30.39 1524.02   40.74 1518.85   49.02 1514.78
   64.44 1505.98   101.9  1492.4  106.96 1490.55  107.93 1490.68  119.45 1490.08
  132.31 1489.51  205.53 1486.93     2211486.821  229.56 1486.76  232.71 1486.72
  234.471488.893   243.2 1499.67  269.72  1530.9  271.35 1532.26  290.62 1549.16
   293.3 1550.97  294.59 1552.31
#Mann= 3 , 0 , 0
       0     .07       0  132.31     .05       0  234.47     .08       0
Bank Sta=132.31,234.47
Exp/Cntr=0.3,0.1

Type RM Length L Ch R = 1 ,9464    ,468.76,463.79,477.22
BEGIN DESCRIPTION:
9386.553
END DESCRIPTION:
XS GIS Cut Line= 4
  884484.0709088  802513.9686377  884455.9460223  802442.0940416
   884404.382877  802342.0935349  884341.8835845   802248.343572
#Sta/Elev= 22
       0 1521.98   17.89 1508.14   42.81 1495.66   51.68 1494.73    58.9  1494.2
   63.07 1494.07   71.34 1493.65   86.22 1492.62   95.64 1493.07  111.33 1492.69
  151.22 1489.67  168.52 1487.31   183.1 1485.25  189.66 1484.87  224.68 1484.94
  244.831486.766  251.72 1487.39  259.74 1496.71  264.14 1500.06  272.29  1505.6
  288.73 1520.38  302.37  1545.5
#Mann= 3 , 0 , 0
       0     .07       0  168.52     .05       0  244.83    .095       0
Bank Sta=168.52,244.83
Exp/Cntr=0.3,0.1

Type RM Length L Ch R = 1 ,9001    ,292.43,239.71,198.62
BEGIN DESCRIPTION:
8922.760
END DESCRIPTION:
XS GIS Cut Line= 4
  884926.2587291  802338.9687752  884862.1955204  802231.1568811
  884798.1333359  802113.9686592  884766.8836896  802087.4066648
#Sta/Elev= 30
       0 1522.16      .3 1522.06    1.71 1521.72    4.04 1521.08   35.22 1511.91
   54.05 1506.75   57.16 1505.16   83.27 1490.18   90.37 1487.64   97.19 1485.04
  104.49 1483.27  112.35 1481.53  121.78 1480.35  123.26 1480.35  131.11 1480.09
  166.33 1480.12   205.5 1480.28  206.33 1480.27   214.1 1479.66   219.7 1479.28
  221.01 1479.33  221.53 1479.34  254.69 1500.21   258.3 1501.98  258.96 1502.84
  268.94 1515.34  269.13 1515.48  269.26 1515.55  270.02 1516.11  299.98 1539.07
#Mann= 3 , 0 , 0
       0    .075       0  112.35     .05       0   205.5     .08       0
Bank Sta=112.35,205.5
Exp/Cntr=0.3,0.1

Type RM Length L Ch R = 1 ,8761    ,240.81,193.98,129.45
BEGIN DESCRIPTION:
8683.054
END DESCRIPTION:
XS GIS Cut Line= 5
   885148.133061  802117.0944432  885041.8830347  802068.6560577
  884998.1333251  802038.9693034  884951.2588557  801998.3443536
  884912.1957737  801963.9689234
#Sta/Elev= 30
       0 1522.73   16.26 1518.96   30.67 1516.04   34.64 1514.15   39.12 1511.45
   57.36 1498.64   64.78 1494.57   70.58 1491.45    73.7 1489.29    85.9 1485.91
   86.46 1485.73   87.09 1485.46     1041481.475   110.3 1479.99  116.09 1479.21
  116.77 1479.21  133.96 1479.15  166.09 1479.23  167.85 1479.23     1711479.814
     1791481.297  207.34 1486.55  213.04 1487.58  222.14 1488.67  232.76  1491.1
  253.91 1501.43  264.07 1504.01  275.54 1508.88  280.86 1511.74  283.71 1513.23
#Mann= 3 , 0 , 0
       0    .075       0     104     .05       0     179    .075       0
Bank Sta=104,179
Exp/Cntr=0.3,0.1

Type RM Length L Ch R = 1 ,8567    ,239.71,192.58,123.63
BEGIN DESCRIPTION:
8489.078
END DESCRIPTION:
XS GIS Cut Line= 6
  885234.0706124  801843.6569659  885176.2579475  801870.2189604
  885116.8834147  801874.9066122  885013.7581483  801874.9066122
  884954.3836155  801884.2819157  884904.3833622  801920.2192138
#Sta/Elev= 28
       0 1533.34   18.82 1527.26   26.32 1525.99   34.79 1522.89   58.97  1515.2
   65.44 1513.88   75.56 1511.33   91.99 1499.83  112.88 1484.03  124.72 1480.74
  129.92 1479.18  141.48 1477.87  153.04 1477.87  164.13 1478.39  172.46 1479.44
  178.01 1479.44  187.72 1479.59  209.25 1479.63  220.51 1483.85   255.8 1493.78
  265.06 1497.61  275.53  1501.2  283.11 1501.44  286.42 1503.25  297.54 1508.42
  340.04 1524.58   347.2  1526.7  347.99 1527.19
#Mann= 3 , 0 , 0
       0     .08       0  124.72     .05       0  187.72    .075       0
Bank Sta=124.72,187.72
Exp/Cntr=0.3,0.1

Type RM Length L Ch R = 1 ,8374    ,289.55,228.74,122.3
BEGIN DESCRIPTION:
8296.501
END DESCRIPTION:
XS GIS Cut Line= 6
  885109.0710032  801629.5940214  885034.0706232  801684.2819265
  884937.1959004   801748.344111  884899.6957104  801779.5937573
  884871.5708239  801813.9691875  884843.4459375  801887.4066755
#Sta/Elev= 30
       0 1537.51   22.14 1523.85   32.99 1517.73   45.55 1511.57   62.79 1496.46
   84.51 1481.62  107.32 1480.64  130.52 1476.29  140.03 1476.82  143.73 1477.87
  152.71 1478.39  160.02 1479.93  166.38 1479.48  194.27 1479.53  209.23 1478.28
  213.87 1478.39  219.71 1478.14  230.63 1477.13  238.14 1476.82  250.43 1476.93
  261.29 1476.77  281.44 1475.62  285.23 1475.93  297.39 1475.32   302.5 1475.33
   311.5 1475.97     313 1476.86  359.08 1512.32  371.44 1522.49  380.84 1525.84
#Mann= 5 ,-1 , 0
       0     .08       0  107.32     .05       0  160.02    .075       0
  250.43     .05       0     313    .075       0
Bank Sta=107.32,160.02
Exp/Cntr=0.3,0.1

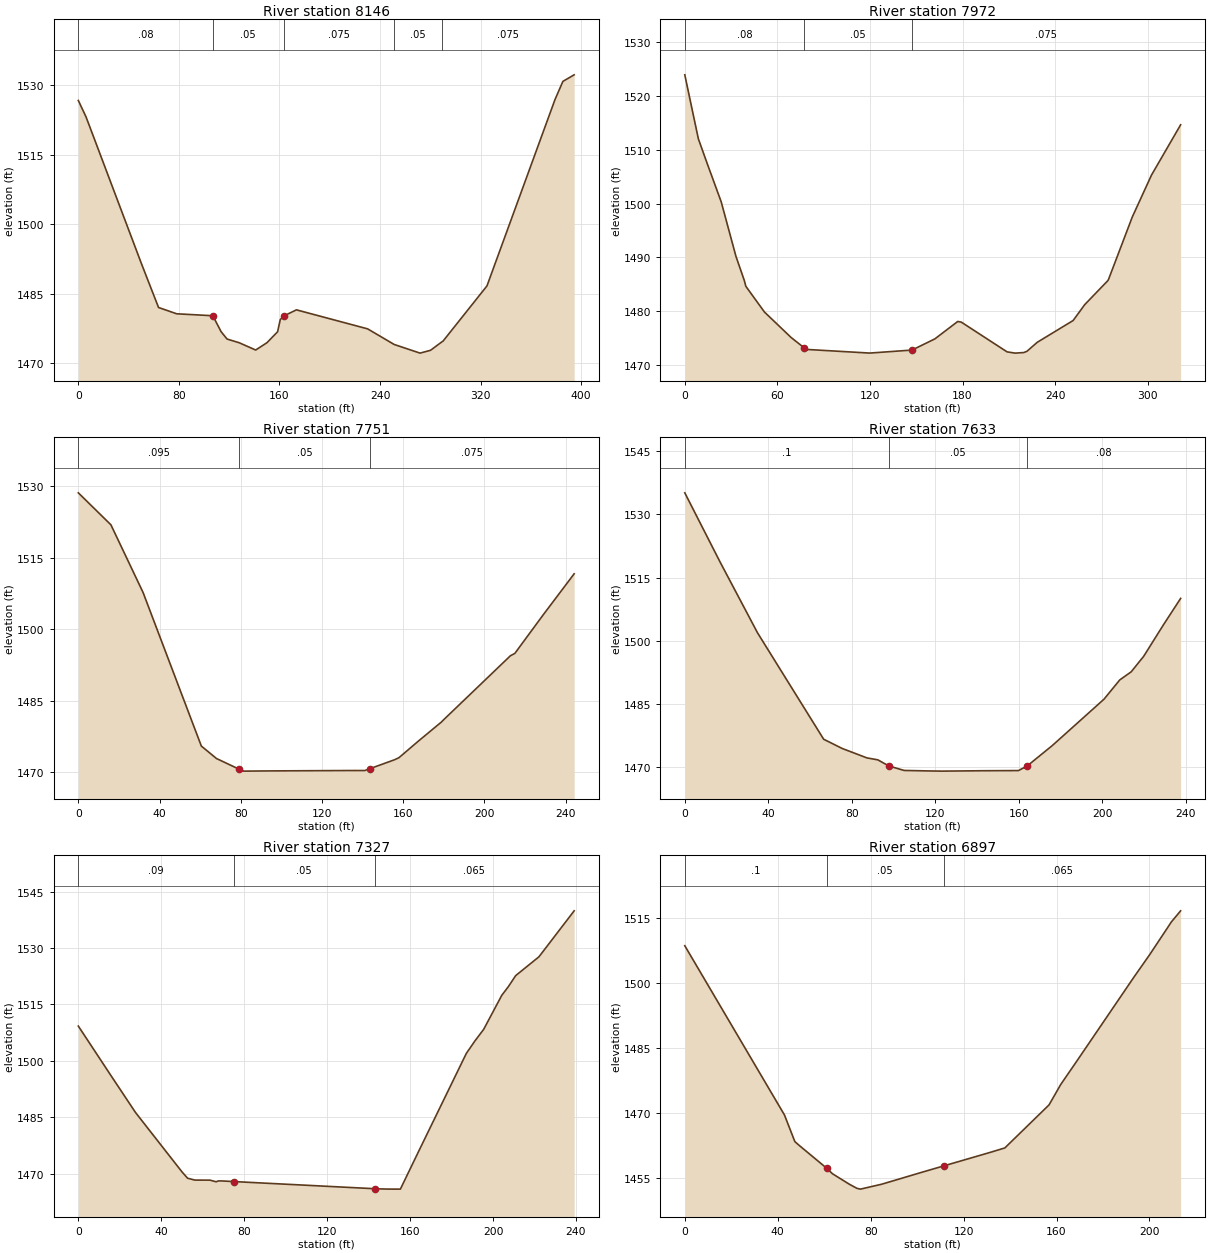
Type RM Length L Ch R = 1 ,8146    ,225.6,173.68,101.8
BEGIN DESCRIPTION:
8067.767
END DESCRIPTION:
XS GIS Cut Line= 5
  884827.8211143  801487.4066971  884816.8829188    801543.65647
  884802.8209877  801660.8436676  884773.1332092  801735.8440477
  884724.6958478  801865.5313086
#Sta/Elev= 25
       0 1526.67    6.15 1523.12   50.37 1491.38   63.81 1482.05   78.22 1480.69
  106.97 1480.27  113.61 1476.82  118.36 1475.24  127.87 1474.46  141.08 1472.88
  150.07 1474.46  158.52 1476.82  160.63 1479.44  163.43 1480.22  173.51 1481.54
  230.14 1477.44  251.31 1474.07  271.85 1472.21  280.18 1472.82  289.46 1474.69
  290.04 1474.77  325.07  1486.7  379.19 1526.87  385.48 1530.79  394.43  1532.2
#Mann= 5 ,-1 , 0
       0     .08       0  106.97     .05       0  163.43    .075       0
  251.31     .05       0  289.46    .075       0
Bank Sta=106.97,163.43
Exp/Cntr=0.3,0.1

Type RM Length L Ch R = 1 ,7972    ,186.41,221.18,227.5
BEGIN DESCRIPTION:
7894.085
END DESCRIPTION:
XS GIS Cut Line= 6
  884579.3837637  801523.3439951  884616.8829296  801587.4061796
  884643.4459482  801643.6569767  884649.6954678  801688.9685541
  884652.8212518  801767.0936939  884651.2583598  801828.0311186
#Sta/Elev= 28
       0 1523.94     8.8 1512.04   14.31 1507.62   23.58 1500.35   33.17 1490.19
   38.62 1485.67   39.55 1484.64   51.63 1479.85    68.9 1475.12   77.53 1473.16
   78.81  1472.9  119.84 1472.22  147.29 1472.78   162.1 1474.86   176.9 1478.09
  179.17 1477.98  208.86 1472.45  214.09 1472.21  219.74 1472.32  221.75 1472.55
  228.49 1474.23  251.69 1478.27  259.26 1481.24  274.23 1485.69  274.73 1485.98
  290.05 1497.52  302.48  1505.3  321.37 1514.65
#Mann= 3 , 0 , 0
       0     .08       0   77.53     .05       0  147.29    .075       0
Bank Sta=77.53,147.29
Exp/Cntr=0.3,0.1

Type RM Length L Ch R = 1 ,7751    ,71.89,117.47,133.36
BEGIN DESCRIPTION:
7672.903
END DESCRIPTION:
XS GIS Cut Line= 6
  884429.3830037  801584.2814198  884426.2582439  801646.7817365
  884427.8211359  801681.1561425  884430.9458957  801720.2192245
  884426.2582439  801763.9689341  884412.1963128  801826.4692508
#Sta/Elev= 23
       0 1528.64   16.06 1521.92   31.89 1507.72    60.6 1475.47   62.58 1474.78
   68.04 1472.86   78.93 1470.67   81.44 1470.21   96.16 1470.26   96.99 1470.26
  136.18 1470.34  141.07 1470.33  143.781470.748  154.48  1472.4  155.62 1472.57
  157.93 1473.03  167.55 1476.53   178.8  1480.5  180.18 1481.09  212.89 1494.45
  215.01 1494.92  228.93 1502.99  244.24 1511.64
#Mann= 3 , 0 , 0
       0    .095       0   78.93     .05       0  143.78    .075       0
Bank Sta=78.93,143.78
Exp/Cntr=0.3,0.1

Type RM Length L Ch R = 1 ,7633    ,291.42,306.19,338.7
BEGIN DESCRIPTION:
7555.435
END DESCRIPTION:
XS GIS Cut Line= 6
  884396.5704654  801568.6565967  884346.5712363  801623.3434776
  884323.1329774  801653.0312561  884307.5081543  801679.5942747
  884293.4462231  801749.9059788  884282.5080276  801770.2194779
#Sta/Elev= 24
       0 1535.14   16.79  1518.8   34.84 1501.86   66.53 1476.56    74.1 1474.69
   75.38 1474.37   87.28 1472.12   92.44 1471.67   97.71 1470.22  105.06 1469.14
  116.22 1469.03   123.1 1468.98  142.74 1469.07  159.81 1469.11   163.9 1470.16
  176.05 1475.06  200.79 1486.07  208.36 1490.66  213.87  1492.6  214.45 1492.96
  218.75 1495.62  219.74 1496.21  229.09 1503.61  237.52 1510.04
#Mann= 3 , 0 , 0
       0      .1       0   97.71     .05       0   163.9     .08       0
Bank Sta=97.71,163.9
Exp/Cntr=0.3,0.1

Type RM Length L Ch R = 1 ,7327    ,445.63,430.08,432.3
BEGIN DESCRIPTION:
7249.249
END DESCRIPTION:
XS GIS Cut Line= 6
  884198.1333682   801378.031911  884137.1959435  801421.7816206
   884109.071057  801443.6559633  884082.5080384  801465.5313302
  884049.6955001  801518.6563433  884023.1335056  801535.8440584
#Sta/Elev= 24
       0 1509.23   15.95  1495.9   27.57 1486.27   50.02 1470.46    52.7 1468.79
   56.25 1468.29   63.49 1468.28    66.5 1467.84   67.39 1468.05   68.52 1468.08
   75.02  1467.9  142.86    1466  145.06 1465.96  149.22  1465.9  155.33 1465.89
  164.44 1476.28  187.13 1501.96  191.27 1505.28   195.5 1508.36  204.21 1517.39
   207.5 1519.79  210.92 1522.64  222.16 1527.65  239.14 1539.87
#Mann= 3 , 0 , 0
       0     .09       0   75.02     .05       0  142.86    .065       0
Bank Sta=75.02,142.86
Exp/Cntr=0.3,0.1

Type RM Length L Ch R = 1 ,6897    ,421.1,425.9,419.67
BEGIN DESCRIPTION:
6819.168
END DESCRIPTION:
XS GIS Cut Line= 5
  883891.8833527   801042.094117  883854.3831627  801093.6562382
   883829.383036  801123.3440166  883812.1963451  801146.7812513
  883752.8207882  801203.0310243
#Sta/Elev= 24
       0 1508.49   42.91 1469.46   47.29 1463.44   47.56 1463.24   49.47 1462.35
   61.01 1457.22   63.58 1455.91   63.76 1455.85   70.83  1453.5   74.06 1452.56
   75.61 1452.37    82.3  1453.2   84.67 1453.49  102.57 1456.34  111.471457.726
  131.63 1460.87  137.76 1461.87  156.78 1471.79  161.82  1476.5  168.62  1481.8
  193.33 1501.26  200.11 1506.44  209.48 1514.01  213.42 1516.54
#Mann= 3 , 0 , 0
       0      .1       0   61.01     .05       0  111.47    .065       0
Bank Sta=61.01,111.47
Exp/Cntr=0.3,0.1

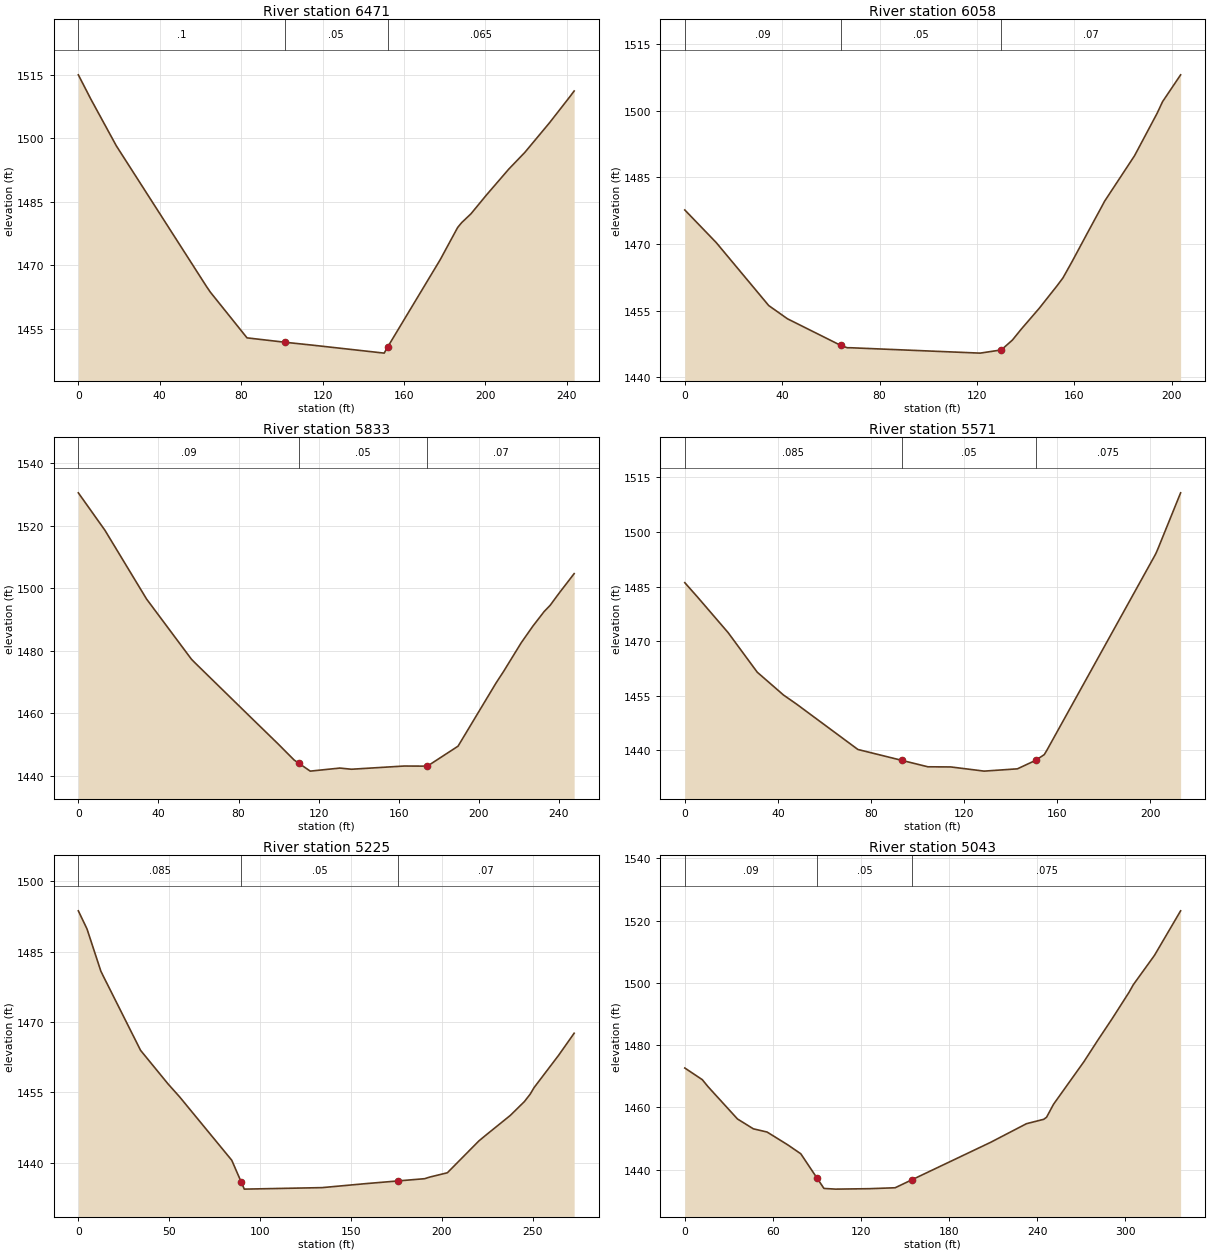
Type RM Length L Ch R = 1 ,6471    ,409.35,413.45,411.49
BEGIN DESCRIPTION:
6393.270
END DESCRIPTION:
XS GIS Cut Line= 6
  883557.5084507  800828.0311725   883495.008134  800884.2819696
  883474.6956591  800907.7192043  883452.8213164  800937.4069827
  883420.0087782  800962.4060852  883376.2580444  800987.4062119
#Sta/Elev= 23
       0 1515.02    6.19 1509.24   18.67 1498.24   63.04 1464.95   64.28 1464.08
   64.79 1463.71   82.88 1452.86   84.09 1452.79  101.51 1451.82   115.1 1451.13
  150.27 1449.25  151.98 1450.69  177.83 1471.35  186.36 1478.93  188.33 1480.08
  192.95 1482.19  193.23 1482.36  200.58 1486.65  211.54 1492.76  219.43 1496.71
  231.52 1503.69  241.82 1510.04  243.62  1511.2
#Mann= 3 , 0 , 0
       0      .1       0  101.51     .05       0  151.98    .065       0
Bank Sta=101.51,151.98
Exp/Cntr=0.3,0.1

Type RM Length L Ch R = 1 ,6058    ,188.21,224.64,247.06
BEGIN DESCRIPTION:
5979.817
END DESCRIPTION:
XS GIS Cut Line= 6
  883193.4457703  800618.6569039  883152.8208205  800673.3437848
  883113.7587626  800710.8439748  883091.8833958  800728.0316899
  883076.2585726  800742.0936211   883049.695554  800760.8442282
#Sta/Elev= 24
       0 1477.65   12.91  1470.3   34.48 1456.11   42.15 1453.14   64.01 1447.15
   66.75 1446.61   68.13 1446.61  121.29  1445.4  122.27 1445.48  129.97 1446.12
  134.58 1448.36   138.1 1450.75  145.58 1455.51  150.09 1458.64   152.8 1460.51
  155.31 1462.35   159.1 1466.07  165.46 1472.57  171.11 1478.28  172.41 1479.62
  184.74  1489.9     194 1499.45  196.23 1502.06  203.63 1508.09
#Mann= 3 , 0 , 0
       0     .09       0   64.01     .05       0  129.97     .07       0
Bank Sta=64.01,129.97
Exp/Cntr=0.3,0.1

Type RM Length L Ch R = 1 ,5833    ,244.49,261.8,265.7
BEGIN DESCRIPTION:
5755.179
END DESCRIPTION:
XS GIS Cut Line= 6
  883155.9455803  800460.8437322  883099.6958073  800476.4685554
  883062.1956173  800493.6562705  883026.2583193   800503.031574
   882993.445781  800517.0935052   882921.571185  800538.9688721
#Sta/Elev= 29
       0 1530.51    13.3 1518.51   34.08 1496.52    56.5 1477.25   58.38 1476.03
   86.31 1458.54   99.63 1450.24  107.75 1445.01  110.261443.901  115.81 1441.45
  130.62 1442.43  136.25 1442.06  136.33 1442.06  136.77 1442.07  160.35 1442.99
  162.73 1443.08  172.47 1443.05  174.09 1443.05  175.06 1443.36  189.61 1449.43
   208.6 1469.66  212.41  1473.4  221.19 1482.55  227.02 1487.88  232.62 1492.52
  235.63 1494.52  238.48 1497.01  240.29 1498.57   247.6 1504.65
#Mann= 3 , 0 , 0
       0     .09       0  110.26     .05       0  174.09     .07       0
Bank Sta=110.26,174.09
Exp/Cntr=0.3,0.1

Type RM Length L Ch R = 1 ,5571    ,343.92,346.54,354.29
BEGIN DESCRIPTION:
5493.381
END DESCRIPTION:
XS GIS Cut Line= 5
   883051.258446  800253.0313315  882991.8828891  800256.1560912
  882946.5713116  800256.1560912  882896.5710583  800265.5313948
  882846.5708049  800293.6562813
#Sta/Elev= 21
       0 1486.06    5.29 1482.24   18.61 1472.33   31.12 1461.45   42.39 1455.18
   48.07 1452.65   74.37  1440.2    93.31437.202  104.49 1435.43  104.77 1435.44
  114.26  1435.4  125.78 1434.48  128.56 1434.25  142.89 1434.88  150.73 1437.22
  154.45  1438.8  155.64 1440.09  202.15 1493.78   202.6 1494.39  203.32 1495.46
  213.01 1510.76
#Mann= 3 , 0 , 0
       0    .085       0    93.3     .05       0  150.73    .075       0
Bank Sta=93.3,150.73
Exp/Cntr=0.3,0.1

Type RM Length L Ch R = 1 ,5225    ,202.16,181.62,147.64
BEGIN DESCRIPTION:
5146.837
END DESCRIPTION:
XS GIS Cut Line= 5
  883060.6337495  799912.4069099   882957.508483  799910.8440179
  882902.8205779  799912.4069099  882824.6954381  799924.9069732
    882788.75814  799924.9069732
#Sta/Elev= 28
       0 1493.73    4.76 1489.88   12.45 1480.79   12.94 1480.44   13.48 1479.99
   34.27 1463.94   49.42 1456.76   55.78    1454   84.45 1440.48   89.661435.829
   91.35 1434.32  134.16 1434.64  157.85 1435.48  175.931436.069  190.69 1436.55
  193.02 1436.85  193.19 1436.86   193.4 1436.89  203.11 1437.81  220.49 1444.62
  223.95 1445.73  236.97 1449.81  237.72 1450.04  245.54 1453.02  248.76 1454.63
  250.81 1455.98  264.27 1462.85   272.9  1467.6
#Mann= 3 , 0 , 0
       0    .085       0   89.66     .05       0  175.93     .07       0
Bank Sta=89.66,175.93
Exp/Cntr=0.3,0.1

Type RM Length L Ch R = 1 ,5043    ,361.45,334.72,312.25
BEGIN DESCRIPTION:
4965.223
END DESCRIPTION:
XS GIS Cut Line= 6
   883030.945971  799696.7810734  882951.2579392   799723.344092
  882910.6329894  799732.7193956  882835.6336336  799767.0938016
  882766.8837973  799792.0939283  882710.6330002  799795.2186881
#Sta/Elev= 26
       0 1472.64   11.92 1468.89   15.75 1466.68   35.87 1456.26   46.71 1453.09
   56.04 1452.06   70.13 1447.94      79 1445.07      90  1437.3   94.78 1433.93
   102.7 1433.71  125.69 1433.85  143.26 1434.15     1551436.786  208.19 1448.73
   232.7 1454.74  244.45 1456.15  246.37 1456.81   251.1 1460.97  271.86  1474.7
  281.35 1481.62   291.2  1488.6  302.66 1497.06  305.44  1499.4  319.85 1508.83
  337.68 1523.16
#Mann= 3 , 0 , 0
       0     .09       0      90     .05       0     155    .075       0
Bank Sta=90,155
Exp/Cntr=0.3,0.1

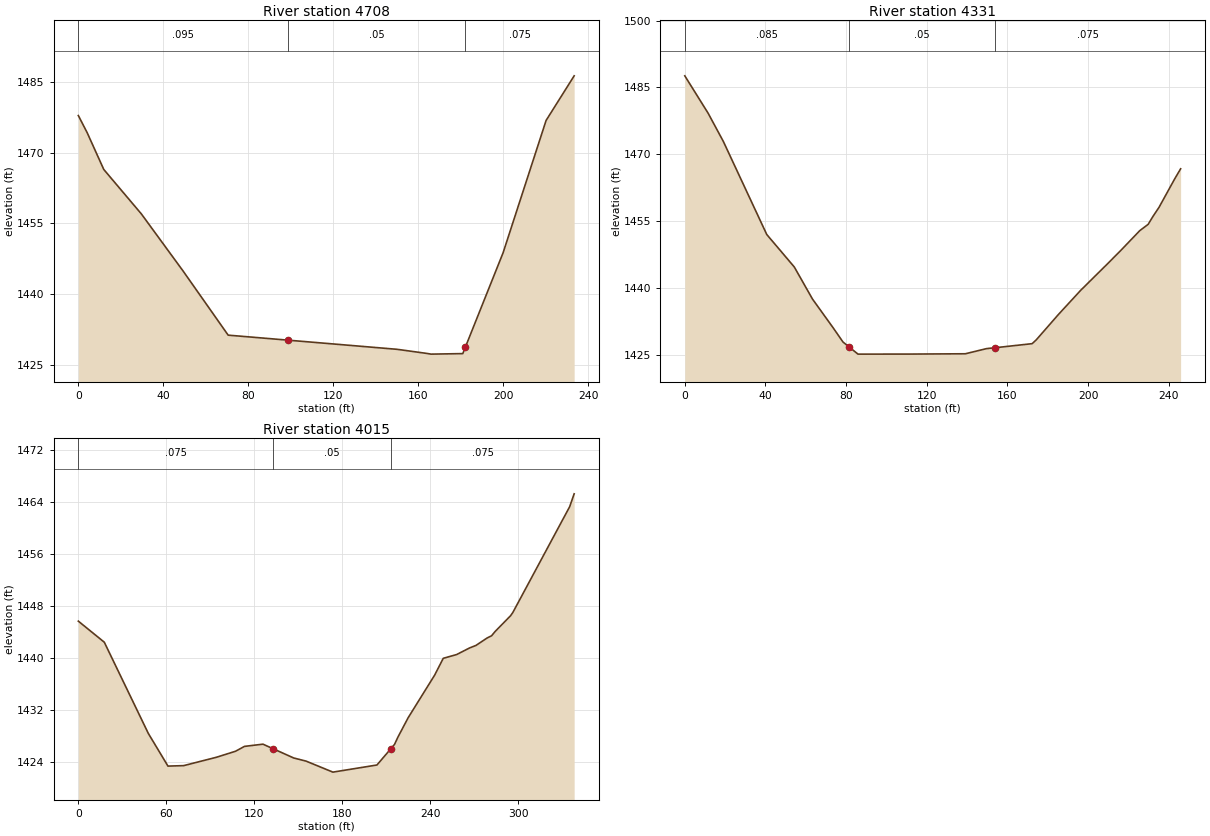
Type RM Length L Ch R = 1 ,4708    ,405.64,377.32,348.89
BEGIN DESCRIPTION:
4630.506
END DESCRIPTION:
XS GIS Cut Line= 5
  882820.0088105   799387.406298  882762.1961455  799432.7188996
   882716.883544  799467.0943298  882688.7586575  799485.8439128
  882626.2583408  799515.5316912
#Sta/Elev= 16
       0 1477.89    4.17 1474.24   11.97 1466.44   29.68 1456.99   49.23 1444.92
   70.51 1431.26   82.391430.812   98.731430.193  150.06 1428.25  164.13 1427.37
  165.97 1427.23  180.92 1427.34  182.151428.728   199.9 1448.76  220.13 1476.85
  233.33 1486.32
#Mann= 3 , 0 , 0
       0    .095       0   98.73     .05       0  182.15    .075       0
Bank Sta=98.73,182.15
Exp/Cntr=0.3,0.1

Type RM Length L Ch R = 1 ,4331    ,345.9,315.8,261.82
BEGIN DESCRIPTION:
4253.189
END DESCRIPTION:
XS GIS Cut Line= 6
  882502.8205994  799118.6564725  882440.3213069  799210.8435435
  882413.7582882  799243.6560817  882393.4458133  799267.0943406
  882376.2580982  799293.6563351  882366.8838189  799321.7812216
#Sta/Elev= 28
       0 1487.62   11.55 1479.24    19.1  1472.9   40.64 1451.99   54.32 1444.68
   63.32 1437.49   73.51 1431.07   78.45 1427.84   81.581426.696   85.89 1425.12
  111.38 1425.13  139.13  1425.2  140.21 1425.32  149.67 1426.36  153.59 1426.54
  172.26 1427.47  174.27 1428.31  184.61 1433.67  184.95 1433.85  196.22  1439.4
  209.57 1445.38  216.25 1448.42  225.63 1452.85  229.79 1454.27  232.15 1456.03
  235.18 1458.09  242.93 1464.46  245.89 1466.74
#Mann= 3 , 0 , 0
       0    .085       0   81.58     .05       0  153.59    .075       0
Bank Sta=81.58,153.59
Exp/Cntr=0.3,0.1

Type RM Length L Ch R = 1 ,4015    ,287.88,133.8,43.92
BEGIN DESCRIPTION:
3937.384
END DESCRIPTION:
XS GIS Cut Line= 6
  882190.3210643  798967.0938447  882155.9456341  799020.2188578
  882145.0084627  799115.5317128  882126.2578556  799196.7816124
  882129.3836396   799221.781739  882163.7580457  799282.7191637
#Sta/Elev= 30
       0 1445.68   17.72 1442.43   47.74 1428.37   61.14 1423.33   71.82  1423.4
   94.19 1424.69  107.25 1425.62  113.35 1426.37  125.96 1426.71  132.65 1426.03
  146.94 1424.58  155.33  1424.1  173.67  1422.4  203.71  1423.5  213.171426.003
  215.69 1426.67  218.05 1427.81  224.98 1430.78  243.08 1437.36  248.95 1439.95
  258.07 1440.53  267.03 1441.56  271.28 1441.94  278.92 1443.09  281.88 1443.42
  284.39  1444.1  294.85 1446.51  296.43 1447.02  335.19 1463.33  338.24 1465.31
#Mann= 3 , 0 , 0
       0    .075       0  132.65     .05       0  213.17    .075       0
Bank Sta=132.65,213.17
Exp/Cntr=0.3,0.1