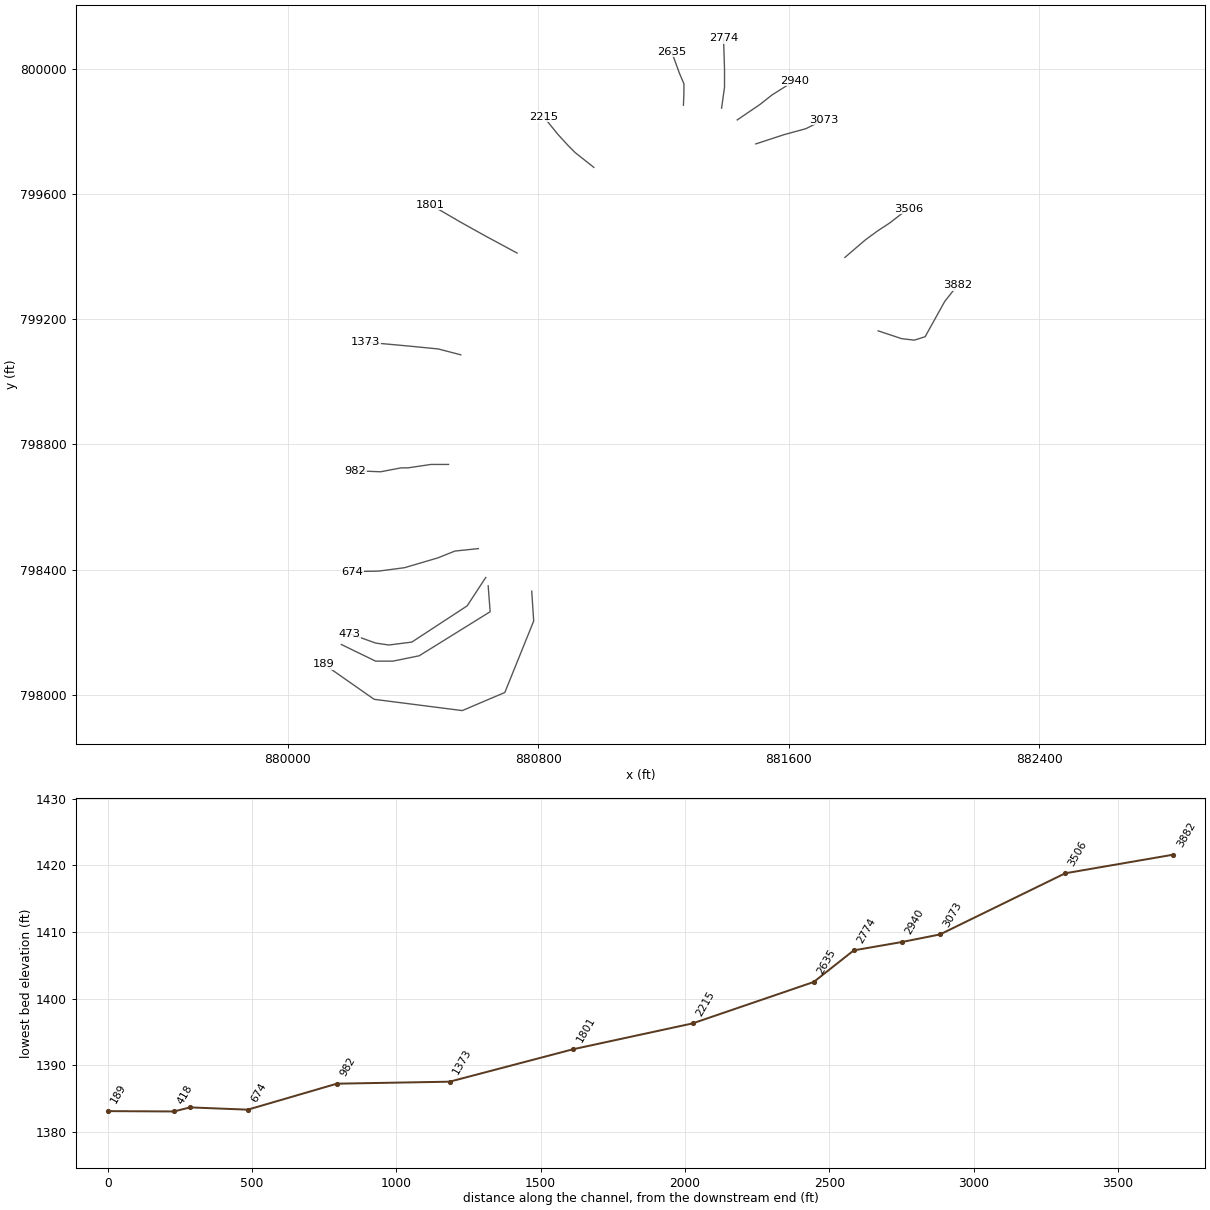
HEC-RAS study lds_big_laurel_crk.prj: lds_big_laurel_crk

--- lds_big_laurel_crk.g20 (geometry) --- (continued)

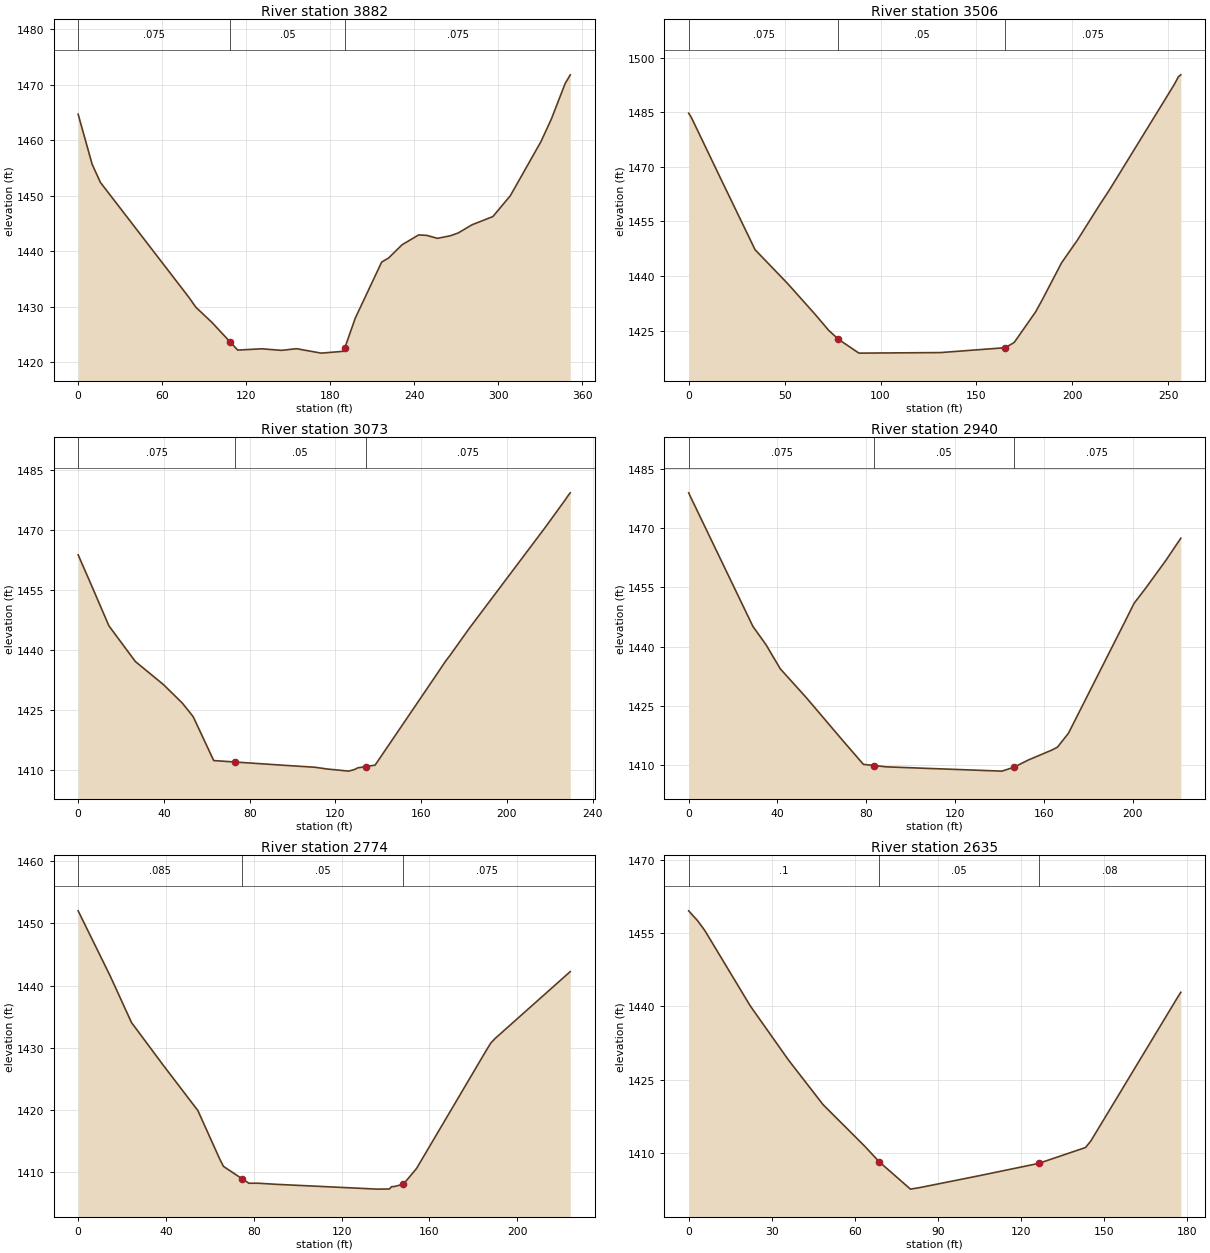
Type RM Length L Ch R = 1 ,3882    ,302.46,375.09,310.04
BEGIN DESCRIPTION:
3803.585
END DESCRIPTION:
XS GIS Cut Line= 6
  881885.6329166  799162.4061821  881960.6332966  799137.4060555
  882001.2582464  799132.7194279  882035.6336767  799143.6565992
  882098.1329692  799256.1561451   882138.757919  799307.7192904
#Sta/Elev= 30
       0 1464.71   10.02 1455.67   15.92 1452.41   79.06  1431.7   84.11 1429.89
   95.77 1427.11  108.561423.639  114.01 1422.16  131.19 1422.39  145.39 1422.11
  156.03 1422.41  173.67 1421.61  189.63 1421.94  190.44 1422.49     198 1427.92
  216.87 1438.04   221.8 1438.77  231.53 1441.18  243.31 1442.94   248.9 1442.86
  256.76 1442.32  266.02 1442.79  271.55 1443.29  281.46 1444.77  296.33 1446.25
  308.81 1450.02  330.65 1459.76  338.15 1463.87  347.95 1470.25  351.62 1471.82
#Mann= 3 , 0 , 0
       0    .075       0  108.56     .05       0  190.44    .075       0
Bank Sta=108.56,190.44
Exp/Cntr=0.3,0.1

Type RM Length L Ch R = 1 ,3506    ,447.49,433.87,406.19
BEGIN DESCRIPTION:
3428.492
END DESCRIPTION:
XS GIS Cut Line= 5
  881779.3828903  799396.7816016  881845.0079668  799453.0313745
  881885.6329166   799482.719153  881921.5712388  799506.1563877
  881982.5086635  799553.0318812
#Sta/Elev= 23
       0 1484.71    1.39 1483.55   16.11 1467.39   34.61 1447.22   51.64 1437.89
   65.65 1429.62   73.04 1425.04   78.09 1422.61   88.74 1418.81  131.28 1418.96
  164.97  1420.3  169.02 1421.52  169.81 1421.83  180.84 1430.13   184.2 1433.35
  194.39 1443.63  202.57  1449.8  214.08 1459.43  219.47 1463.76   250.3 1490.17
  253.22  1492.7   255.3 1494.74  256.54 1495.26
#Mann= 3 , 0 , 0
       0    .075       0   78.09     .05       0  164.97    .075       0
Bank Sta=78.09,164.97
Exp/Cntr=0.3,0.1

Type RM Length L Ch R = 1 ,3073    ,108.79,132.25,151.56
BEGIN DESCRIPTION:
2994.622
END DESCRIPTION:
XS GIS Cut Line= 4
  881495.0082417    799759.28139  881585.6334448  799788.9691685
  881654.3832811  799807.7187514  881710.6330541  799835.8436379
#Sta/Elev= 28
       0 1463.72    5.65  1456.8   14.36 1445.96   26.67 1437.05   39.83 1431.25
   48.58 1426.65   53.35 1423.46   53.88 1422.99   63.23 1412.27    73.11411.914
   95.36 1411.11  110.62 1410.59  116.12 1410.16  121.76 1409.87  126.14 1409.63
  128.78 1410.02  130.48 1410.46  134.091410.762  138.49 1411.13  166.62 1433.35
  171.43 1437.19  172.74 1438.11   173.4 1438.56  182.29 1445.25   217.9 1470.63
  226.87 1477.26  228.63 1478.63  229.51 1479.23
#Mann= 3 , 0 , 0
       0    .075       0    73.1     .05       0  134.09    .075       0
Bank Sta=73.1,134.09
Exp/Cntr=0.3,0.1

Type RM Length L Ch R = 1 ,2940    ,106.92,166.49,239.43
BEGIN DESCRIPTION:
2862.373
END DESCRIPTION:
XS GIS Cut Line= 4
   881435.633709  799835.8436379   881509.071197  799885.8438912
  881546.5703629  799915.5316697  881618.4459831  799960.8442713
#Sta/Elev= 23
       0 1478.97     .64 1478.19   28.93 1445.14   34.81 1440.52   41.27 1434.39
   52.78 1427.23   69.32 1416.29   78.69  1410.2    83.61409.905   88.84 1409.59
   89.16 1409.57  134.65 1408.62  141.05 1408.49  146.33 1409.44  153.02 1411.32
  163.63 1413.84  166.08 1414.56  171.03 1418.07  195.96 1445.78  200.62 1451.01
  205.47 1454.56  214.93 1461.87  221.64 1467.48
#Mann= 3 , 0 , 0
       0    .075       0    83.6     .05       0  146.33    .075       0
Bank Sta=83.6,146.33
Exp/Cntr=0.3,0.1

Type RM Length L Ch R = 1 ,2774    ,127.5,138.89,165.96
BEGIN DESCRIPTION:
2695.886
END DESCRIPTION:
XS GIS Cut Line= 4
  881385.6334556  799873.3438279  881395.0087592  799940.5317964
  881395.0087592  799998.3444613  881391.8829752  800096.7810518
#Sta/Elev= 24
       0 1452.04   14.59 1441.56   24.34 1434.03   25.74 1433.38   38.45 1427.33
   54.53 1419.89   64.48 1412.09   66.18 1410.91   67.84 1410.51   74.721408.899
   77.75 1408.19   82.03 1408.19   90.43 1408.01  125.65 1407.42  136.18 1407.24
  141.73 1407.26  142.82 1407.66  143.76 1407.64  148.11 1408.02  154.15 1410.58
  185.66 1429.44  187.88 1430.72  189.84 1431.47  224.14 1442.26
#Mann= 3 , 0 , 0
       0    .085       0   74.72     .05       0  148.11    .075       0
Bank Sta=74.72,148.11
Exp/Cntr=0.3,0.1

Type RM Length L Ch R = 1 ,2635    ,382.18,419.84,449.81
BEGIN DESCRIPTION:
2556.993
END DESCRIPTION:
XS GIS Cut Line= 5
  881263.7586062  799882.7191314   881265.320474  799920.2193215
   881265.320474  799951.4689677  881251.2585429  799984.2815059
  881226.2584162  800053.0313422
#Sta/Elev= 20
       0 1459.64    3.16 1457.65    4.98 1456.26    6.06 1455.38   22.24 1440.11
   35.83 1429.16   37.53  1427.9    48.5 1419.85   60.741412.894   63.65 1411.24
   68.78  1408.1   80.05 1402.49   83.55 1402.82  104.48  1405.2  126.29 1407.77
  143.23 1411.03  145.13 1412.35     153 1419.75   176.7 1442.08  177.64 1442.91
#Mann= 3 , 0 , 0
       0      .1       0   68.78     .05       0  126.29     .08       0
Bank Sta=68.78,126.29
Exp/Cntr=0.3,0.1

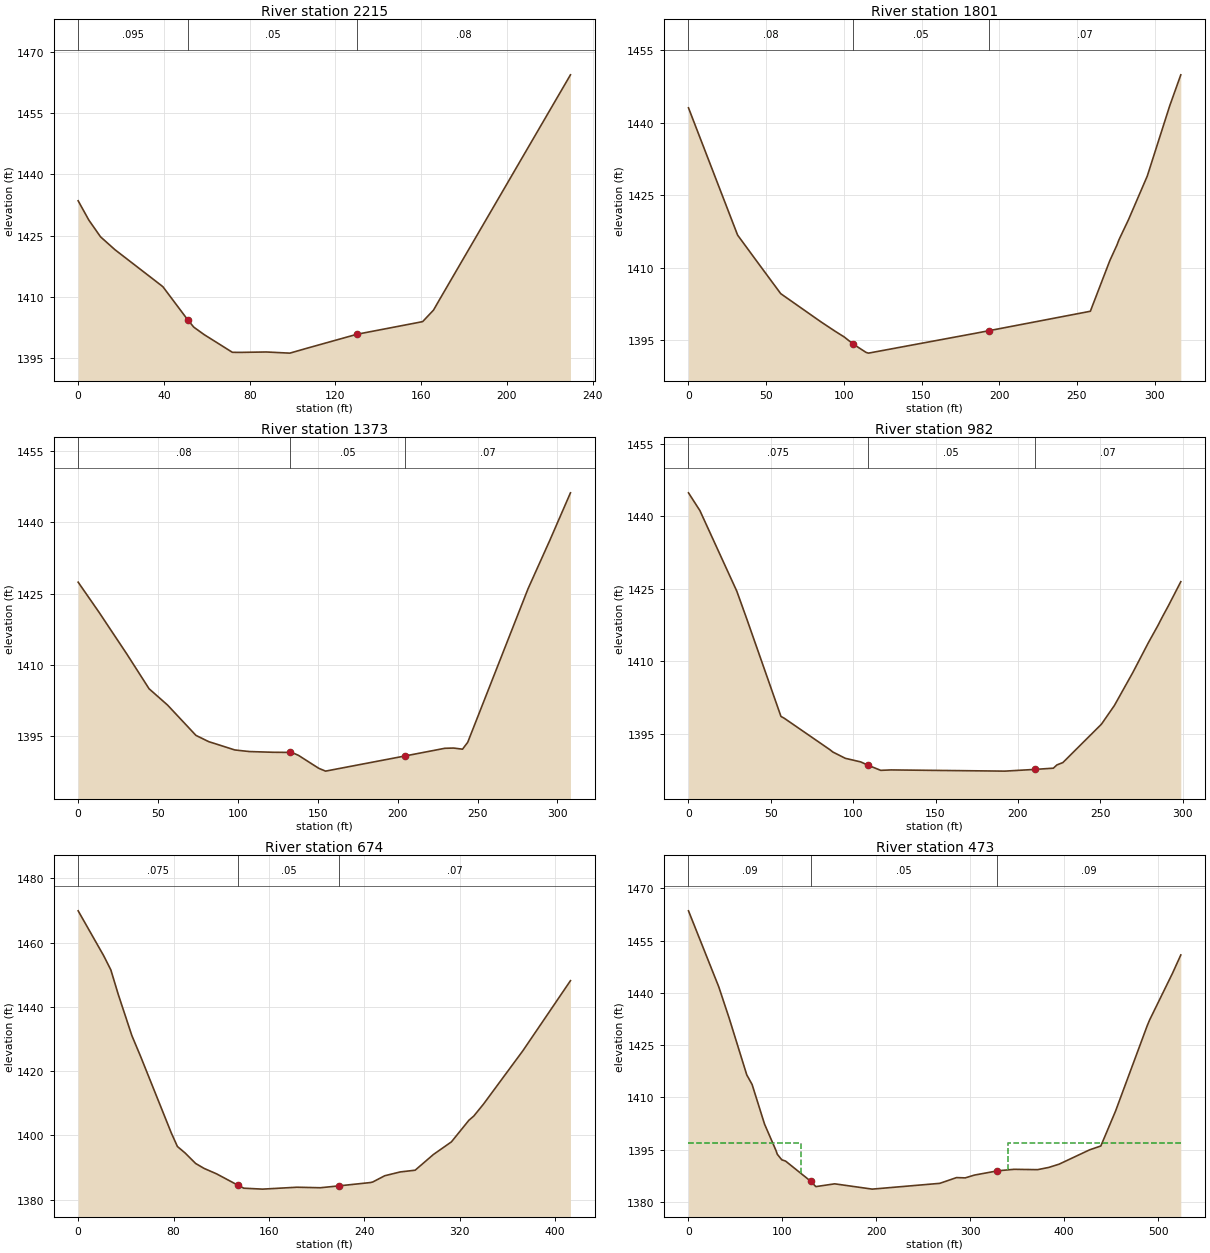
Type RM Length L Ch R = 1 ,2215    ,386.19,413.99,449.3
BEGIN DESCRIPTION:
2137.156
END DESCRIPTION:
XS GIS Cut Line= 5
  880977.8210656    799684.28101  880918.4455087  799731.1565036
   880896.571166  799753.0318705  880862.1957358  799790.5310363
  880816.8831342  799846.7818334
#Sta/Elev= 22
       0 1433.53    4.97 1428.82   10.43 1424.72   17.15 1421.57   38.87 1412.79
   39.61 1412.46   51.21 1404.36   53.96 1402.62   58.72 1400.82   71.95 1396.47
   73.16 1396.46   75.65 1396.45   87.77 1396.55   97.36  1396.3   98.78 1396.27
  106.58 1397.44  130.13 1400.89  157.46 1403.64  160.73 1403.98  165.78 1406.78
  168.68 1409.43  229.69 1464.33
#Mann= 3 , 0 , 0
       0    .095       0   51.21     .05       0  130.13     .08       0
Bank Sta=51.21,130.13
Exp/Cntr=0.3,0.1

Type RM Length L Ch R = 1 ,1801    ,381.37,427.79,479.39
BEGIN DESCRIPTION:
1723.170
END DESCRIPTION:
XS GIS Cut Line= 4
  880732.5084748  799410.8435327  880630.9461003  799465.5314379
  880549.6962007  799510.8440394  880455.9462377  799565.5319446
#Sta/Elev= 22
       0 1443.08   31.62 1416.78   45.02 1410.92   59.38 1404.68   85.42 1398.82
   94.31 1396.93  100.21 1395.74  106.13 1394.24  114.32 1392.54  115.35 1392.44
   115.9 1392.39  181.66 1396.31  183.44 1396.41  193.381397.024  258.69 1401.04
  271.23 1411.51  275.81 1414.72   277.1 1415.81  283.23 1419.95  295.34 1428.98
  309.78 1443.49  316.92  1449.9
#Mann= 3 , 0 , 0
       0     .08       0  106.13     .05       0  193.38     .07       0
Bank Sta=106.13,193.38
Exp/Cntr=0.3,0.1

Type RM Length L Ch R = 1 ,1373    ,364.31,390.82,410.8
BEGIN DESCRIPTION:
1295.376
END DESCRIPTION:
XS GIS Cut Line= 5
  880552.8209604  799085.8439343  880480.9463644  799104.5935172
  880401.2583326   799112.406953  880351.2580792  799117.0935806
  880248.1338369  799126.4688841
#Sta/Elev= 27
       0  1427.4   12.93 1421.12   30.44 1412.25    44.4  1404.9   55.94 1401.47
    73.7 1395.07   74.28 1394.97   81.85 1393.72   83.83 1393.52   98.02 1391.99
  104.96 1391.73  107.33 1391.65  121.85  1391.5  132.82 1391.47  135.35 1391.23
  137.92 1390.84  149.35 1388.38  150.62 1388.11  154.85 1387.52  204.57 1390.72
  229.53 1392.34  235.07 1392.39  240.55 1392.15  243.81  1393.6  281.54 1425.99
  295.27 1436.29  308.12 1446.26
#Mann= 3 , 0 , 0
       0     .08       0  132.82     .05       0  204.57     .07       0
Bank Sta=132.82,204.57
Exp/Cntr=0.3,0.1

Type RM Length L Ch R = 1 ,982     ,284.56,308.57,322.02
BEGIN DESCRIPTION:
904.5599
END DESCRIPTION:
XS GIS Cut Line= 6
  880513.7578785  798735.8442092  880457.5081055  798735.8442092
  880384.0706175  798724.9060137  880362.1962748  798724.9060137
  880296.5711983  798712.4069745  880216.8831665  798715.5317343
#Sta/Elev= 26
       0  1444.9    6.91 1441.23   29.36  1424.5   35.42 1418.74   56.15 1398.56
   58.24 1398.16   86.05 1391.62   87.55  1391.2    95.2 1389.88  104.58 1389.13
  108.81 1388.47  116.73 1387.38  122.92 1387.47  192.12 1387.22  210.341387.577
  221.55 1387.83  223.72 1388.51  227.31 1388.99  250.72 1396.94  258.59 1400.81
  269.91 1407.73   279.3 1413.88  285.02 1417.39  287.49 1419.03  291.44 1421.52
  298.93 1426.48
#Mann= 3 , 0 , 0
       0    .075       0  108.81     .05       0  210.34     .07       0
Bank Sta=108.81,210.34
Exp/Cntr=0.3,0.1

Type RM Length L Ch R = 1 ,674     ,168.96,200.42,228.7
BEGIN DESCRIPTION:
595.9945
END DESCRIPTION:
XS GIS Cut Line= 6
  880609.0707334  798467.0943837  880534.0703534  798459.2819721
  880479.3834724  798437.4066052  880373.1334461   798406.156959
  880290.3206545  798395.2187634  880205.9459951  798393.6568956
#Sta/Elev= 30
       0 1469.85   21.38 1455.92   27.41  1451.5   33.64 1443.87   45.03 1431.08
    52.5 1424.48   78.15 1400.78   83.26 1396.58   89.71 1394.56   98.51 1391.31
  105.59 1389.77  116.01 1388.09  134.31 1384.48  138.95 1383.61  154.71 1383.32
  183.49 1383.91  203.17 1383.75   218.91384.336  245.07 1385.36  247.14 1385.54
  257.18 1387.48  270.09 1388.66  282.69  1389.2  298.02 1394.09  313.11 1398.01
  327.83 1404.75  331.87 1406.03   340.1 1409.79  373.07 1426.35  412.99 1448.13
#Mann= 3 , 0 , 0
       0    .075       0  134.31     .05       0   218.9     .07       0
Bank Sta=134.31,218.9
Exp/Cntr=0.5,0.3

Type RM Length L Ch R = 1 ,473     ,64.2,55.67,50.17
BEGIN DESCRIPTION:
384.8104
END DESCRIPTION:
XS GIS Cut Line= 6
  880632.5079681  798374.9062885  880573.1334354  798284.2810854
  880396.5706808  798168.6567797  880323.1331928  798159.2814762
   880280.945351  798165.5309958  880198.1335836  798195.2187742
#Sta/Elev= 30
       0 1463.57    32.3  1441.7   43.41 1432.66   62.04 1416.47   67.72 1413.71
   80.95 1402.34   93.28 1394.67   94.52 1393.68   99.32 1392.08  103.37 1391.71
  130.18 1385.91  135.56 1384.38  155.65 1385.18  195.64 1383.66  267.53 1385.32
  285.33 1386.97  294.59 1386.89  304.39 1387.69  328.75  1388.9  346.51 1389.35
  371.61 1389.25  383.51 1389.89   394.5 1390.82   427.1 1394.95  438.98 1396.05
  454.59 1406.04  488.43 1430.64  490.91 1432.24  515.25 1445.63   524.1  1450.9
#Mann= 3 , 0 , 0
       0     .09       0  130.18     .05       0  328.75     .09       0
#XS Ineff= 2 , 0
       0     120    1397     340       0    1397
Permanent Ineff=
       F       F
Bank Sta=130.18,328.75
Exp/Cntr=0.5,0.3

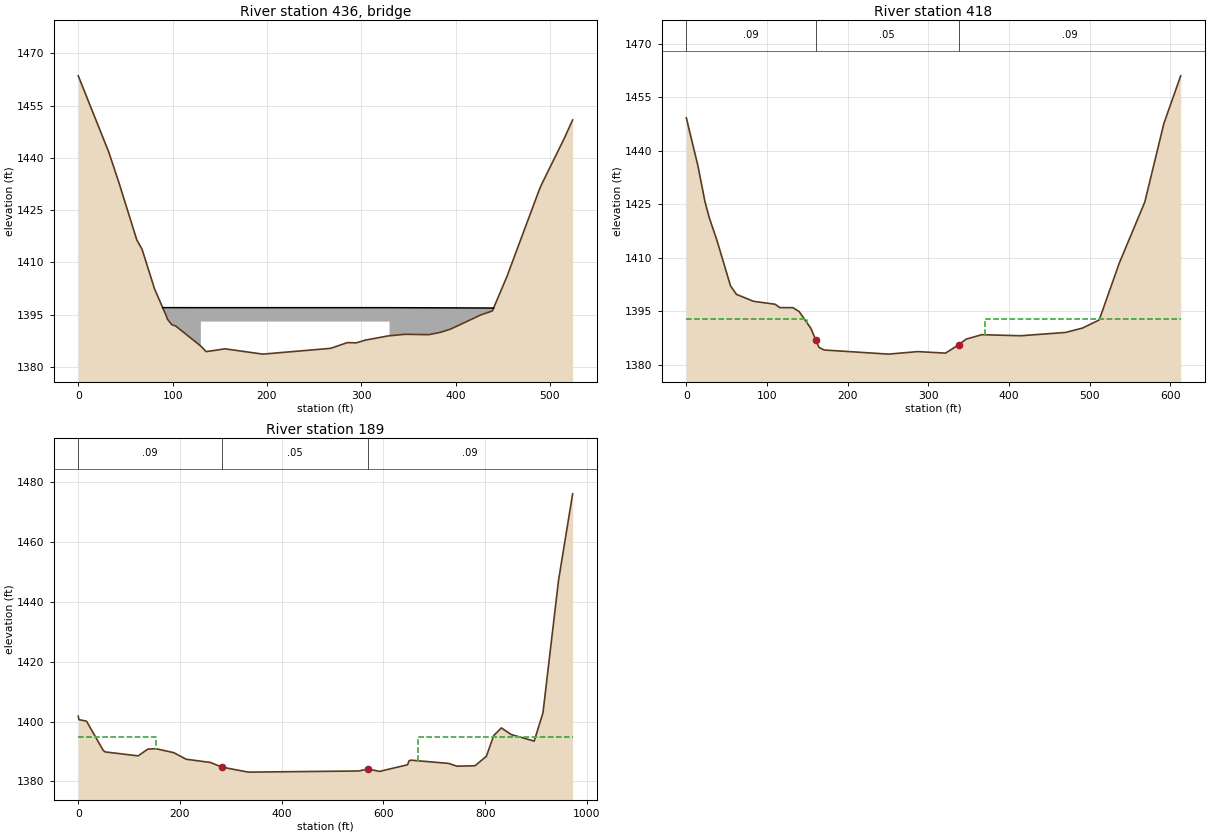
Type RM Length L Ch R = 3 ,436     ,,,
BEGIN DESCRIPTION:
349.81  FBSTR_1524  RR - No Access / Photo / Pier Data
END DESCRIPTION:
Bridge Culvert--1,0,-1,-1, 0
Deck Dist Width WeirC Skew NumUp NumDn MinLoCord MaxHiCord MaxSubmerge Is_Ogee
21,32,3,0, 7, 7, , , 0.95, 0, 1,1,,
   89.52     130     130     230     330     330  440.31
 1397.01    1397    1397    1397    1397    1397  1396.9
                    1393    1393    1393
  110.07     160     160     260     360     360   518.4
 1397.03    1397    1397    1397    1397    13971396.918
                    1393    1393    1393
BR Coef=-1 , 0 , 0 ,, 0 ,,,0.8,0,,0,
WSPro=,,,, 1 ,,,, 0 ,,,, 0 ,,,,-1 ,-1 ,-1 , 0 , 0 , 0 , 0 , 0
BC Design=,, 0 ,, 0 ,,,,,,

Type RM Length L Ch R = 1 ,418     ,243.88,229.17,98.01
BEGIN DESCRIPTION:
322.0774
END DESCRIPTION:
XS GIS Cut Line= 6
  880640.3203796  798348.3442941  880646.5709234  798265.5315025
  880420.0079155   798124.906046  880335.6332561   798107.719355
   880280.945351   798107.719355  880171.5705649  798160.8443682
#Sta/Elev= 30
       0 1449.28   14.47 1435.77   23.07 1425.83   28.64 1421.14   37.82 1415.04
   54.87 1402.13   62.19  1399.8   83.41 1397.85  110.07 1397.03  115.83 1396.09
  132.08 1396.08  139.86 1394.98  154.23 1390.33  160.581386.969  164.45 1384.92
  170.78 1384.21  250.67 1383.05  286.88 1383.76  321.17 1383.33  337.32 1385.63
   346.8 1387.26  366.31  1388.5  414.27  1388.2  470.03 1389.13  491.09 1390.36
  511.73 1392.64  536.41 1408.47  568.17 1425.66  591.87 1447.71  612.69 1461.06
#Mann= 3 , 0 , 0
       0     .09       0  160.58     .05       0  337.32     .09       0
#XS Ineff= 2 , 0
       0     150    1393     370       0    1393
Permanent Ineff=
       F       F
Bank Sta=160.58,337.32
Exp/Cntr=0.5,0.3

Type RM Length L Ch R = 1 ,189     ,281.51,188.43,357.53
BEGIN DESCRIPTION:
112.9680
END DESCRIPTION:
XS GIS Cut Line= 6
  880779.3829442   798331.156579  880785.6334879   798235.843724
  880693.4453928  798007.7188483  880557.5086122  797949.9061834
  880276.2587234  797985.8434814   880115.320792  798098.3440515
#Sta/Elev= 30
       0  1401.8    1.31 1400.64   16.21 1400.12   49.07 1390.36   53.09 1389.85
  117.67 1388.53  136.88 1390.79  152.83 1390.93  187.97 1389.59  212.22 1387.41
  260.21 1386.32  281.83  1384.8  334.34  1383.1  551.79 1383.48  569.28 1384.16
  592.35 1383.34  647.69 1385.57  650.58 1386.92  654.69 1387.09  728.74    1386
   744.3 1385.09   780.2 1385.23  802.58  1388.4  817.14 1395.35  831.99 1397.87
   851.5 1395.65  896.56 1393.46  913.86 1402.89   944.4 1447.07  972.22 1476.06
#Mann= 3 , 0 , 0
       0     .09       0  281.83     .05       0  569.28     .09       0
#XS Ineff= 2 , 0
       0  152.83    1395   667.4       0    1395
Permanent Ineff=
       F       F
Bank Sta=281.83,569.28
Exp/Cntr=0.3,0.1
Stream Node=Big_Laurel_Creek,Main_Branch     , 0 , 0 ,Upstream end
Stream Node=Big_Laurel_Creek,Main_Branch     , 0 , 1 ,Downstream end

Chan Stop Cuts=-1
Use User Specified Reach Order=0
User Specified Reach Order=Big_Laurel_Creek,Main_Branch