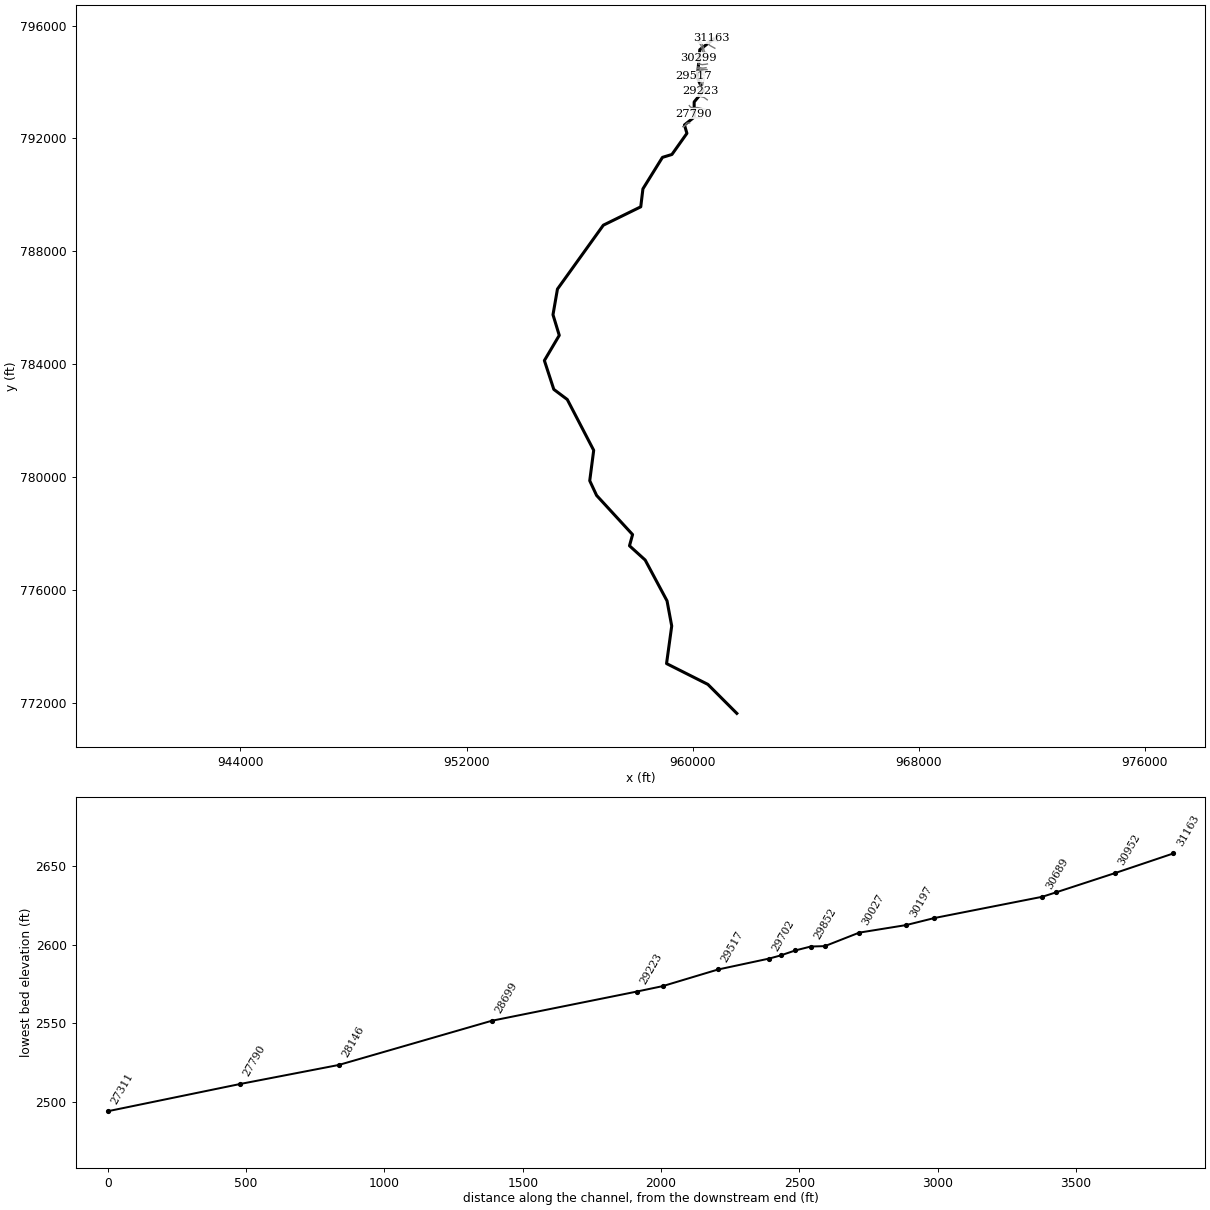
--- lds_california_crk.prj (project) ---

Proj Title=California Creek Limited Detail Study
Current Plan=p02
Default Exp/Contr=0.3,0.1
English Units
Geom File=g01
Flow File=f02
Plan File=p02
Y Axis Title=Elevation
X Axis Title(PF)=Main Channel Distance
X Axis Title(XS)=Station
BEGIN DESCRIPTION:
California Creek
END DESCRIPTION:
DSS Export Rating Curves= 0
DSS Export Rating Curve Sorted= 0
DSS Export Volume Flow Curves= 0
DXF OffsetX= 0
DXF OffsetY= 0
DXF ScaleX= 1
DXF ScaleY= 10

--- lds_california_crk.p02 (plan) ---

Plan Title=Floodway Run
Program Version=3.13
Short Identifier=Floodway
Geom File=g01
Flow File=f02
Subcritical Flow
K Sum by GR= 0
Std Step Tol= 0.01
Critical Tol= 0.01
Num of Std Step Trials= 20
Max Error Tol= 0.3
Flow Tol Ratio= 0.001
Split Flow NTrial= 30
Split Flow Tol= 0.02
Split Flow Ratio= 0.02
Log Output Level= 0
Friction Slope Method= 0
Unsteady Friction Slope Method= 2
Unsteady Bridges Friction Slope Method= 1
Parabolic Critical Depth
Global Vel Dist= 0 , 0 , 0
Global Log Level= 0
CheckData=True
Encroach Param=-1 ,10,10, 2
Encroach River=California Creek
Encroach Reach=Reach-1
Encroach Node=31163
       1    4976 5013.12
Encroach Node=30952
       1 4986.17  5017.6
Encroach Node=30739
       1    4972 5019.36
Encroach Node=30689
       1    4978 5014.73
Encroach Node=30299
       1    4903  5045.4
Encroach Node=30197
       1 4982.79 5011.05
Encroach Node=30027
       1 4987.54  5020.8
Encroach Node=29903
       1  4991.5  5006.6
Encroach Node=29852
       1  4992.4    5004
Encroach Node=29796
       1  4983.5 5012.99
Encroach Node=29743
       1 3483.77    3547
Encroach Node=29702
       1 3492.33 3545.66
Encroach Node=29517
       1 4991.71    5009
Encroach Node=29317
       1 4990.31 5007.26
Encroach Node=29223
       1 4991.42 5014.51
Encroach Node=28699
       4      .7
Encroach Node=28146
       1    4981 5059.63
Encroach Node=27790
       1 4977.73 5075.74
Encroach Node=27311
       1    4950  5021.7
Encroach Node=27267
       1 4972.08 5016.11
Encroach Node=26908
       1 4985.92  5058.4
Encroach Node=26456
       1 4983.92  5016.2
Encroach Node=25980
       1 4985.57  5020.4
Encroach Node=25893
       1 4982.58  5018.9
Encroach Node=25265
       1  4928.7 5065.03
Encroach Node=24376
       1  4920.5 5016.86
Encroach Node=23932
       1  3814.5  3855.6
Encroach Node=23818
       1  3819.2 3884.23
Encroach Node=23706
       1 4986.54 5039.74
Encroach Node=23632
       1  4990.7    5106
Encroach Node=23584
       1 4984.58    5108
Encroach Node=22911
       1  4937.6  5048.5
Encroach Node=22131
       1    4920  5021.9
Encroach Node=22107
       1    4945    5011
Encroach Node=21863
       1  4814.8 5019.94
Encroach Node=21722
       1    4949  5029.5
Encroach Node=21651
       1  4963.4  5015.6
Encroach Node=21303
       1  4907.4  5069.3
Encroach Node=21066
       1  290.77  462.52
BEGIN DESCRIPTION:
Floodway Run
END DESCRIPTION:
Computation Interval=1HOUR
Output Interval=1HOUR
Run HTab= 0
Run UNet= 0
Run PostProcess= 0
UNET Theta= 1
UNET Theta Warmup= 1
UNET ZTol= 0.02
UNET ZSATol= 0.05
UNET MxIter= 20
UNET MaxInSteps= 0
UNET DtIC= 0
UNET DtMin= 0
UNET MaxCRTS= 20
UNET WFStab= 2
UNET SFStab= 1
UNET WFX= 1
UNET SFX= 1
UNET DSS MLevel= 4
UNET DZMax Abort= 100
UNET Convert EG Bridges=-1
UNET Use Existing IB Tables=-1
UNET Froude Reduction=False
UNET Froude Limit= 1
UNET Froude Power= 10
Instantaneous Interval=1HOUR
Write IC File= 0
Echo Input=False
Echo Output=False
Write Detailed= 0
Detailed Automatic Start=False, 10

--- lds_california_crk.f02 (steady flow) ---

Flow Title=Floodway
Program Version=3.13
Number of Profiles= 2
Profile Names=100-year,100-FW
River Rch & RM=California Creek,Reach-1         ,31163
     820     820
River Rch & RM=California Creek,Reach-1         ,30299
    1540    1540
River Rch & RM=California Creek,Reach-1         ,28699
    1620    1620
River Rch & RM=California Creek,Reach-1         ,23932
    1920    1920
River Rch & RM=California Creek,Reach-1         ,21066
    2490    2490
Boundary for River Rch & Prof#=California Creek,Reach-1         , 1
Up Type= 0
Dn Type= 1
Dn Known WS=2350.262
Boundary for River Rch & Prof#=California Creek,Reach-1         , 2
Up Type= 0
Dn Type= 1
Dn Known WS=2350.302
DSS Import GetInterval= 0
DSS Import GetPeak= 0
DSS Import FillOption= 0

--- lds_california_crk.g01 (geometry) ---

Geom Title=Existing Conditions
Program Version=3.13

River Reach=California Creek,Reach-1
Reach XY= 30
       960750.44       795526.87        960258.1       795144.46
       960170.82       794150.98       960378.83       793685.51
       960058.82       793294.22       960058.82       792756.03
        959715.1       792479.87       959801.71       792182.15
       959271.22       791434.05       958935.61        791331.2
       958244.88       790216.09       958167.95       789579.71
       956843.55       788929.25        955219.4       786665.83
       955061.41       785756.98       955283.63       785026.94
       954756.71       784134.44       955090.25       783112.85
       955567.47       782754.23       956502.37       780954.75
       956361.84       779877.23       956604.99        779356.4
       957878.65       777970.05       957769.28        777572.6
       958324.49       777068.09       959098.19        775621.3
       959264.14       774731.11         959081.        773400.3
       960543.57       772663.25       961568.63       771636.07

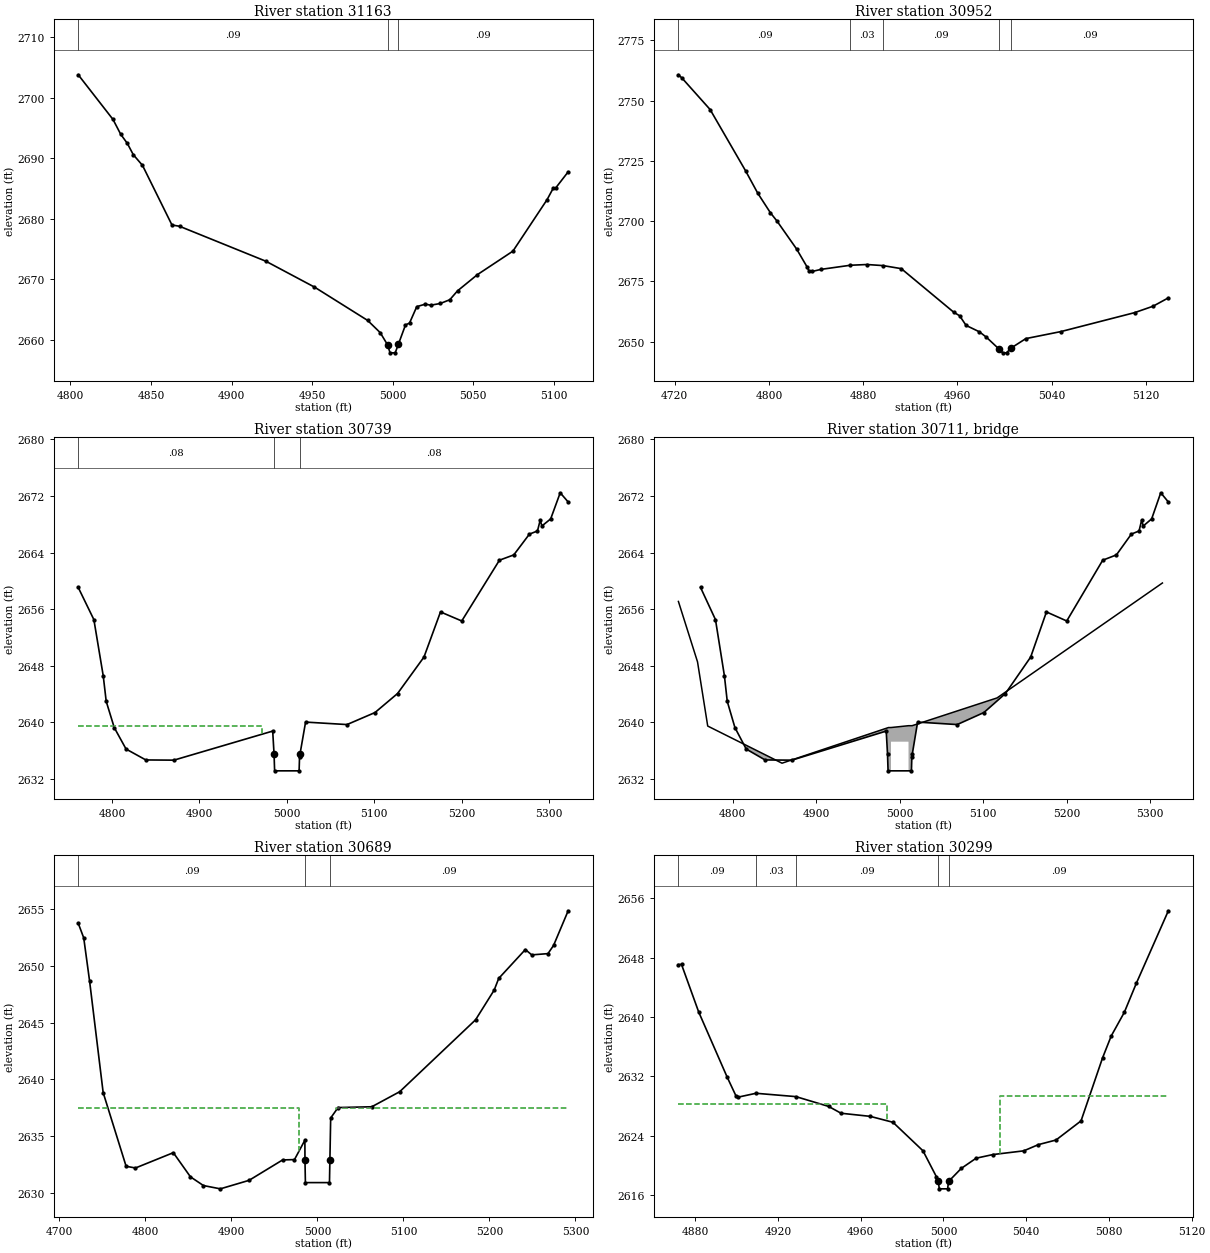
Type RM Length L Ch R = 1 ,31163   ,211,211,211
BEGIN DESCRIPTION:
xs 1
END DESCRIPTION:
XS GIS Cut Line= 6
       960898.39       795428.16       960848.15       795456.95
       960797.91       795463.73       960720.58       795460.34
       960683.32        795470.5       960665.26       795547.84
#Sta/Elev= 30
  4804.8 2703.83  4826.4 2696.44  4831.2 2693.98  4835.3 2692.48    4839 2690.61
  4844.7 2688.85    4863 2678.99  4867.7 2678.78  4921.3    2673  4951.5 2668.72
  4984.5 2663.21  4992.3 2661.19  4996.9 2659.16  4998.4 2657.85  5001.6 2657.85
 5003.54 2659.23    5008 2662.47  5010.5 2662.77    5015 2665.49  5020.3  2665.9
  5023.7 2665.73  5029.6 2666.01  5035.5 2666.63  5040.3  2668.1  5052.7 2670.79
  5074.7 2674.67  5095.9 2683.18  5099.8 2685.11  5101.3 2685.13    5109 2687.78
#Mann= 3 ,-1 , 0
  4804.8     .09       0  4996.9     .05       0 5003.54     .09       0
Bank Sta=4996.9,5003.54
Exp/Cntr=0.3,0.1

Type RM Length L Ch R = 1 ,30952   ,213,213,213
BEGIN DESCRIPTION:
xs2
END DESCRIPTION:
XS GIS Cut Line= 6
        960791.3       795196.87       960624.84       795288.91
       960557.71       795343.42       960551.22       795358.53
       960555.22       795423.35       960573.63       795477.77
#Sta/Elev= 30
  4723.2 2760.76  4726.3 2759.37  4750.1 2746.34  4780.2  2720.9  4790.6 2711.55
  4801.3 2703.47  4806.8 2700.09  4823.5 2688.45  4832.6 2680.82  4834.1 2679.24
  4836.6 2679.13  4844.4 2680.02  4869.1 2681.72  4883.2 2682.02  4896.7 2681.58
  4912.3 2680.31  4956.8 2662.23  4961.8 2660.75  4967.3 2656.75  4978.6 2654.09
  4984.5 2651.86 4994.82 2647.13  4998.4 2645.37  5001.6 2645.37  5005.4 2647.34
    5018 2651.28  5047.9 2654.21  5110.2 2662.04  5125.9 2664.71  5138.9 2668.18
#Mann= 5 ,-1 , 0
  4723.2     .09       0  4869.1     .03       0  4896.7     .09       0
 4994.82     .05       0  5005.4     .09       0
Bank Sta=4994.82,5005.4
Exp/Cntr=0.5,0.3

Type RM Length L Ch R = 1 ,30739   ,50,50,50
BEGIN DESCRIPTION:
xs3
END DESCRIPTION:
XS GIS Cut Line= 6
       960473.59       795044.82       960420.77       795059.23
       960389.56       795207.28       960344.75       795335.32
       960299.93       795408.15        960209.5       795505.78
#Sta/Elev= 30
  4761.4 2659.07  4779.3 2654.52    4790 2646.58  4793.4 2642.97  4802.6 2639.26
  4816.1 2636.23  4838.7 2634.69  4870.8 2634.66  4983.8 2638.77 4985.35 2635.51
    4986 2633.15    5014 2633.15  5014.5 2635.15 5015.01 2635.51  5021.4 2640.04
  5068.8 2639.69  5100.8 2641.39  5126.6 2644.08  5156.8 2649.23  5175.7 2655.61
    5200 2654.33  5243.1 2662.92  5259.5 2663.67  5277.4 2666.61  5286.6 2667.05
  5289.7 2668.57  5291.7 2667.76  5301.7 2668.76  5312.6 2672.45  5321.7 2671.15
#Mann= 3 ,-1 , 0
  4761.4     .08       0 4985.35     .05       0 5015.01     .08       0
#XS Ineff= 2 , 0
       0    4972 2639.53    5028       0 2639.93
Permanent Ineff=
       F       F
Bank Sta=4985.35,5015.01
Exp/Cntr=0.5,0.3

Type RM Length L Ch R = 3 ,30711   ,,,
BEGIN DESCRIPTION:
xs4
Structure ID: SR 1348
Approximate Survey Structure
END DESCRIPTION:
Bridge Culvert--1,0,-1,-1, 0
Deck Dist Width WeirC Skew NumUp NumDn MinLoCord MaxHiCord MaxSubmerge Is_Ogee
17.5,21,3,0, 12, 12, , , , 0, 1,1,,
  4734.9  4757.8    4770    4859  4986.5  4989.5  4989.5  5010.5  5010.5  5014.8
  5116.6  5314.6
 2657.09 2648.55 2639.48 2634.23 2639.27 2639.27 2639.27 2639.53 2639.53 2639.53
 2643.46  2659.7
  2610.3  2610.3  2610.3  2610.3  2610.3  2610.3 2637.27 2637.27  2610.3  2610.3
  2610.3  2610.3
  4734.9  4757.8    4770    4859  4986.5  4989.5  4989.5  5010.5  5010.5  5014.8
  5116.6  5314.6
 2657.09 2648.55 2639.48 2634.23 2639.27 2639.27 2639.27 2639.53 2639.53 2639.53
 2643.46  2659.7
  2610.3  2610.3  2610.3  2610.3  2610.3  2610.3 2637.27 2637.27  2610.3  2610.3
  2610.3  2610.3
BR Coef= 1 , 1 , 0 ,1.25, 0 ,,,0.8,0,2,0,
WSPro=,,,, 1 ,,,, 0 ,,,, 0 ,,,,-1 ,-1 ,-1 , 0 , 0 , 0 , 0 , 0
BC Design=,, 0 ,, 0 ,,,,,,
BC HTab HWMax=2672.47

Type RM Length L Ch R = 1 ,30689   ,390,390,390
BEGIN DESCRIPTION:
101
END DESCRIPTION:
XS GIS Cut Line= 6
       960454.81       795004.87       960390.71       795022.95
       960362.77       795080.48       960331.54       795223.48
        960288.8       795318.81        960172.1       795466.74
#Sta/Elev= 30
  4721.8 2653.76  4728.2 2652.47    4735 2648.67  4750.8 2638.82  4777.5 2632.32
  4788.4 2632.17  4832.4 2633.52  4852.3 2631.39  4867.4 2630.62  4887.1 2630.33
  4920.5 2631.08  4959.5 2632.88  4973.3 2632.91  4985.4 2634.62  4985.5 2632.88
    4986 2630.88    5014 2630.88  5014.5 2632.88  5015.4 2636.58    5024  2637.5
  5063.2 2637.57  5095.7  2638.9  5183.9 2645.24  5205.6 2647.87  5210.8 2648.89
  5241.8 2651.44  5249.2 2650.97  5268.1 2651.08  5274.6  2651.8  5291.6 2654.86
#Mann= 3 ,-1 , 0
  4721.8     .09       0  4985.5     .05       0  5014.5     .09       0
#XS Ineff= 2 , 0
       0    4978 2637.43    5022       0 2637.43
Permanent Ineff=
       F       F
Bank Sta=4985.5,5014.5
Exp/Cntr=0.5,0.3

Type RM Length L Ch R = 1 ,30299   ,102,102,102
BEGIN DESCRIPTION:
xs6
END DESCRIPTION:
XS GIS Cut Line= 5
       960424.06       794912.98       960327.31       794881.33
       960290.69       794874.55       960261.75       794869.58
       960193.49       794865.51
#Sta/Elev= 30
  4871.9 2647.07  4873.4 2647.09  4881.7 2640.68  4895.4 2631.94  4899.8 2629.32
  4900.6 2629.19  4909.4 2629.72  4928.7 2629.27  4944.5 2627.95  4950.5 2627.03
  4964.6 2626.61  4975.6 2625.81  4990.1 2621.97  4996.6 2618.47  4997.5 2617.84
    4998 2616.84    5002 2616.84  5002.5 2617.84  5008.6 2619.59  5015.8 2620.97
  5023.9 2621.46  5038.8 2621.96  5045.9  2622.8  5054.4 2623.42  5066.5    2626
  5076.9 2634.49  5081.1 2637.45  5087.4 2640.62  5093.2 2644.53  5108.7 2654.32
#Mann= 5 ,-1 , 0
  4871.9     .09       0  4909.4     .03       0  4928.7     .09       0
  4997.5     .04       0  5002.5     .09       0
#XS Ineff= 2 , 0
       0  4972.5  2628.3  5027.5       0 2629.42
Permanent Ineff=
       F       F
Bank Sta=4997.5,5002.5
Exp/Cntr=0.5,0.3

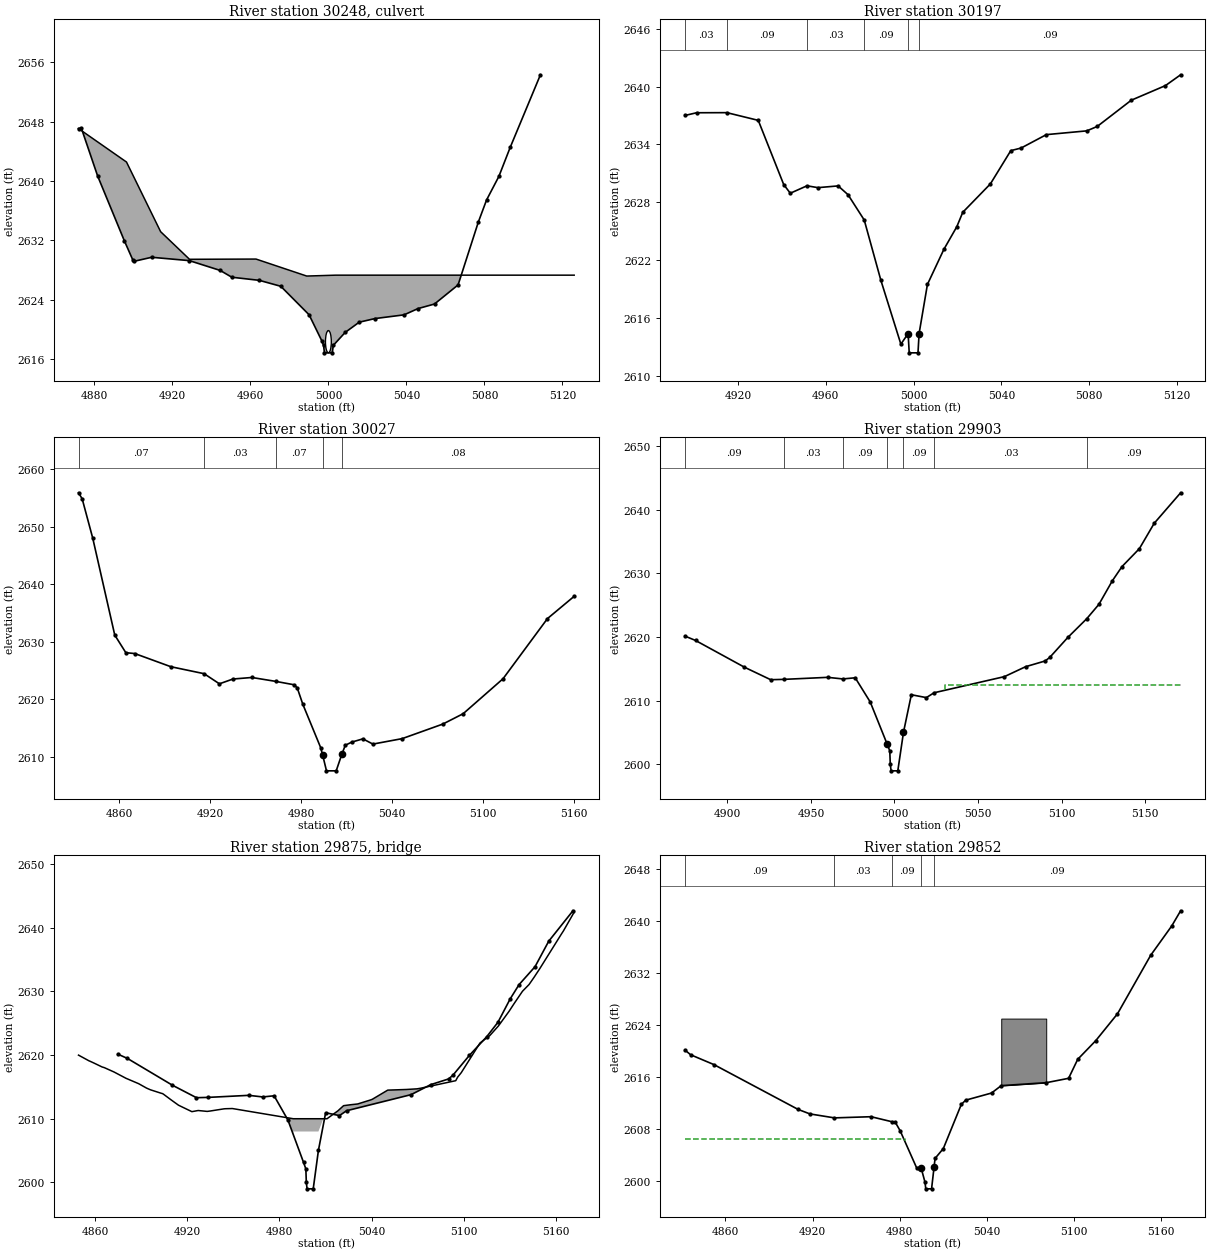
Type RM Length L Ch R = 2 ,30248   ,,,
BEGIN DESCRIPTION:
xs7
Structure ID: Unknown Bridge
Approximate Survey Structure
END DESCRIPTION:
Bridge Culvert--1,0,-1,-1, 0
Deck Dist Width WeirC Skew NumUp NumDn MinLoCord MaxHiCord MaxSubmerge Is_Ogee
26,50,3,0, 11, 11, , , , 0, 1,1,,
  4871.9  4896.5    4914  4928.8  4962.9  4988.9  5003.7  5005.1  5071.3  5083.9
    5126
 2647.07 2642.56 2633.17 2629.45 2629.48 2627.19 2627.31 2627.31 2627.31 2627.31
 2627.31
 2592.37 2592.37 2592.37 2592.37 2592.37 2592.37 2592.37 2592.37 2592.37 2592.37
 2592.37
  4871.9  4896.5    4914  4928.8  4962.9  4988.9  5003.7  5005.1  5071.3  5083.9
    5126
 2647.07 2642.56 2633.17 2629.45 2629.48 2627.19 2627.31 2627.31 2627.31 2627.31
 2627.31
 2592.37 2592.37 2592.37 2592.37 2592.37 2592.37 2592.37 2592.37 2592.37 2592.37
 2592.37
Culvert=1,3,,50,0.027,0.5,1,2,1,2616.84,5000,2612.37,5000,Culvert #1  , 0 ,26
Culvert Bottom n=0.027
BC Design=,, 0 ,, 0 ,,,,,,
BC HTab HWMax=2654.32

Type RM Length L Ch R = 1 ,30197   ,170,170,170
BEGIN DESCRIPTION:
xs8
END DESCRIPTION:
XS GIS Cut Line= 5
       960431.75       794796.34       960358.05       794780.51
       960329.22       794779.48       960294.31       794774.18
       960207.95       794770.57
#Sta/Elev= 30
  4895.8    2637  4901.1 2637.28  4914.9 2637.29  4929.2 2636.49  4940.8 2629.83
  4943.8 2628.93  4951.4  2629.7  4956.4 2629.51  4965.6 2629.69  4970.1 2628.78
  4977.5 2626.15  4985.1 2619.88  4994.2 2613.27  4997.5 2614.37    4998 2612.37
    5002 2612.37  5002.5 2614.37  5006.3 2619.47  5013.8 2623.11  5019.7 2625.46
  5022.4 2626.95    5035  2629.9  5044.3 2633.35    5049 2633.62  5060.5 2635.01
  5078.9  2635.4  5083.7 2635.86  5099.2 2638.58  5114.8  2640.1  5121.7 2641.22
#Mann= 6 ,-1 , 0
  4895.8     .03       0  4914.9     .09       0  4951.4     .03       0
  4977.5     .09       0  4997.5     .04       0  5002.5     .09       0
#XS Ineff= 2 , 0
       0  4972.5    2615  5027.5       0    2615
Permanent Ineff=
       F       F
Bank Sta=4997.5,5002.5
Exp/Cntr=0.5,0.3

Type RM Length L Ch R = 1 ,30027   ,124,124,124
BEGIN DESCRIPTION:
xs10
END DESCRIPTION:
XS GIS Cut Line= 5
        960527.3       794641.02       960442.53       794625.48
       960391.67       794622.66       960352.81       794614.89
       960205.17       794641.73
#Sta/Elev= 30
  4833.3  2655.9  4835.7 2654.86  4842.7 2647.99  4857.2 2631.16  4864.5  2628.1
  4870.4 2627.95  4894.2 2625.66  4916.1 2624.45  4926.2 2622.69  4935.1 2623.52
  4947.6 2623.79  4963.4 2623.11  4975.5 2622.52  4977.5 2621.99  4981.2 2619.13
 4992.94 2611.61 4994.19 2610.39  4996.8 2607.56  5003.2 2607.56 5006.89 2610.42
  5009.2 2612.01  5013.5 2612.56  5020.8 2613.12  5027.4 2612.21  5046.7 2613.16
  5073.5 2615.69  5086.9 2617.49  5113.2 2623.57  5142.5 2634.03  5160.1  2637.9
#Mann= 5 ,-1 , 0
  4833.3     .07       0  4916.1     .03       0  4963.4     .07       0
 4994.19     .04       0 5006.89     .08       0
Bank Sta=4994.19,5006.89
Exp/Cntr=0.5,0.3

Type RM Length L Ch R = 1 ,29903   ,51,51,51
BEGIN DESCRIPTION:
xs9
END DESCRIPTION:
XS GIS Cut Line= 6
       960479.26       794507.51       960433.34       794499.74
       960376.12       794494.09       960345.75       794493.38
       960289.23       794503.27       960188.92       794533.65
#Sta/Elev= 30
  4874.6 2620.14  4880.9 2619.46  4910.2 2615.26  4925.9  2613.3  4933.6 2613.35
    4960 2613.67  4969.1 2613.42  4976.5  2613.6  4985.5  2609.8  4995.7 2603.14
  4997.2 2602.13  4997.5    2600    4998    2599    5002    2599  5005.4 2605.05
  5010.1 2610.94  5019.1 2610.49  5023.7 2611.25  5065.8 2613.78  5078.5 2615.34
  5090.2 2616.24    5093 2616.81  5103.8 2619.94  5115.1 2622.87  5122.4 2625.13
  5130.4 2628.81  5136.2 2631.05  5146.6 2633.86  5155.5 2637.85  5171.3 2642.63
#Mann= 7 ,-1 , 0
  4874.6     .09       0  4933.6     .03       0  4969.1     .09       0
  4995.7     .04       0  5005.4     .09       0  5023.7     .03       0
  5115.1     .09       0
#XS Ineff= 2 , 0
       0    4970 2611.45    5030       0 2612.47
Permanent Ineff=
       F       F
Bank Sta=4995.7,5005.4
Exp/Cntr=0.5,0.3

Type RM Length L Ch R = 3 ,29875   ,,,
BEGIN DESCRIPTION:
xs11
Structure ID: Tax Service
Approximate Survey Structure
END DESCRIPTION:
Bridge Culvert--1,0,-1,-1, 0
Deck Dist Width WeirC Skew NumUp NumDn MinLoCord MaxHiCord MaxSubmerge Is_Ogee
22,12,3,0, 59, 52, , , , 0, 0.5,0.5,,
    4849  4855.8  4856.6  4859.3  4864.4  4865.8  4872.1  4879.6  4879.8  4880.3
  4888.2  4893.4  4895.9    4903  4903.8  4904.5  4909.3  4913.8  4914.2  4922.9
    4927  4932.9  4935.1  4939.8  4943.8  4944.8  4949.3    4989    4989    5011
    5011  5018.2  5019.4  5021.8  5026.5    5030    5031  5039.4  5040.5  5050.5
  5050.7  5062.7  5069.6  5071.9  5094.9  5096.1  5098.5  5110.7  5117.1  5122.7
  5129.7  5132.9  5138.4  5142.7  5145.9  5149.7  5163.7  5165.1  5172.1
 2619.98 2619.09 2619.01 2618.71 2618.12 2618.02 2617.34 2616.39 2616.36 2616.31
  2615.5  2614.8 2614.54 2613.99 2613.94 2613.83 2612.97 2612.19 2612.12 2611.11
 2611.29 2611.15 2611.22  2611.4 2611.55 2611.57  2611.6    2610    2610    2610
    2610 2611.26 2611.53 2612.05  2612.2 2612.29 2612.32 2612.95 2613.05 2614.48
 2614.49 2614.59 2614.69 2614.78 2615.97 2616.51 2617.23 2621.88 2623.05 2624.55
 2626.87 2628.05    2630 2631.06 2632.17 2633.56 2638.95 2639.47 2642.41
    2579    2579    2579    2579    2579    2579    2579    2579    2579    2579
    2579    2579    2579    2579    2579    2579    2579    2579    2579    2579
    2579    2579    2579    2579    2579    2579    2579    2579    2608    2608
    2579    2579    2579    2579    2579    2579    2579    2579    2579    2579
    2579    2579    2579    2579    2579    2579    2579    2579    2579    2579
    2579    2579    2579    2579    2579    2579    2579    2579    2579
    4849  4855.8  4856.6  4859.3  4864.4  4865.8  4872.1  4879.6  4879.8  4880.3
  4888.2  4893.4  4895.9    4903  4903.8  4904.5  4909.3  4913.8  4914.2  4922.9
    4989    4989    5011    5011  5018.2  5019.4  5021.8  5026.5    5030    5031
  5039.4  5040.5  5050.5  5050.7  5062.7  5069.6  5071.9  5094.9  5096.1  5098.5
  5110.7  5117.1  5122.7  5129.7  5132.9  5138.4  5142.7  5145.9  5149.7  5163.7
  5165.1  5172.1
 2619.98 2619.09 2619.01 2618.71 2618.12 2618.02 2617.34 2616.39 2616.36 2616.31
  2615.5  2614.8 2614.54 2613.99 2613.94 2613.83 2612.97 2612.19 2612.12 2611.11
    2608    2608    2608    2608 2611.26 2611.53 2612.05  2612.2 2612.29 2612.32
 2612.95 2613.05 2614.48 2614.49 2614.59 2614.69 2614.78 2615.97 2616.51 2617.23
 2621.88 2623.05 2624.55 2626.87 2628.05    2630 2631.06 2632.17 2633.56 2638.95
 2639.47 2642.41
    2579    2579    2579    2579    2579    2579    2579    2579    2579    2579
    2579    2579    2579    2579    2579    2579    2579    2579    2579    2579
    2579    2606    2606    2579    2579    2579    2579    2579    2579    2579
    2579    2579    2579    2579    2579    2579    2579    2579    2579    2579
    2579    2579    2579    2579    2579    2579    2579    2579    2579    2579
    2579    2579
BR Coef= 1 , 1 , 0 ,1.25, 0 ,,,0.8,0,2,0,
WSPro=,,,, 1 ,,,, 0 ,,,, 0 ,,,,-1 ,-1 ,-1 , 0 , 0 , 0 , 0 , 0
BC Design=,, 0 ,, 0 ,,,,,,
BC HTab HWMax=2642.63

Type RM Length L Ch R = 1 ,29852   ,56,56,56
BEGIN DESCRIPTION:
xs12
END DESCRIPTION:
XS GIS Cut Line= 5
         960516.       794441.11        960373.3       794441.11
       960357.05       794442.52       960331.62       794446.05
       960179.03       794482.08
#Sta/Elev= 30
  4832.1 2620.14    4836 2619.42  4852.1  2617.9    4910    2611  4918.2  2610.3
  4935.1 2609.69  4960.3 2609.87  4974.8 2609.09    4977 2609.02  4980.4 2607.68
  4991.7 2601.99  4994.9  2601.9  4997.5 2599.75    4998 2598.75    5002 2598.75
 5003.73 2602.12  5004.4 2603.44  5010.1 2604.96  5022.5 2611.77  5025.5 2612.42
  5043.3 2613.52    5050 2614.66  5081.1 2615.12  5096.4 2615.79  5102.7 2618.72
  5115.1 2621.59  5130.1 2625.74    5153 2634.77  5167.5 2639.29  5173.6 2641.62
#Mann= 5 ,-1 , 0
  4832.1     .09       0  4935.1     .03       0  4974.8     .09       0
  4994.9     .05       0 5003.73     .09       0
#XS Ineff= 2 , 0
       0 4983.57  2606.4    5020       0  2606.4
Permanent Ineff=
       F       F
#Block Obstruct= 1 ,-1
    5050    5081    2625
Bank Sta=4994.9,5003.73
Exp/Cntr=0.5,0.3

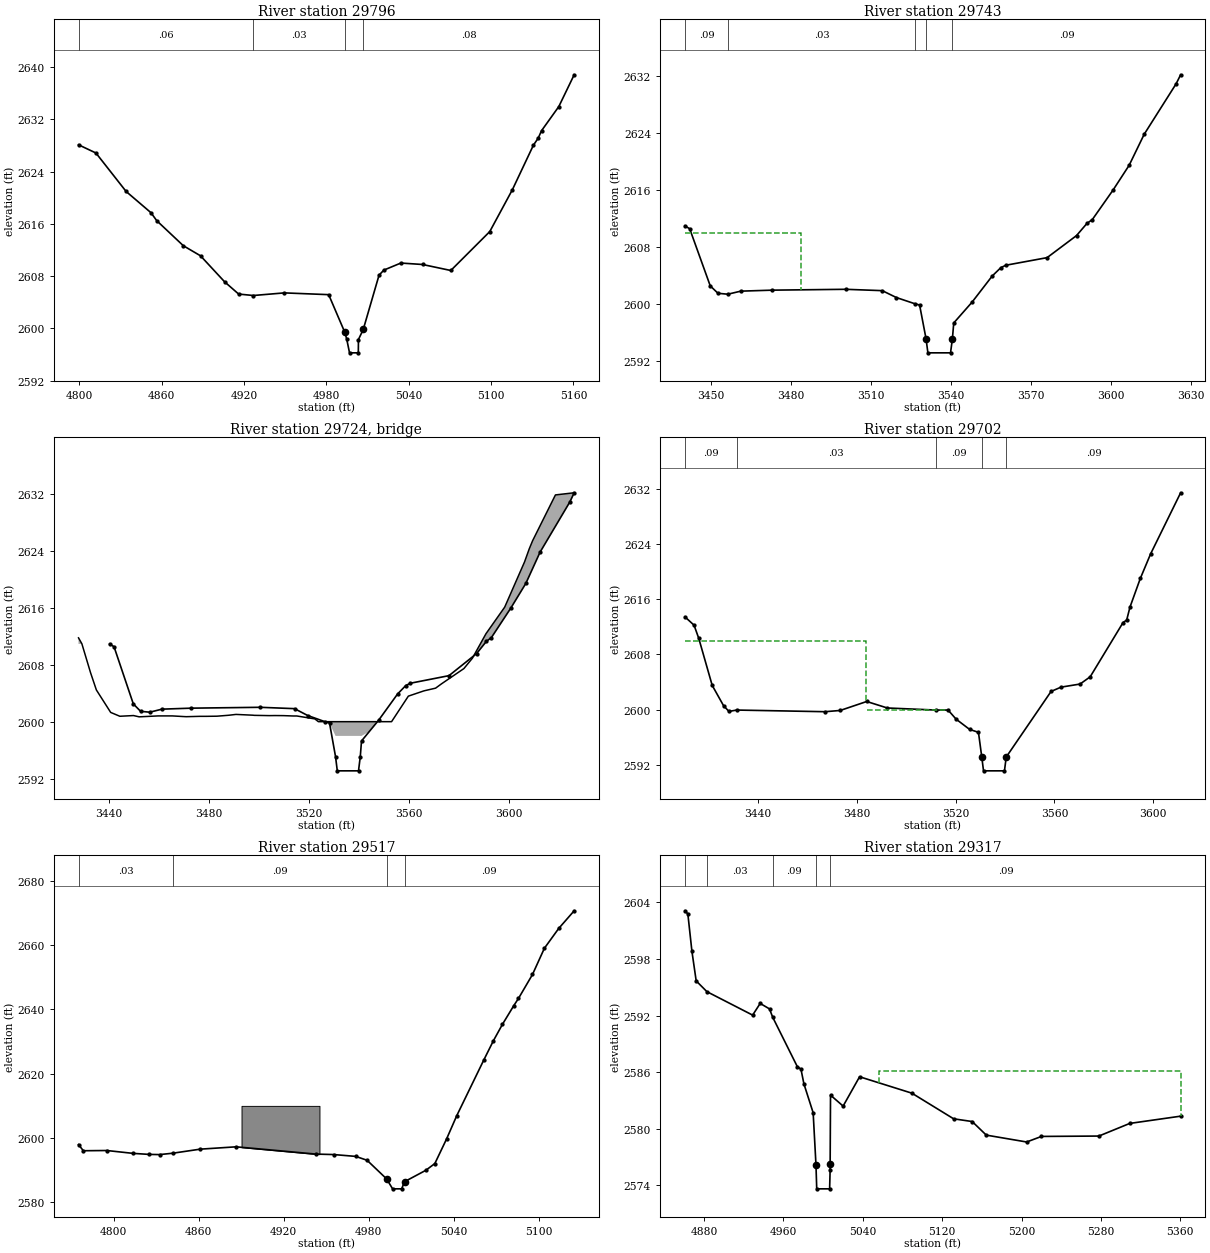
Type RM Length L Ch R = 1 ,29796   ,53,53,53
BEGIN DESCRIPTION:
xs13
END DESCRIPTION:
XS GIS Cut Line= 6
       960532.24       794349.27       960422.04       794361.28
       960352.81        794385.3        960318.9       794392.36
       960237.67       794410.73       960179.03        794418.5
#Sta/Elev= 30
  4799.3 2628.11    4812 2626.85    4834 2620.96  4852.1 2617.71  4856.3 2616.49
  4875.7 2612.65  4888.2 2611.11  4905.8 2607.12    4916 2605.25  4926.7 2605.03
  4949.3 2605.43  4981.6 2605.16  4993.4 2599.37 4994.78 2598.33  4996.8 2596.25
  5003.2 2596.25  5003.3 2598.29  5006.8 2599.83  5018.3 2608.14  5021.8 2608.92
  5034.2    2610    5050 2609.78  5070.6 2608.86    5099 2614.82  5115.5 2621.24
  5130.8 2628.05  5134.3 2629.13  5136.7 2630.26  5149.3 2633.96  5160.5 2638.83
#Mann= 4 ,-1 , 0
  4799.3     .06       0  4926.7     .03       0  4993.4     .05       0
  5006.8     .08       0
Bank Sta=4993.4,5006.8
Exp/Cntr=0.5,0.3

Type RM Length L Ch R = 1 ,29743   ,41,41,41
BEGIN DESCRIPTION:
xs14
END DESCRIPTION:
XS GIS Cut Line= 4
       960424.87       794281.46       960316.08       794336.56
       960287.11       794365.52       960190.34       794390.25
#Sta/Elev= 30
3440.216 2610.933441.984 2610.533449.691  2602.5 3452.59 2601.463456.267 2601.33
3461.146 2601.763472.955  2601.93500.461 2602.023514.179 2601.833519.482 2600.86
3526.483 2599.98 3528.18 2599.813530.584 2595.093531.291 2593.093539.776 2593.09
3540.484 2595.093540.979 2597.293547.837 2600.213555.404 2603.893558.656 2605.07
3560.495  2605.4 3575.98 2606.473587.011 2609.57  3590.9 2611.273592.951 2611.83
3600.729 2615.98 3606.74 2619.453612.396 2623.823624.346  2630.93626.043 2632.17
#Mann= 5 ,-1 , 0
3440.216     .09       03456.267     .03       03526.483     .09       0
3530.584     .05       03540.484     .09       0
#XS Ineff= 3 ,-1
 3400.22 3483.77    2610    3484 3517.86    2600 3553.21 3626.04    2600
Permanent Ineff=
       F       F       F
Bank Sta=3530.584,3540.484
Skew Angle= 45
Exp/Cntr=0.5,0.3

Type RM Length L Ch R = 3 ,29724   ,,,
BEGIN DESCRIPTION:
xs15
Structure ID: Gas Station
Approximate Survey Structure
END DESCRIPTION:
Bridge Culvert--1,0,-1,-1, 0
Deck Dist Width WeirC Skew NumUp NumDn MinLoCord MaxHiCord MaxSubmerge Is_Ogee
13,12,3,45, 44, 44, , , , 0, 0.5,0.5,,
3427.7713429.1143432.5793434.913 3440.643444.3173449.7623452.0243459.6613465.318
3469.2073470.8333476.3493478.8243483.1373487.8043490.7743497.5623498.0573504.138
3506.3313509.7953513.6143515.0993522.3113523.7253527.0493527.0493544.0193544.019
    35533559.7173565.9393570.606 3572.94 3581.923585.3143590.7593598.2543606.174
3608.0833609.4273618.5483626.043
 2611.78 2610.95 2606.89 2604.46  2601.3 2600.76 2600.86 2600.68 2600.81 2600.81
 2600.73  2600.7 2600.75 2600.75 2600.77  2600.9 2601.02 2600.91 2600.89 2600.85
 2600.86 2600.85  2600.8  2600.8 2600.39    2600    2600    2600    2600    2600
    2600 2603.59 2604.33 2604.71 2605.31 2607.46 2608.91 2612.36  2616.1 2622.44
  2624.3 2625.44 2631.87 2632.17
    2569    2569    2569    2569    2569    2569    2569    2569    2569    2569
    2569    2569    2569    2569    2569    2569    2569    2569    2569    2569
    2569    2569    2569    2569    2569    2569    2569    2598    2598    2569
    2569    2569    2569    2569    2569    2569    2569    2569    2569    2569
    2569    2569    2569    2569
3410.3763427.7713429.1143432.5793434.913 3440.643444.3173449.7623452.0243459.661
3465.3183469.2073470.8333476.3493478.8243483.1373487.8043490.7743497.5623498.057
3504.1383506.3313509.7953513.6143515.0993522.3113523.7253527.0493527.0493544.019
3544.019    35533559.7173565.9393570.606 3572.94 3581.923585.3143590.7593598.254
3606.1743608.0833609.4273618.548
 2613.43 2611.78 2610.95 2606.89 2604.46  2601.3 2600.76 2600.86 2600.68 2600.81
 2600.81 2600.73  2600.7 2600.75 2600.75 2600.77  2600.9 2601.02 2600.91 2600.89
 2600.85 2600.86 2600.85  2600.8  2600.8 2600.39    2600    2600    2600    2600
    2600    2600 2603.59 2604.33 2604.71 2605.31 2607.46 2608.91 2612.36  2616.1
 2622.44  2624.3 2625.44 2631.87
    2569    2569    2569    2569    2569    2569    2569    2569    2569    2569
    2569    2569    2569    2569    2569    2569    2569    2569    2569    2569
    2569    2569    2569    2569    2569    2569    2569    2569    2598    2598
    2569    2569    2569    2569    2569    2569    2569    2569    2569    2569
    2569    2569    2569    2569
BR Coef= 1 , 1 , 0 ,1.25, 0 ,,,0.8,0,2,0,
WSPro=,,,, 1 ,,,, 0 ,,,, 0 ,,,,-1 ,-1 ,-1 , 0 , 0 , 0 , 0 , 0
BC Design=,, 0 ,, 0 ,,,,,,
BC HTab HWMax=2632.17

Type RM Length L Ch R = 1 ,29702   ,185,185,185
BEGIN DESCRIPTION:
xs16
END DESCRIPTION:
XS GIS Cut Line= 4
       960424.16       794227.77       960287.11       794301.94
       960270.16       794328.08       960178.33       794359.16
#Sta/Elev= 30
3410.376 2613.433414.053 2612.233415.962 2610.323421.407  2603.53426.003 2600.56
3428.195 2599.733431.306 2599.933467.086 2599.693473.238 2599.873483.986 2601.17
 3492.33 2600.233511.917 2599.933516.937 2599.933520.189 2598.613525.634 2597.13
3529.241  2596.73530.584 2593.123531.291 2591.123539.776 2591.123540.484 2593.12
3558.656 2602.633562.687 2603.253570.394  2603.73574.496 2604.753587.789  2612.6
3589.274 2612.983590.617 2614.863594.789    26193598.961 2622.563611.124 2631.42
#Mann= 5 ,-1 , 0
3410.376     .09       03431.306     .03       03511.917     .09       0
3530.584     .05       03540.484     .09       0
#XS Ineff= 3 ,-1
 3410.38 3483.77    2610    3484 3515.74    2600 3555.33 3611.12    2600
Permanent Ineff=
       F       F       F
Bank Sta=3530.584,3540.484
Skew Angle= 45
Exp/Cntr=0.5,0.3

Type RM Length L Ch R = 1 ,29517   ,200,200,200
BEGIN DESCRIPTION:
xs17
END DESCRIPTION:
XS GIS Cut Line= 4
       960397.32       794158.54       960203.05        794176.2
       960152.19       794173.37        960054.7        794208.7
#Sta/Elev= 30
  4775.2 2597.95  4778.6 2596.03  4795.2  2596.1  4813.7 2595.21    4825 2594.89
  4832.4 2594.83  4841.7 2595.26    4861 2596.52  4886.4 2597.25  4942.5 2594.99
  4955.3 2594.84  4970.8 2594.27  4978.8 2593.06 4992.58 2587.26  4996.8 2584.17
  5003.2 2584.17  5005.2 2586.39  5020.2 2589.93  5026.6 2592.04  5034.9 2599.72
  5042.1 2606.98  5061.1 2624.24  5067.9 2630.26  5074.3 2635.38  5082.3  2641.2
  5085.6 2643.44  5095.5  2650.9  5103.9 2659.07    5114 2665.23  5124.9 2670.73
#Mann= 4 ,-1 , 0
  4775.2     .03       0  4841.7     .09       0 4992.58     .05       0
  5005.2     .09       0
#Block Obstruct= 1 ,-1
  4890.2  4945.2    2610
Bank Sta=4992.58,5005.2
Exp/Cntr=0.5,0.3

Type RM Length L Ch R = 1 ,29317   ,94,94,94
BEGIN DESCRIPTION:
xs18
END DESCRIPTION:
XS GIS Cut Line= 5
       960404.82       794121.54        960317.4        794108.3
       960298.86       793971.43        960234.4       793797.47
       960212.32        793712.7
#Sta/Elev= 30
  4860.7 2603.12  4863.6 2602.78  4867.7 2598.82    4872 2595.68  4882.8 2594.54
  4928.9 2592.05  4936.5 2593.29  4945.9 2592.71  4949.1 2591.83    4974 2586.57
  4977.6 2586.32  4980.6 2584.75  4989.9 2581.69 4992.72  2576.2  4993.5 2573.62
  5006.5 2573.62    5007 2575.62 5007.02 2576.22  5007.4 2583.56  5020.1  2582.4
  5036.7 2585.51  5089.4 2583.77  5131.5 2581.05  5150.2 2580.76  5164.4 2579.32
  5205.1 2578.59    5220 2579.18  5277.9 2579.22    5309 2580.56  5360.3 2581.33
#Mann= 5 ,-1 , 0
  4860.7     .09       0  4882.8     .03       0  4949.1     .09       0
 4992.72     .05       0 5007.02     .09       0
#XS Ineff= 2 , 0
       0    4944 2591.24    5056       0 2586.07
Permanent Ineff=
       F       F
Bank Sta=4992.72,5007.02
Exp/Cntr=0.5,0.3

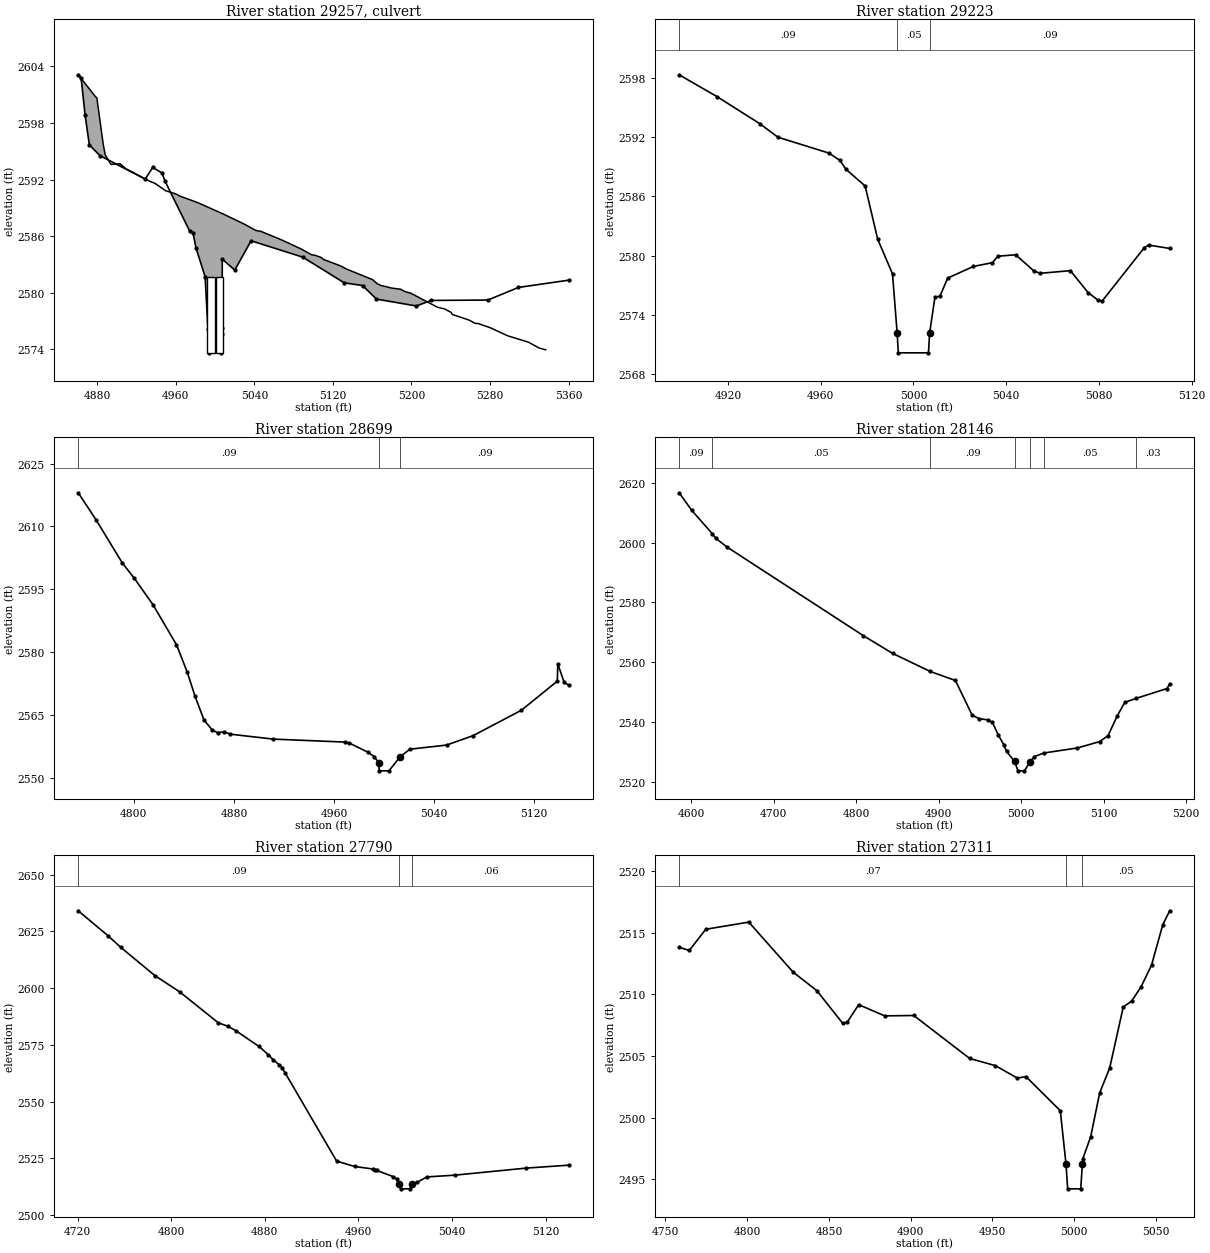
Type RM Length L Ch R = 2 ,29257   ,,,
BEGIN DESCRIPTION:
xs19
Structure ID: California Crk Rd
Approximate Survey Structure
END DESCRIPTION:
Bridge Culvert--1,0,-1,-1, 0
Deck Dist Width WeirC Skew NumUp NumDn MinLoCord MaxHiCord MaxSubmerge Is_Ogee
47.5,25,3,0, 45, 44, , , , 0, 1,1,,
  4860.7  4878.5  4879.6  4886.1  4888.1    4894  4903.3  4909.1  4933.5    4939
  4949.8  4960.1  4964.2  4982.3  5007.5  5030.3  5041.4  5046.6  5067.4  5087.7
  5098.5  5101.6  5107.8  5110.7  5127.7  5134.1  5160.4  5165.2    5169  5179.9
  5188.9  5193.4  5199.3  5226.5    5234  5240.4  5241.7  5258.6  5265.2  5267.9
  5279.9    5298    5319  5330.1  5336.8
 2603.12 2600.76  2600.7 2595.77 2594.63 2593.61 2593.68 2593.16 2591.82 2591.59
 2590.81 2590.48 2590.25 2589.56 2588.39 2587.25 2586.61 2586.51 2585.62 2584.64
 2584.02 2583.98 2583.75 2583.52 2582.85  2582.5 2581.39 2580.95 2580.77 2580.49
 2580.37 2580.12 2579.95 2578.46 2578.27 2577.91 2577.69  2577.1 2576.74 2576.73
  2576.3 2575.43 2574.76 2574.13 2573.94
    2550    2550    2550    2550    2550    2550    2550    2550    2550    2550
    2550    2550    2550    2550    2550    2550    2550    2550    2550    2550
    2550    2550    2550    2550    2550    2550    2550    2550    2550    2550
    2550    2550    2550    2550    2550    2550    2550    2550    2550    2550
    2550    2550    2550    2550    2550
  4878.5  4879.6  4886.1  4888.1    4894  4903.3  4909.1  4933.5    4939  4949.8
  4960.1  4964.2  4982.3  5007.5  5030.3  5041.4  5046.6  5067.4  5087.7  5098.5
  5101.6  5107.8  5110.7  5127.7  5134.1  5160.4  5165.2    5169  5179.9  5188.9
  5193.4  5199.3  5226.5    5234  5240.4  5241.7  5258.6  5265.2  5267.9  5279.9
    5298    5319  5330.1  5336.8
 2600.76  2600.7 2595.77 2594.63 2593.61 2593.68 2593.16 2591.82 2591.59 2590.81
 2590.48 2590.25 2589.56 2588.39 2587.25 2586.61 2586.51 2585.62 2584.64 2584.02
 2583.98 2583.75 2583.52 2582.85  2582.5 2581.39 2580.95 2580.77 2580.49 2580.37
 2580.12 2579.95 2578.46 2578.27 2577.91 2577.69  2577.1 2576.74 2576.73  2576.3
 2575.43 2574.76 2574.13 2573.94
    2550    2550    2550    2550    2550    2550    2550    2550    2550    2550
    2550    2550    2550    2550    2550    2550    2550    2550    2550    2550
    2550    2550    2550    2550    2550    2550    2550    2550    2550    2550
    2550    2550    2550    2550    2550    2550    2550    2550    2550    2550
    2550    2550    2550    2550
Culvert=2,8,8,25,0.013,0.4,1,8,1,2573.62,4995.5,2569.88,4995.5,Culvert #1  , 0 ,47.5
Culvert Bottom n=0.013
Culvert=2,8,8,25,0.013,0.4,1,8,1,2573.62,5004.5,2569.88,5004.5,Culvert #2  , 0 ,47.5
Culvert Bottom n=0.013
BC Design=,, 0 ,, 0 ,,,,,,
BC HTab HWMax=2603.12

Type RM Length L Ch R = 1 ,29223   ,524,524,524
BEGIN DESCRIPTION:
xs20
END DESCRIPTION:
XS GIS Cut Line= 4
         960411.       794080.04       960371.86       793986.95
       960362.44        793910.5       960289.15        793671.2
#Sta/Elev= 30
    4899  2598.3  4915.4 2596.08  4933.7 2593.36  4941.6 2591.98  4963.6 2590.37
  4968.3 2589.64  4970.9 2588.74  4979.2 2587.04  4984.6 2581.66    4991 2578.14
    4993 2572.15  4993.5 2570.15  5006.5 2570.15    5007 2572.15  5009.3 2575.81
  5011.4 2575.86  5014.8 2577.72  5025.9  2578.9  5034.1 2579.28  5036.4 2579.93
  5044.1 2580.08  5051.8 2578.47  5054.6  2578.2  5067.7 2578.47  5075.3 2576.25
  5079.6 2575.49  5081.4  2575.4  5099.5 2580.78  5101.4 2581.06  5110.5 2580.72
#Mann= 3 ,-1 , 0
    4899     .09       0    4993     .05       0    5007     .09       0
#XS Ineff= 2 , 0
       0    4970    2578    5030       0    2578
Permanent Ineff=
       F       F
Bank Sta=4993,5007
Exp/Cntr=0.5,0.3

Type RM Length L Ch R = 1 ,28699   ,553,553,553
BEGIN DESCRIPTION:
xs21
END DESCRIPTION:
XS GIS Cut Line= 6
       960522.26        793369.2       960417.18       793447.79
       960339.48        793473.4       960296.21       793481.35
       960264.42       793500.77       960224.69       793589.96
#Sta/Elev= 30
  4755.6 2618.04    4770  2611.5  4790.7 2601.32  4800.5 2597.57  4815.4 2591.27
  4834.1 2581.74  4842.6 2575.28  4848.8 2569.55  4856.1 2563.75  4862.7 2561.37
  4866.9 2560.76  4872.4 2560.95  4876.7  2560.4  4911.4 2559.21  4968.6  2558.5
  4972.1 2558.28  4987.2 2556.06    4992 2555.02  4995.7 2553.61  4996.1 2551.63
  5003.9 2551.63  5012.7 2554.96  5020.5 2556.79    5050 2557.79  5071.2 2560.05
  5109.7  2566.1  5138.4 2573.05  5138.8 2577.15  5143.9 2572.74  5147.6 2572.09
#Mann= 3 ,-1 , 0
  4755.6     .09       0  4995.7     .05       0  5012.7     .09       0
Bank Sta=4995.7,5012.7
Exp/Cntr=0.3,0.1

Type RM Length L Ch R = 1 ,28146   ,356,356,356
BEGIN DESCRIPTION:
xs22
END DESCRIPTION:
XS GIS Cut Line= 6
       960443.68       793034.54        960171.7       793097.23
       960022.47       793084.87       959963.31       793098.12
       959920.92       793120.19       959886.49       793165.22
#Sta/Elev= 30
  4585.6 2616.67    4601 2610.75  4625.6 2603.03  4629.9 2601.44  4643.7 2598.48
  4808.9 2568.81  4844.4 2562.87  4889.9 2556.84  4920.3 2553.83  4940.7 2542.19
  4949.3 2541.02  4959.5 2540.65  4965.1 2539.83  4972.4 2535.49  4978.8 2532.35
  4982.2 2530.08    4992 2526.75  4996.1 2523.58  5003.9 2523.58 5010.79 2526.61
  5015.8 2528.33  5027.4 2529.55  5068.1 2531.24  5095.1 2533.37  5105.3 2535.39
  5116.1 2541.83  5125.4 2546.48  5139.5 2547.86  5176.7 2551.14  5179.9 2552.77
#Mann= 7 ,-1 , 0
  4585.6     .09       0  4625.6     .05       0  4889.9     .09       0
    4992     .05       0 5010.79     .09       0  5027.4     .05       0
  5139.5     .03       0
Bank Sta=4992,5010.79
Exp/Cntr=0.3,0.1

Type RM Length L Ch R = 1 ,27790   ,479,479,479
BEGIN DESCRIPTION:
xs23
END DESCRIPTION:
XS GIS Cut Line= 6
       960323.58        792724.6       960101.94       792732.54
        960052.5       792742.26        960036.6        792750.2
       960029.54       792828.79       960032.19       792879.12
#Sta/Elev= 30
  4720.5 2634.03  4745.9 2623.04    4757 2617.86  4785.9  2605.5  4807.2 2598.32
  4840.1 2584.72  4848.7 2583.07  4855.2 2581.22  4874.8 2574.33    4883 2570.65
    4887 2568.47  4892.5 2566.13  4894.6 2564.98  4897.4 2562.59  4941.4 2523.74
  4956.7 2521.38  4972.9 2520.22  4973.9 2519.77  4975.8 2519.62  4989.6 2516.93
  4992.6 2515.94 4994.49 2513.66  4996.1 2511.52  5003.9 2511.52  5006.1  2513.8
  5010.4 2514.45  5018.5 2516.77  5042.5 2517.55  5103.5 2520.66  5139.9 2521.95
#Mann= 3 , 0 , 0
  4720.5     .09       0 4994.49     .05       0  5006.1     .06       0
Bank Sta=4994.49,5006.1
Exp/Cntr=0.5,0.3

Type RM Length L Ch R = 1 ,27311   ,44,44,44
BEGIN DESCRIPTION:
xs24
END DESCRIPTION:
XS GIS Cut Line= 6
       959897.08       792548.87       959827.32       792552.41
       959796.42       792540.93        959739.9       792465.87
       959701.05       792425.25       959654.25       792421.72
#Sta/Elev= 30
  4758.4 2513.82  4764.6 2513.56  4774.7 2515.28    4801 2515.86  4828.2 2511.79
  4842.6  2510.3  4858.4 2507.65  4861.2 2507.74  4868.2 2509.16  4884.1 2508.25
  4901.9 2508.28  4936.1 2504.79  4951.8 2504.21  4965.2  2503.2  4970.5 2503.32
  4991.5 2500.55    4995 2496.21    4996 2494.21    5004 2494.21    5005 2496.21
  5005.2 2496.62  5010.1 2498.45  5015.6    2502  5021.7 2504.02    5030 2508.97
  5035.1 2509.44  5040.9 2510.61  5047.3 2512.37  5054.2 2515.66  5058.4 2516.78
#Mann= 3 ,-1 , 0
  4758.4     .07       0    4995    .045       0    5005     .05       0
#XS Ineff= 2 , 0
       0    4950          5026.5       0 2503.99
Permanent Ineff=
       T       F
Bank Sta=4995,5005
Exp/Cntr=0.5,0.3