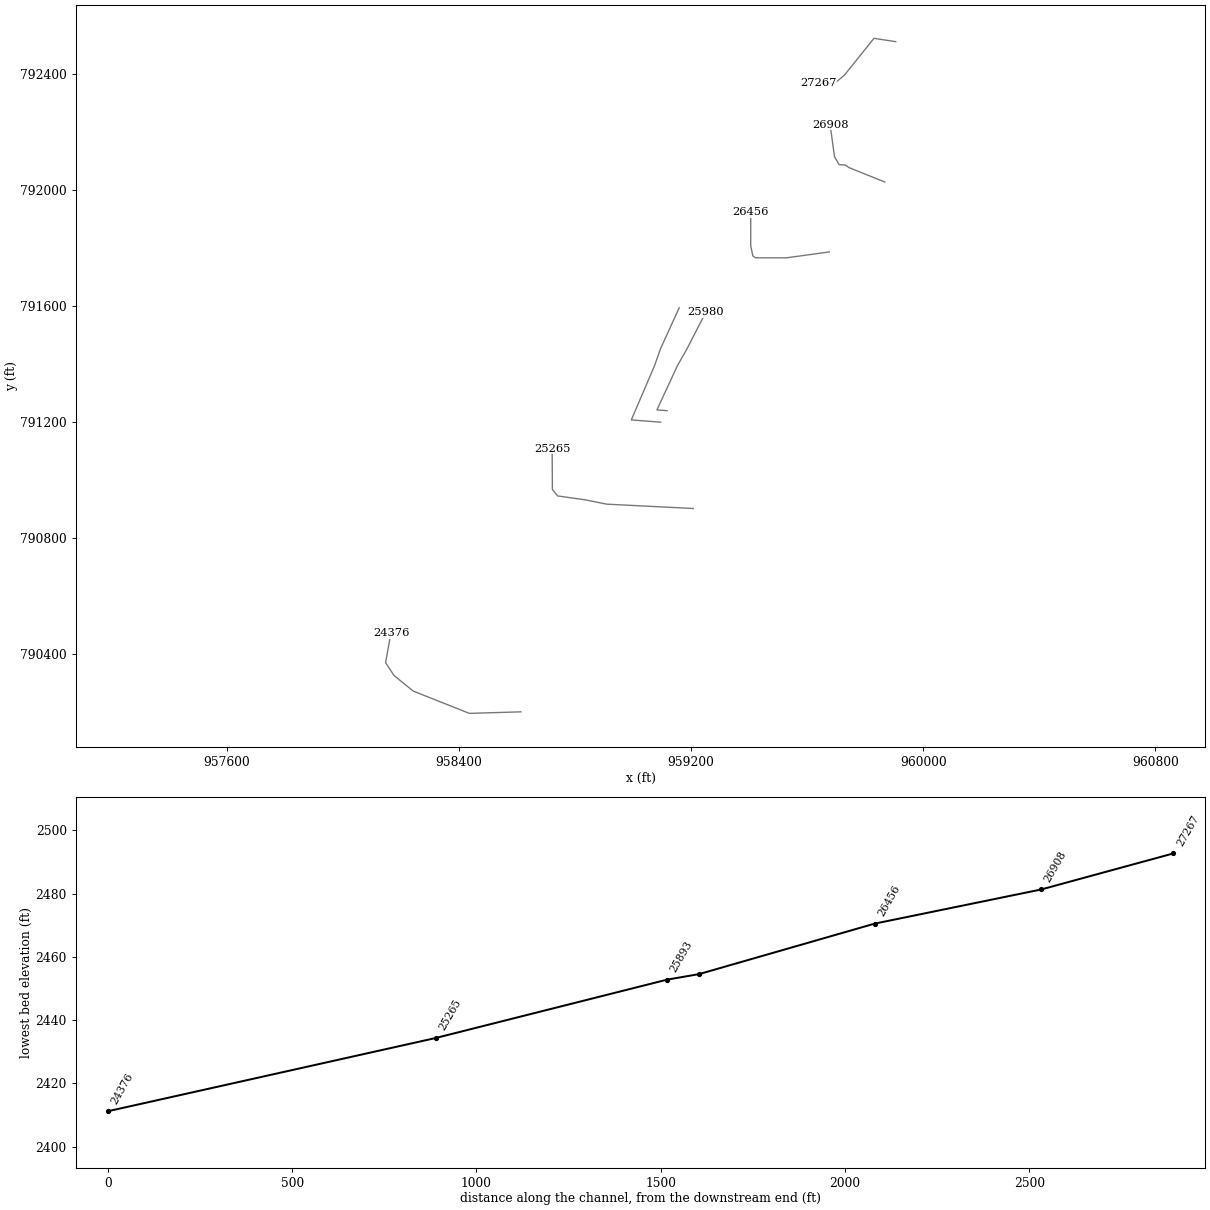
HEC-RAS study lds_california_crk.prj: California Creek Limited Detail Study

--- lds_california_crk.g01 (geometry) --- (continued)

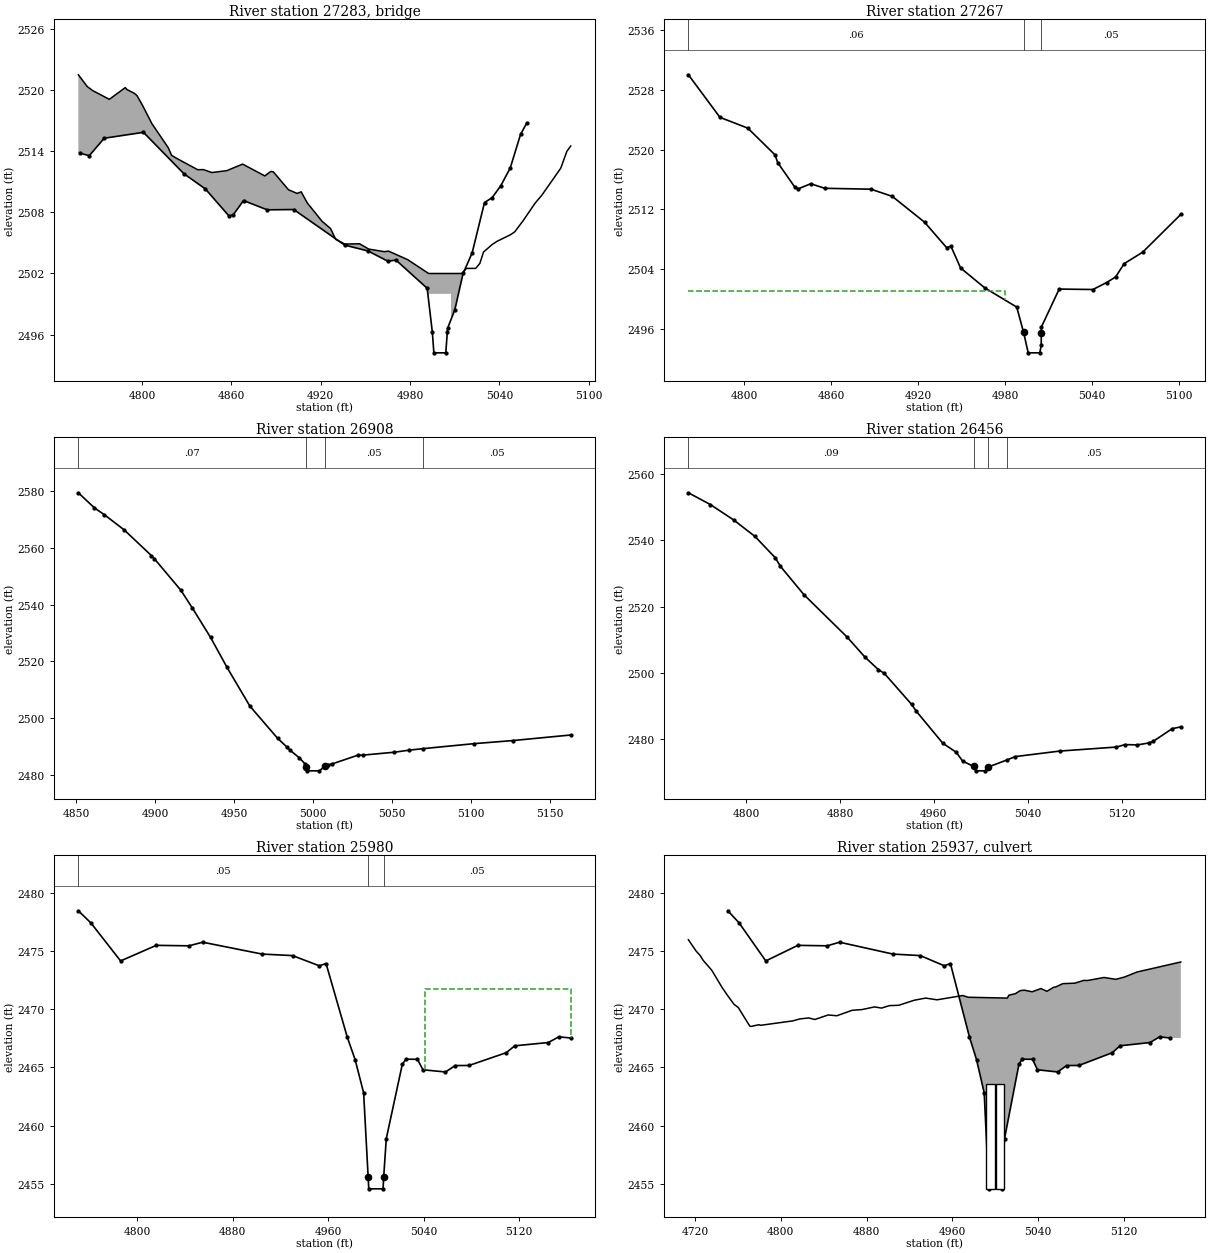
Type RM Length L Ch R = 3 ,27283   ,,,
BEGIN DESCRIPTION:
xs25
Structure ID: Sckewed Driveway
Approximate Survey Structure
END DESCRIPTION:
Bridge Culvert--1,0,-1,-1, 0
Deck Dist Width WeirC Skew NumUp NumDn MinLoCord MaxHiCord MaxSubmerge Is_Ogee
19,18,3,0, 53, 53, , , , 0, 0.5,0.5,,
  4757.3  4763.3  4766.9  4778.1  4788.8    4790  4794.8  4796.7  4800.3  4806.7
  4817.7  4819.9  4823.1  4837.4  4841.3  4846.9    4857  4867.6  4882.5  4886.5
  4888.2  4898.4  4904.2  4906.9    4911  4920.9  4926.6  4930.1  4936.2  4946.1
  4952.2  4962.8  4965.5  4978.4  4992.5  4992.5  5007.5  5007.5  5014.7  5017.9
  5024.1  5026.9  5029.3    5035  5038.3  5047.5  5050.3  5055.8  5064.1  5068.4
  5081.2  5085.3  5087.9
 2521.51 2520.35 2519.96  2519.1 2520.25 2520.05  2519.7 2519.46 2518.53 2516.71
 2514.34  2513.6 2513.32 2512.19  2512.2 2511.91  2512.1 2512.74 2511.58 2512.02
 2511.98 2510.22 2509.86 2510.02 2508.93 2507.13 2506.42 2505.35 2504.89 2504.92
  2504.4 2504.14  2504.2 2503.36    2502    2502    2502    2502    2502  2502.5
  2502.5    2503  2504.1 2504.83 2505.15 2505.81 2506.09 2507.16 2508.93 2509.67
 2512.34    2514 2514.52
  2473.3  2473.3  2473.3  2473.3  2473.3  2473.3  2473.3  2473.3  2473.3  2473.3
  2473.3  2473.3  2473.3  2473.3  2473.3  2473.3  2473.3  2473.3  2473.3  2473.3
  2473.3  2473.3  2473.3  2473.3  2473.3  2473.3  2473.3  2473.3  2473.3  2473.3
  2473.3  2473.3  2473.3  2473.3  2473.3    2500    2500  2473.3  2473.3  2473.3
  2473.3  2473.3  2473.3  2473.3  2473.3  2473.3  2473.3  2473.3  2473.3  2473.3
  2473.3  2473.3  2473.3
  4757.3  4763.3  4766.9  4778.1  4788.8    4790  4794.8  4796.7  4800.3  4806.7
  4817.7  4819.9  4823.1  4837.4  4841.3  4846.9    4857  4867.6  4882.5  4886.5
  4888.2  4898.4  4904.2  4906.9    4911  4920.9  4926.6  4930.1  4936.2  4946.1
  4952.2  4962.8  4965.5  4978.4  4992.5  4992.5  5007.5  5007.5  5014.7  5017.9
  5024.1  5026.9  5029.3    5035  5038.3  5047.5  5050.3  5055.8  5064.1  5068.4
  5081.2  5085.3  5087.9
 2521.51 2520.35 2519.96  2519.1 2520.25 2520.05  2519.7 2519.46 2518.53 2516.71
 2514.34  2513.6 2513.32 2512.19  2512.2 2511.91  2512.1 2512.74 2511.58 2512.02
 2511.98 2510.22 2509.86 2510.02 2508.93 2507.13 2506.42 2505.35 2504.89 2504.92
  2504.4 2504.14  2504.2 2503.36    2502    2502    2502    2502    2502  2502.5
  2502.5    2503  2504.1 2504.83 2505.15 2505.81 2506.09 2507.16 2508.93 2509.67
 2512.34    2514 2514.52
  2473.3  2473.3  2473.3  2473.3  2473.3  2473.3  2473.3  2473.3  2473.3  2473.3
  2473.3  2473.3  2473.3  2473.3  2473.3  2473.3  2473.3  2473.3  2473.3  2473.3
  2473.3  2473.3  2473.3  2473.3  2473.3  2473.3  2473.3  2473.3  2473.3  2473.3
  2473.3  2473.3  2473.3  2473.3  2473.3    2500    2500  2473.3  2473.3  2473.3
  2473.3  2473.3  2473.3  2473.3  2473.3  2473.3  2473.3  2473.3  2473.3  2473.3
  2473.3  2473.3  2473.3
BR Coef= 1 , 1 , 0 ,1.25, 0 ,,,0.8,0,2,0,
WSPro=,,,, 1 ,,,, 0 ,,,, 0 ,,,,-1 ,-1 ,-1 , 0 , 0 , 0 , 0 , 0
BC Design=,, 0 ,, 0 ,,,,,,
BC HTab HWMax=2516.78

Type RM Length L Ch R = 1 ,27267   ,359,359,359
BEGIN DESCRIPTION:
xs26
END DESCRIPTION:
XS GIS Cut Line= 5
       959905.03       792510.02       959829.97        792521.5
       959728.16       792394.51        959693.1        792365.2
       959637.47       792366.97
#Sta/Elev= 30
  4761.3 2530.02  4783.1 2524.31  4802.3 2522.87  4821.1 2519.29    4823 2518.24
  4834.8 2514.96  4837.2 2514.73  4845.8 2515.41  4855.5  2514.8  4887.4 2514.68
  4902.1 2513.72  4924.4 2510.26  4939.7 2506.83  4942.6 2507.04  4949.3 2504.12
    4966 2501.45  4988.1 2498.87 4992.82 2495.48    4996 2492.74    5004 2492.74
    5005 2493.75 5005.05 2495.45  5005.1  2496.2  5017.4 2501.29  5040.7 2501.23
  5050.2 2502.17  5056.4 2502.92  5062.3  2504.7  5075.1 2506.24  5101.4  2511.3
#Mann= 3 ,-1 , 0
  4761.3     .06       0 4992.82    .045       0 5005.05     .05       0
#XS Ineff= 2 , 0
       0    4980    2501    5018       0    2501
Permanent Ineff=
       F       F
Bank Sta=4992.82,5005.05
Exp/Cntr=0.5,0.3

Type RM Length L Ch R = 1 ,26908   ,452,452,452
BEGIN DESCRIPTION:
xs27
END DESCRIPTION:
XS GIS Cut Line= 6
       959867.06       792026.12       959744.32       792075.57
       959730.67       792084.62       959709.88       792086.17
       959693.99       792112.66       959678.98       792223.04
#Sta/Elev= 30
  4851.3 2579.47  4861.5 2574.13  4867.8 2571.72  4880.3 2566.38  4897.6 2557.28
  4899.4 2556.21  4916.2 2545.08  4923.4 2538.87    4935 2528.44  4945.3 2517.98
  4959.9 2504.19  4977.5 2492.79  4983.6 2489.62  4985.4 2488.58  4991.2 2485.93
    4995  2483.7 4995.41 2482.85  4996.1 2481.33  5003.9 2481.33  5007.5 2482.97
  5009.4 2483.42    5012 2483.77  5028.5 2486.89  5031.3 2486.87  5051.4  2487.9
  5060.5 2488.61  5069.5 2489.16    5102 2490.93  5126.3 2492.01  5163.1 2493.98
#Mann= 4 ,-1 , 0
  4851.3     .07       0 4995.41     .05       0  5007.5     .05       0
  5069.5     .05       0
Bank Sta=4995.41,5007.5
Exp/Cntr=0.3,0.1

Type RM Length L Ch R = 1 ,26456   ,476,476,476
BEGIN DESCRIPTION:
xs28
END DESCRIPTION:
XS GIS Cut Line= 6
       959676.33       791785.06       959528.86       791764.75
       959421.13       791764.75        959412.3       791771.81
       959405.24       791806.25       959405.24       791922.81
#Sta/Elev= 30
  4750.9 2554.28  4769.6 2550.74  4789.5 2546.09  4807.6 2541.14  4824.9 2534.71
  4829.3 2532.14  4849.4 2523.57  4886.3 2510.76  4901.3  2504.8  4912.7 2501.03
  4917.8  2499.9  4941.1 2490.54    4945 2488.52  4967.7 2478.83  4979.3 2476.08
  4984.5 2473.48 4993.92 2471.86  4996.1 2470.52  5003.9 2470.52  5005.9 2471.61
  5022.2 2473.77  5029.4 2474.81  5067.4 2476.48  5115.5 2477.68    5123 2478.42
  5133.6 2478.34    5143  2478.9  5146.9 2479.38  5163.2 2483.23  5170.5 2483.76
#Mann= 4 ,-1 , 0
  4750.9     .09       0 4993.92     .05       0  5005.9     .09       0
  5022.2     .05       0
Bank Sta=4993.92,5005.9
Exp/Cntr=0.5,0.3

Type RM Length L Ch R = 1 ,25980   ,87,87,87
BEGIN DESCRIPTION:
xs29
END DESCRIPTION:
XS GIS Cut Line= 5
       959117.37       791237.58       959082.05       791240.23
       959152.69       791392.99       959185.36       791450.39
       959250.71       791577.55
#Sta/Elev= 30
  4750.6 2478.46  4761.1 2477.42    4786 2474.15  4815.9 2475.49  4843.3 2475.45
  4854.8 2475.76  4904.6 2474.74  4930.1 2474.61  4952.6 2473.73  4958.2 2473.93
    4976  2467.6  4982.6 2465.66  4989.7 2462.82  4993.5 2455.57    4994 2454.57
    5006 2454.57  5006.5 2455.57  5008.7 2458.89  5022.1 2465.26  5025.1 2465.71
  5034.8  2465.7  5039.4  2464.8  5058.3 2464.61  5066.5 2465.16  5078.1 2465.17
  5109.3 2466.27  5116.4 2466.86  5144.5 2467.14  5153.3 2467.63  5163.3 2467.53
#Mann= 3 ,-1 , 0
  4750.6     .05       0  4993.5     .05       0  5006.5     .05       0
#XS Ineff= 2 , 0
       0    4959 2470.99    5041       0 2471.74
Permanent Ineff=
       F       F
Bank Sta=4993.5,5006.5
Exp/Cntr=0.5,0.3

Type RM Length L Ch R = 2 ,25937   ,,,
BEGIN DESCRIPTION:
xs30
Structure ID: US-23
Approximate Survey Structure
END DESCRIPTION:
Bridge Culvert--1,0,-1,-1, 0
Deck Dist Width WeirC Skew NumUp NumDn MinLoCord MaxHiCord MaxSubmerge Is_Ogee
32.5,21,3,0, 49, 50, , , , 0, 1,1,,
  4713.8    4721  4724.9  4727.5  4735.6  4745.3  4750.2  4756.4  4760.3    4771
    4772  4779.6  4781.2  4811.2  4817.8  4826.1  4831.8  4844.2  4852.2  4866.6
  4875.6  4887.4    4894  4901.2    4910  4924.3  4935.1  4945.7  4969.7  4974.8
  5011.3  5012.8  5018.8  5023.3  5027.1  5034.4  5042.7  5048.2  5054.7  5056.1
    5063  5074.2  5082.6  5086.1  5101.5  5112.5  5120.6  5132.3  5173.1
 2475.97    2475  2474.6 2474.21 2473.35 2471.86  2471.2 2470.42 2470.15 2468.56
 2468.52 2468.67 2468.62    2469 2469.17 2469.25 2469.12 2469.51 2469.44 2469.91
 2469.97  2470.2  2470.1 2470.31 2470.34 2470.77 2470.96 2470.81 2471.18 2471.03
 2470.96 2471.21 2471.34  2471.6 2471.64  2471.5 2471.78 2471.54  2471.9  2471.9
  2472.2 2472.24 2472.48 2472.47 2472.73 2472.57 2472.77  2473.2 2474.06
    2428    2428    2428    2428    2428    2428    2428    2428    2428    2428
    2428    2428    2428    2428    2428    2428    2428    2428    2428    2428
    2428    2428    2428    2428    2428    2428    2428    2428    2428    2428
    2428    2428    2428    2428    2428    2428    2428    2428    2428    2428
    2428    2428    2428    2428    2428    2428    2428    2428    2428
  4651.6  4713.8    4721  4724.9  4727.5  4735.6  4745.3  4750.2  4756.4  4760.3
    4771    4772  4779.6  4781.2  4811.2  4817.8  4826.1  4831.8  4844.2  4852.2
  4866.6  4875.6  4887.4    4894  4901.2    4910  4924.3  4935.1  4945.7  4969.7
  4974.8  5011.3  5012.8  5018.8  5023.3  5027.1  5034.4  5042.7  5048.2  5054.7
  5056.1    5063  5074.2  5082.6  5086.1  5101.5  5112.5  5120.6  5132.3  5173.1
 2476.78 2475.97    2475  2474.6 2474.21 2473.35 2471.86  2471.2 2470.42 2470.15
 2468.56 2468.52 2468.67 2468.62    2469 2469.17 2469.25 2469.12 2469.51 2469.44
 2469.91 2469.97  2470.2  2470.1 2470.31 2470.34 2470.77 2470.96 2470.81 2471.18
 2471.03 2470.96 2471.21 2471.34  2471.6 2471.64  2471.5 2471.78 2471.54  2471.9
  2471.9  2472.2 2472.24 2472.48 2472.47 2472.73 2472.57 2472.77  2473.2 2474.06
    2428    2428    2428    2428    2428    2428    2428    2428    2428    2428
    2428    2428    2428    2428    2428    2428    2428    2428    2428    2428
    2428    2428    2428    2428    2428    2428    2428    2428    2428    2428
    2428    2428    2428    2428    2428    2428    2428    2428    2428    2428
    2428    2428    2428    2428    2428    2428    2428    2428    2428    2428
Culvert=2,9,8,21,0.013,0.4,1,8,1,2454.57,4995.5,2452.81,4995.5,Culvert #1  , 0 ,32.5
Culvert Bottom n=0.013
Culvert=2,9,8,21,0.013,0.4,1,8,1,2454.57,5004.5,2452.81,5004.5,Culvert #2  , 0 ,32.5
Culvert Bottom n=0.013
BC Design=,, 0 ,, 0 ,,,,,,
BC HTab HWMax=2478.46

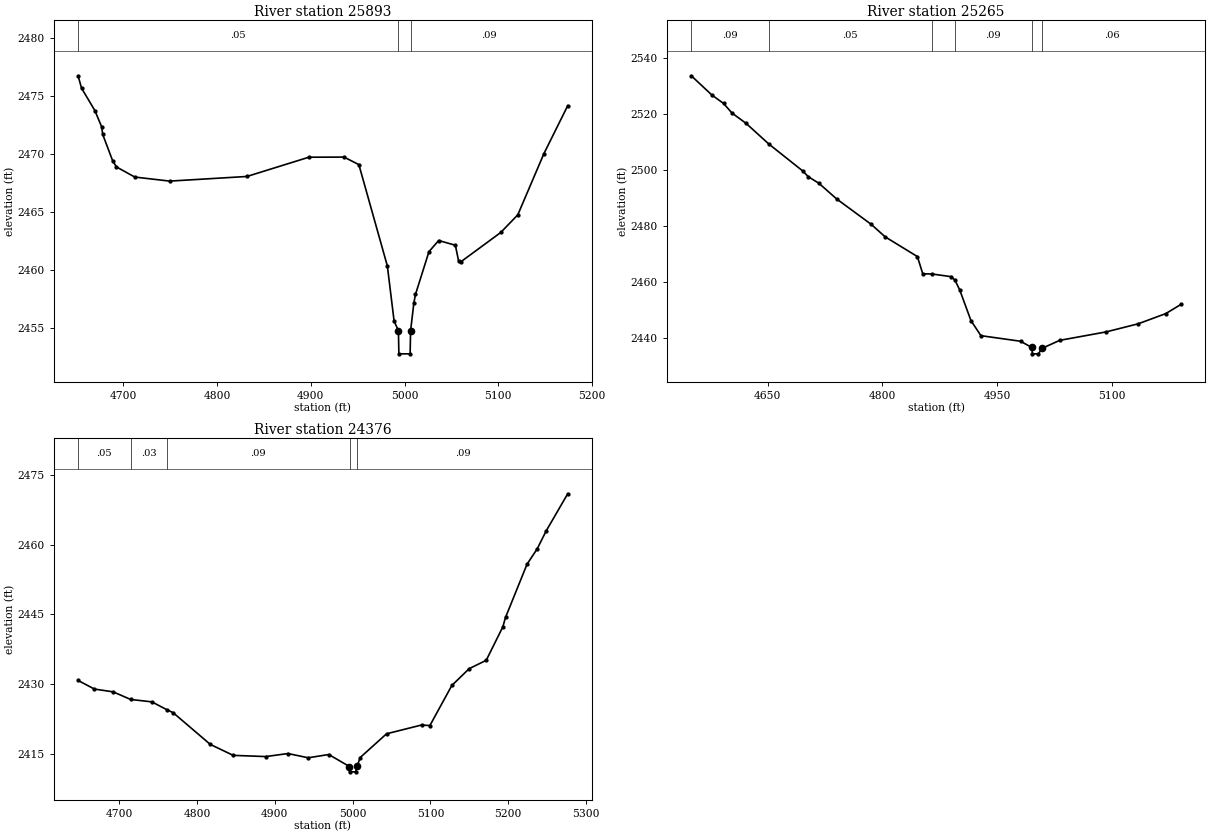
Type RM Length L Ch R = 1 ,25893   ,628,628,628
BEGIN DESCRIPTION:
xs31
END DESCRIPTION:
XS GIS Cut Line= 5
        959095.3       791197.85       958993.75       791205.79
       959073.22       791391.23       959094.41       791451.27
       959158.87       791592.56
#Sta/Elev= 30
  4651.6 2476.78  4655.3 2475.71  4669.6 2473.77  4676.8 2472.37  4677.9 2471.72
  4688.5 2469.45  4692.6 2468.92  4712.1 2468.05  4749.4  2467.7  4831.8  2468.1
  4897.9 2469.76  4935.5 2469.77  4951.3 2469.12  4981.7 2460.38  4988.9 2455.63
  4993.5 2454.81    4994 2452.81    5006 2452.81  5006.5 2454.81    5010  2457.2
  5011.7 2457.93  5026.1 2461.62  5036.5 2462.58  5054.3 2462.17  5057.7 2460.82
  5060.4 2460.76  5102.7 2463.27  5120.9 2464.79  5148.8 2470.07  5174.2  2474.2
#Mann= 3 ,-1 , 0
  4651.6     .05       0  4993.5     .05       0  5006.5     .09       0
#XS Ineff= 2 , 0
       0    4958    2462    5042       0    2462
Permanent Ineff=
       F       F
Bank Sta=4993.5,5006.5
Exp/Cntr=0.5,0.3

Type RM Length L Ch R = 1 ,25265   ,889,889,889
BEGIN DESCRIPTION:
xs32
END DESCRIPTION:
XS GIS Cut Line= 6
       959207.44       790900.27       958908.98       790915.28
       958833.92       790930.29       958740.32       790943.53
       958721.78       790965.61       958720.89       791106.89
#Sta/Elev= 30
  4550.1 2533.51  4577.1 2526.62  4592.2 2523.66  4603.2 2520.25  4621.8 2516.52
  4651.5 2509.16  4695.5 2499.63  4703.1 2497.51    4717 2495.16    4740 2489.61
  4785.3 2480.53  4803.5 2476.08  4845.7 2469.03  4852.7 2462.88  4864.4 2462.84
  4889.8 2461.87  4894.9  2460.6  4901.2 2457.01  4915.7  2446.2  4928.7 2440.83
  4980.5 2438.84    4995 2436.65  4996.1 2434.35  5003.9 2434.35  5008.5 2436.29
  5031.7 2439.16  5092.2 2442.16  5134.3 2445.06  5170.3 2448.69  5190.2 2451.97
#Mann= 6 ,-1 , 0
  4550.1     .09       0  4651.5     .05       0  4864.4     .03       0
  4894.9     .09       0    4995     .05       0  5008.5     .06       0
Bank Sta=4995,5008.5
Exp/Cntr=0.3,0.1

Type RM Length L Ch R = 1 ,24376   ,444,444,444
BEGIN DESCRIPTION:
xs33
END DESCRIPTION:
XS GIS Cut Line= 6
       958613.16       790199.14       958435.68       790193.85
       958242.29       790270.67       958176.07       790324.53
       958146.93       790368.68       958165.47       790471.12
#Sta/Elev= 30
  4647.3 2430.83  4668.3 2428.98  4692.4 2428.38  4714.8 2426.75  4742.1 2426.23
  4761.1 2424.57  4769.4 2423.91  4817.2 2417.09  4846.6 2414.74  4888.4 2414.48
    4917 2415.13    4943 2414.22  4969.4 2414.92    4996 2412.34  4996.1  2411.2
  5003.9  2411.2 5005.86 2412.43  5009.8 2414.28  5043.6 2419.37  5088.6 2421.26
  5099.3 2421.14  5127.5 2429.75  5149.7 2433.35  5171.7 2435.16    5193 2442.33
  5196.5 2444.37  5224.1 2455.79  5237.4 2459.16  5248.8 2462.98  5276.4 2470.93
#Mann= 5 ,-1 , 0
  4647.3     .05       0  4714.8     .03       0  4761.1     .09       0
  4996.1     .05       0 5005.86     .09       0
Bank Sta=4996,5005.86
Exp/Cntr=0.5,0.3