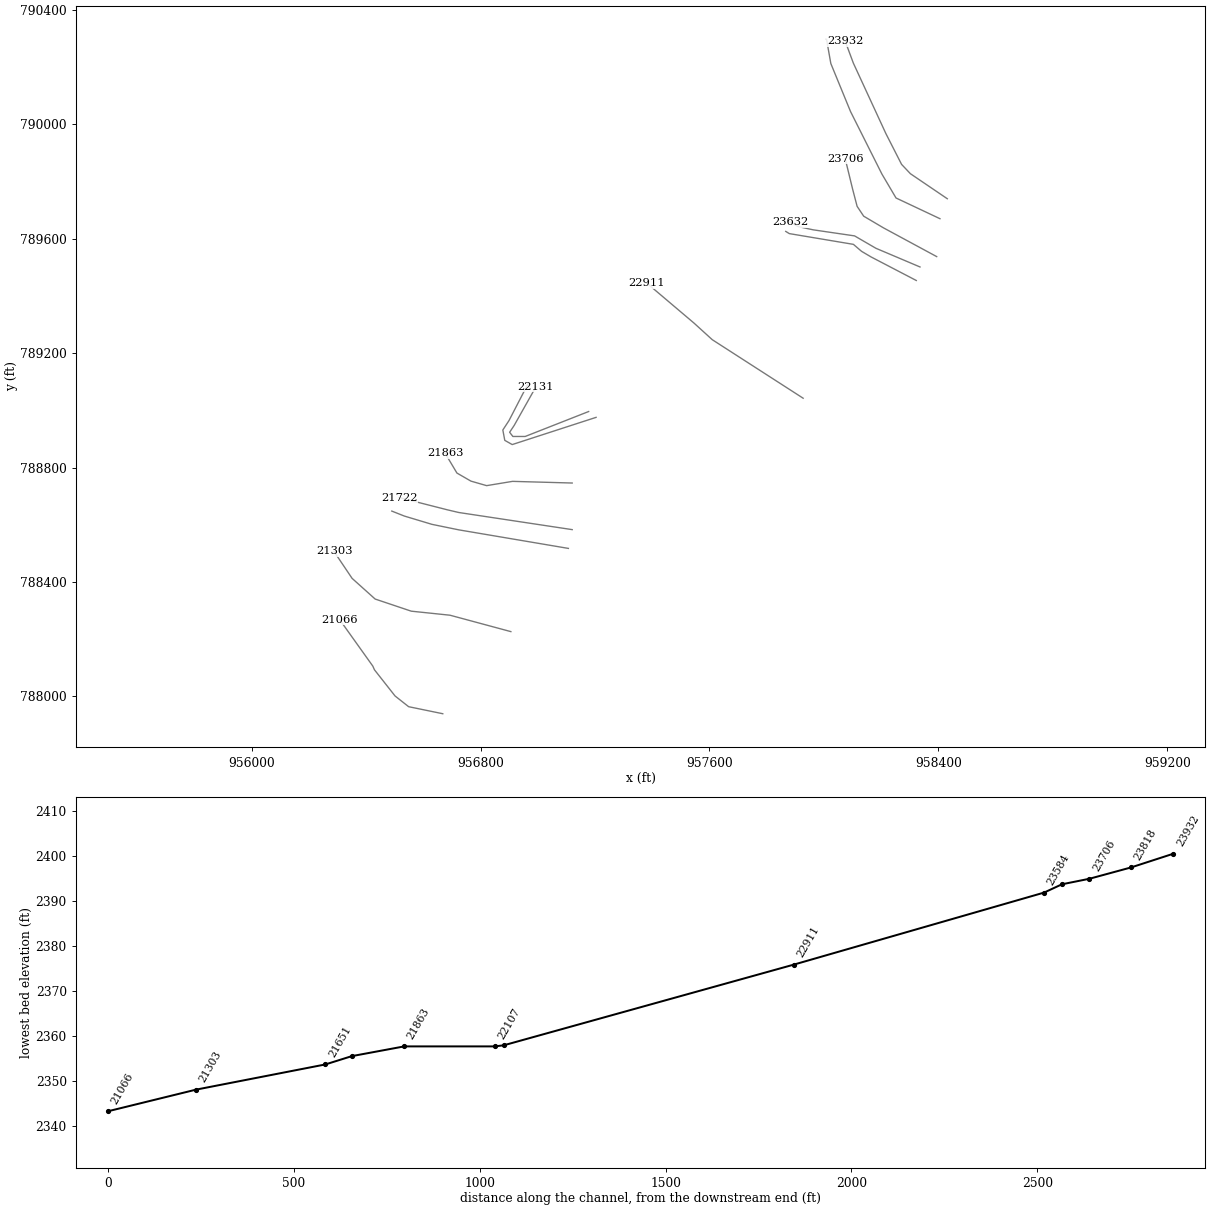
HEC-RAS study lds_california_crk.prj: California Creek Limited Detail Study

--- lds_california_crk.g01 (geometry) --- (continued)

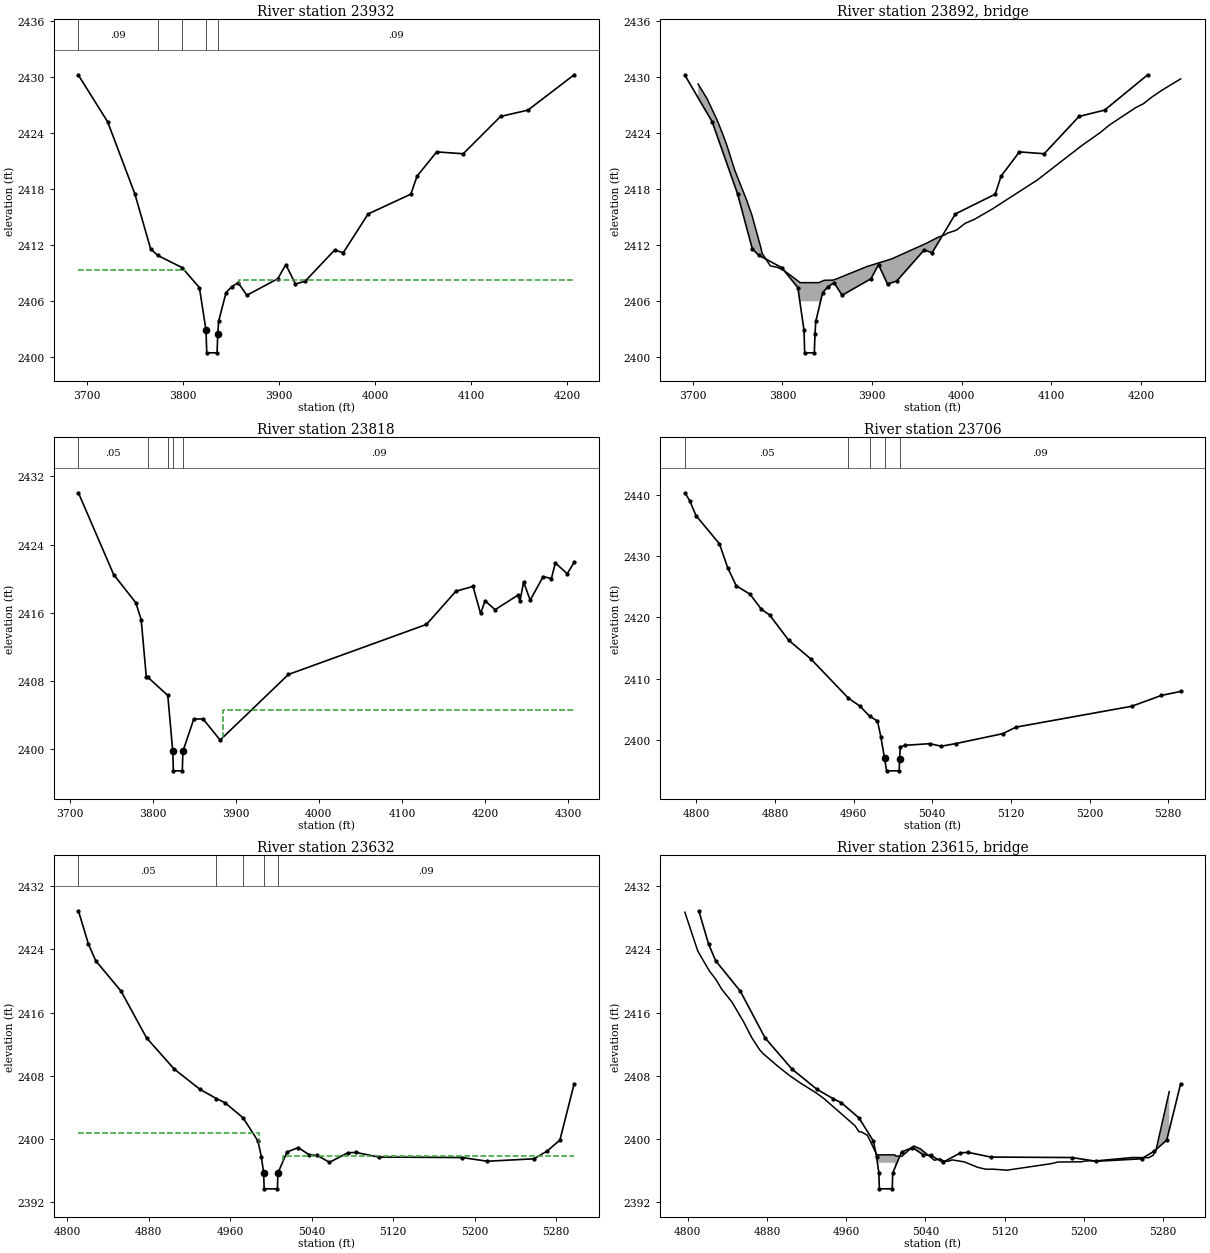
Type RM Length L Ch R = 1 ,23932   ,114,114,114
BEGIN DESCRIPTION:
xs34
END DESCRIPTION:
XS GIS Cut Line= 6
       958431.26       789739.09       958302.34       789826.51
       958271.43       789859.18       958216.66       789966.63
       958102.78       790213.27       958074.52       790289.21
#Sta/Elev= 30
3691.185  2430.23721.597 2425.223749.941 2417.513766.411 2411.623773.688 2410.92
3799.198 2409.613817.199 2407.473824.094  2402.9 3824.86 2400.493835.584 2400.49
3836.351 2402.493837.193 2403.85 3844.93 2406.933850.676 2407.55 3857.57 2407.99
3866.609 2406.65 3898.86 2408.42 3907.21 2409.933917.245 2407.85 3927.51 2408.17
3958.152  2411.53966.961 2411.19 3992.93 2415.354037.437 2417.474043.872 2419.39
4064.325 2421.99 4091.98 2421.794130.818 2425.784159.392 2426.464207.499 2430.24
#Mann= 5 ,-1 , 0
3691.185     .09       03773.688     .03       03799.198     .09       0
3824.094     .05       03836.351     .09       0
#XS Ineff= 2 , 0
       03802.261  2409.33858.183       0 2408.33
Permanent Ineff=
       F       F
Bank Sta=3824.094,3836.351
Skew Angle= 40
Exp/Cntr=0.5,0.3

Type RM Length L Ch R = 3 ,23892   ,,,
BEGIN DESCRIPTION:
xs35
Structure ID: Chadler creek Rd
Approximate Survey Structure
END DESCRIPTION:
Bridge Culvert--1,0,-1,-1, 0
Deck Dist Width WeirC Skew NumUp NumDn MinLoCord MaxHiCord MaxSubmerge Is_Ogee
23,34,3,40, 39, 37, , , , 0, 0.5,0.5,,
 3705.973715.8523727.1893733.0113737.8373746.8773760.3593766.028 3775.913777.442
3786.5583793.9123800.8063819.8813819.8813840.5643840.5643846.6153856.1143859.026
3894.4933921.8413960.8333973.9323981.4393983.8913993.9264003.9614014.0734034.143
4084.3194134.4184154.4894164.524 4193.484202.4434212.7854223.7394244.192
 2429.25  2427.7 2425.39    2424 2422.75 2420.02 2416.76 2415.21 2411.76 2411.13
 2409.79 2409.65 2409.37    2408    2408    2408    2408 2408.25 2408.27 2408.35
 2409.73 2410.54 2412.22 2412.87 2413.12 2413.29 2413.61 2414.35 2414.77 2415.88
 2418.98  2422.7 2424.05 2424.85 2426.69 2427.13  2427.9 2428.61  2429.8
    2379    2379    2379    2379    2379    2379    2379    2379    2379    2379
    2379    2379    2379    2379    2406    2406    2379    2379    2379    2379
    2379    2379    2379    2379    2379    2379    2379    2379    2379    2379
    2379    2379    2379    2379    2379    2379    2379    2379    2379
 3705.973715.8523727.1893733.0113737.8373746.8773760.3593766.028 3775.913777.442
3786.5583793.9123800.8063819.8813819.8813840.5643840.5643923.0673981.4393983.891
3993.9264003.9614014.0734034.1434044.255 4054.294064.0954074.284 4095.124134.418
4154.4894164.524 4193.484202.4434212.7854223.7394244.192
 2429.25  2427.7 2425.39    2424 2422.75 2420.02 2416.76 2415.21 2411.76 2411.13
 2409.79 2409.65 2409.37    2405    2405    2405    2405    2406 2413.12 2413.29
 2413.61 2414.35 2414.77 2415.88 2416.54 2417.09 2417.77 2418.34 2419.74  2422.7
 2424.05 2424.85 2426.69 2427.13  2427.9 2428.61  2429.8
    2379    2379    2379    2379    2379    2379    2379    2379    2379    2379
    2379    2379    2379    2379    2403    2403    2379    2379    2379    2379
    2379    2379    2379    2379    2379    2379    2379    2379    2379    2379
    2379    2379    2379    2379    2379    2379    2379
BR Coef= 1 , 1 , 0 ,1.25, 0 ,,,0.8,0,2,0,
WSPro=,,,, 1 ,,,, 0 ,,,, 0 ,,,,-1 ,-1 ,-1 , 0 , 0 , 0 , 0 , 0
BC Design=,, 0 ,, 0 ,,,,,,
BC HTab HWMax=2430.24

Type RM Length L Ch R = 1 ,23818   ,112,112,112
BEGIN DESCRIPTION:
xs36
END DESCRIPTION:
XS GIS Cut Line= 6
       958405.65       789669.33       958252.01       789741.74
       958202.56       789825.62       958093.06       790043.73
       958024.19       790211.51       958009.18       790296.28
#Sta/Elev= 30
 3710.49 2430.073752.928 2420.483779.587 2417.173786.098 2415.183792.226 2408.48
3793.758 2408.453818.119 2406.293824.094 2399.75 3824.86 2397.443835.584 2397.44
3836.351 2399.75 3849.45 2403.523860.558 2403.533881.164 2401.053963.361 2408.75
4129.516 2414.62 4165.06 2418.52 4185.59 2419.084194.706 2415.914200.145 2417.39
4212.172 2416.354239.596 2418.054242.125 2417.364246.567  2419.64254.458 2417.46
4270.085 2420.244279.967    24204284.716 2421.844299.042 2420.574307.391 2421.91
#Mann= 5 ,-1 , 0
 3710.49     .05       03793.758     .03       03818.119     .09       0
3824.094     .05       03836.351     .09       0
#XS Ineff= 2 , 0
       03776.216  2404.63884.228       0  2404.6
Permanent Ineff=
       F       F
Bank Sta=3824.094,3836.351
Skew Angle= 40
Exp/Cntr=0.5,0.3

Type RM Length L Ch R = 1 ,23706   ,74,74,74
BEGIN DESCRIPTION:
xs37
END DESCRIPTION:
XS GIS Cut Line= 6
       958394.17       789536.88         958208.       789637.45
       958138.98       789678.16       958116.02        789712.6
       958100.13       789773.53       958074.52       789878.61
#Sta/Elev= 30
  4788.4 2440.35  4793.3 2439.07  4799.8 2436.61  4823.6 2432.01    4832 2428.09
  4840.7 2425.15  4854.7 2423.78  4866.3  2421.3  4874.5 2420.41  4893.9 2416.28
  4916.7 2413.18  4954.5 2406.84  4966.5 2405.49  4976.3 2403.86  4984.3 2403.06
  4987.7 2400.51 4991.49 2396.96  4993.6 2394.93  5006.4 2394.93 5006.73 2396.86
  5007.5 2398.81  5012.4  2399.1  5037.6 2399.37  5049.1 2398.95  5064.2 2399.39
  5111.7    2401  5125.2 2402.07  5242.9 2405.48  5273.1 2407.25  5292.6  2407.9
#Mann= 5 ,-1 , 0
  4788.4     .05       0  4954.5     .03       0  4976.3     .09       0
 4991.49     .05       0 5006.73     .09       0
Bank Sta=4991.49,5006.73
Exp/Cntr=0.5,0.3

Type RM Length L Ch R = 1 ,23632   ,48,48,48
BEGIN DESCRIPTION:
xs38
END DESCRIPTION:
XS GIS Cut Line= 6
       958335.89       789500.67       958181.68       789566.02
       958107.19       789609.28       957962.37       789630.48
       957909.39       789641.96       957882.02       789657.85
#Sta/Elev= 30
  4811.2 2428.87    4821 2424.68  4828.2 2422.55  4853.1  2418.7  4878.1 2412.79
  4905.3 2408.84  4930.7 2406.27  4946.6 2405.12    4955  2404.6  4972.9 2402.67
  4987.4 2399.75  4990.7 2397.79    4993  2395.7  4993.5  2393.7  5006.5  2393.7
    5007  2395.7  5015.9 2398.35  5026.9 2398.92  5037.8    2398  5045.7 2397.92
  5057.6 2397.05  5075.4 2398.25  5083.3 2398.31  5105.9 2397.72  5187.7 2397.66
  5212.5 2397.19  5258.2  2397.5  5271.2 2398.48  5283.7 2399.87  5297.7 2406.98
#Mann= 5 ,-1 , 0
  4811.2     .05       0  4946.6     .03       0  4972.9     .09       0
    4993     .05       0    5007     .09       0
#XS Ineff= 2 , 0
       0    4988 2400.72    5012       0 2397.84
Permanent Ineff=
       F       F
Bank Sta=4993,5007
Exp/Cntr=0.5,0.3

Type RM Length L Ch R = 3 ,23615   ,,,
BEGIN DESCRIPTION:
xs39
Structure ID: Missing structure
Approximate Survey Structure
END DESCRIPTION:
Bridge Culvert--1,0,-1,-1, 0
Deck Dist Width WeirC Skew NumUp NumDn MinLoCord MaxHiCord MaxSubmerge Is_Ogee
3,28,3,0, 48, 49, , , , 0, 1,1,,
  4797.1  4810.2  4821.9  4828.6  4834.3  4844.7  4856.7  4864.5  4872.4  4875.8
  4889.3  4902.4  4913.7  4929.9  4937.6    4969  4972.8  4975.3  4981.4    4991
    4991    5009    5009  5009.8  5016.1  5028.2  5034.9  5049.2  5054.7  5058.9
  5063.6  5067.1  5079.3  5092.6    5101  5108.2  5122.3  5166.8  5173.7  5198.1
    5200  5206.5  5209.6  5249.5  5265.4  5269.8  5272.9  5286.2
 2428.69 2423.76 2421.25 2420.16 2418.95 2417.32 2414.76 2412.85 2411.33 2410.84
 2409.38 2408.07 2407.09 2405.82 2405.11 2401.67 2400.94  2400.9 2400.48    2398
    2398    2398    2398 2397.86 2397.81 2399.12 2398.76 2397.31 2397.51 2397.18
 2397.21 2397.36 2397.11 2396.43 2396.18 2396.19 2396.06 2396.88 2397.09 2397.12
  2397.2 2397.26 2397.21 2397.67 2397.64 2397.93 2398.64    2406
  2373.7  2373.7  2373.7  2373.7  2373.7  2373.7  2373.7  2373.7  2373.7  2373.7
  2373.7  2373.7  2373.7  2373.7  2373.7  2373.7  2373.7  2373.7  2373.7  2373.7
    2397    2397  2373.7  2373.7  2373.7  2373.7  2373.7  2373.7  2373.7  2373.7
  2373.7  2373.7  2373.7  2373.7  2373.7  2373.7  2373.7  2373.7  2373.7  2373.7
  2373.7  2373.7  2373.7  2373.7  2373.7  2373.7  2373.7  2373.7
    4766  4797.1  4810.2  4821.9  4828.6  4834.3  4844.7  4856.7  4864.5  4872.4
  4875.8  4889.3  4902.4  4913.7  4929.9  4937.6    4969  4972.8  4975.3  4981.4
    4991    4991    5009    5009  5009.8  5016.1  5028.2  5034.9  5049.2  5054.7
  5058.9  5063.6  5067.1  5079.3  5092.6    5101  5108.2  5122.3  5166.8  5173.7
  5198.1    5200  5206.5  5209.6  5249.5  5265.4  5269.8  5272.9  5286.2
 2430.71 2428.69 2423.76 2421.25 2420.16 2418.95 2417.32 2414.76 2412.85 2411.33
 2410.84 2409.38 2408.07 2407.09 2405.82 2405.11 2401.67 2400.94  2400.9 2400.48
    2398    2398    2398    2398 2397.86 2397.81 2399.12 2398.76 2397.31 2397.51
 2397.18 2397.21 2397.36 2397.11 2396.43 2396.18 2396.19 2396.06 2396.88 2397.09
 2397.12  2397.2 2397.26 2397.21 2397.67 2397.64 2397.93 2398.64    2406
  2373.7  2373.7  2373.7  2373.7  2373.7  2373.7  2373.7  2373.7  2373.7  2373.7
  2373.7  2373.7  2373.7  2373.7  2373.7  2373.7  2373.7  2373.7  2373.7  2373.7
  2373.7    2397    2397  2373.7  2373.7  2373.7  2373.7  2373.7  2373.7  2373.7
  2373.7  2373.7  2373.7  2373.7  2373.7  2373.7  2373.7  2373.7  2373.7  2373.7
  2373.7  2373.7  2373.7  2373.7  2373.7  2373.7  2373.7  2373.7  2373.7
BR Coef= 1 , 1 , 0 ,1.25, 0 ,,,0.8,0,2,0,
WSPro=,,,, 1 ,,,, 0 ,,,, 0 ,,,,-1 ,-1 ,-1 , 0 , 0 , 0 , 0 , 0
BC Design=,, 0 ,, 0 ,,,,,,
BC HTab HWMax=2428.87

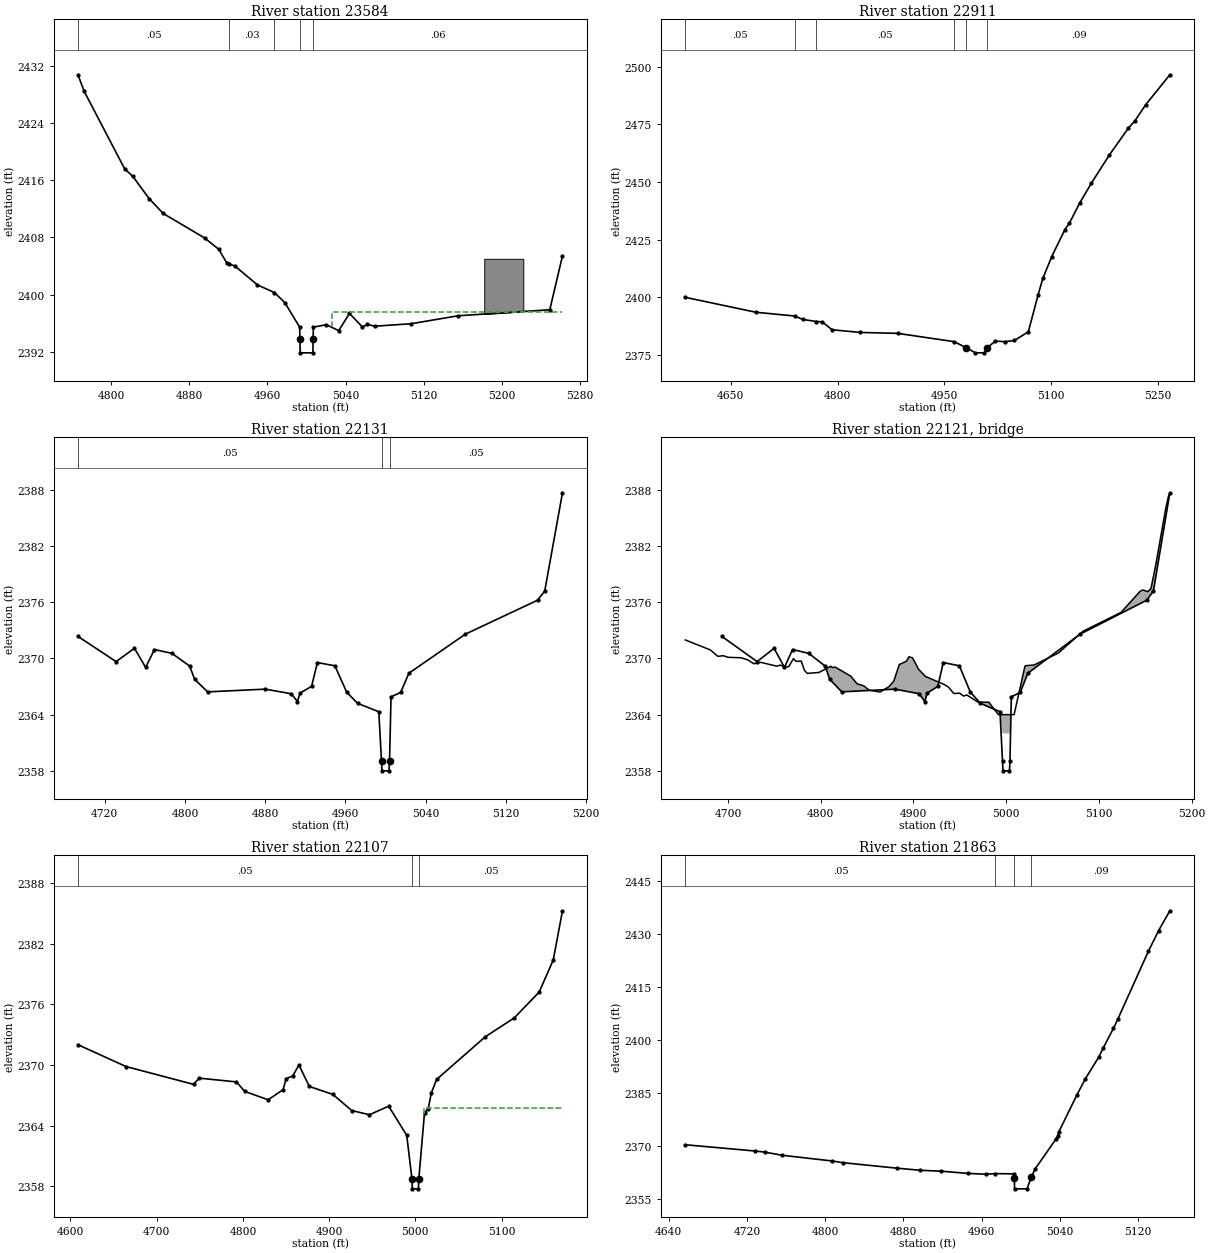
Type RM Length L Ch R = 1 ,23584   ,673,673,673
BEGIN DESCRIPTION:
xs40
END DESCRIPTION:
XS GIS Cut Line= 6
       958322.86       789453.43         958165.       789535.64
       958131.65        789555.3       958103.05       789579.72
       957879.08       789617.25       957866.57       789624.99
#Sta/Elev= 30
    4766 2430.71  4772.3 2428.42  4813.8 2417.57  4822.3  2416.5  4838.8 2413.42
  4853.2 2411.34  4895.7 2407.91  4910.3 2406.31  4918.1 2404.48    4921 2404.25
  4926.5 2404.01  4949.8 2401.35  4967.2 2400.28  4977.8 2398.88    4993 2395.45
  4993.3 2393.74  4993.5 2391.86  5006.5 2391.86 5006.82 2393.78    5007 2395.45
  5020.3 2395.79    5033 2394.96    5044 2397.37  5057.2 2395.48  5062.3 2395.82
  5069.9 2395.58  5107.3 2395.93  5155.2 2397.04  5249.1 2397.88  5262.1 2405.41
#Mann= 5 ,-1 , 0
    4766     .05       0    4921     .03       0  4967.2     .09       0
  4993.3     .05       0 5006.82     .06       0
#XS Ineff= 2 , 0
       0    4974  2397.5    5026       0  2397.5
Permanent Ineff=
       F       F
#Block Obstruct= 1 ,-1
    5182    5222    2405
Bank Sta=4993.3,5006.82
Exp/Cntr=0.5,0.3

Type RM Length L Ch R = 1 ,22911   ,780,780,780
BEGIN DESCRIPTION:
100
END DESCRIPTION:
XS GIS Cut Line= 4
       957927.41       789042.11       957609.86       789246.55
       957546.08       789304.54       957380.69       789444.53
#Sta/Elev= 30
  4586.2 2399.98  4685.2 2393.51  4739.8 2391.87  4751.5 2390.36  4770.3 2389.49
  4778.6 2389.33  4792.4  2385.9  4831.8 2384.75  4884.6 2384.34  4963.9 2380.74
 4981.13 2378.06  4993.6 2375.89  5006.4 2375.89  5009.9 2378.02  5021.8 2380.99
  5035.8 2380.72  5048.5 2381.27    5068    2385  5081.8 2401.09  5088.4 2408.18
  5100.9 2417.65  5119.4  2429.4  5125.5 2432.05  5140.1 2440.84  5156.3 2449.38
  5181.6 2461.64  5208.5 2473.38  5217.8  2476.6    5233 2483.61  5266.8 2496.56
#Mann= 6 ,-1 , 0
  4586.2     .05       0  4739.8     .03       0  4770.3     .05       0
  4963.9     .09       0 4981.13     .05       0  5009.9     .09       0
Bank Sta=4981.13,5009.9
Exp/Cntr=0.5,0.3

Type RM Length L Ch R = 1 ,22131   ,24,24,24
BEGIN DESCRIPTION:
201
END DESCRIPTION:
XS GIS Cut Line= 6
       957177.77       788995.58       956955.95       788908.44
       956912.95       788908.44       956901.63       788923.15
       956917.48       788946.92        956993.3       789081.59
#Sta/Elev= 30
  4693.4 2372.35  4731.4 2369.66  4749.7 2371.08  4760.9 2369.04  4769.6 2370.95
  4787.1 2370.54  4804.8 2369.18  4809.7 2367.77  4822.7 2366.43    4880 2366.72
  4906.1 2366.23  4912.2  2365.4  4914.8  2366.3  4926.3 2367.02  4932.1 2369.56
  4949.5 2369.21  4961.3  2366.4  4972.2  2365.2  4993.3 2364.31    4996    2359
  4996.5    2358  5003.5    2358    5004    2359  5005.5  2365.9  5015.1 2366.37
  5023.3 2368.42  5079.6 2372.59  5151.5 2376.21  5158.7 2377.19  5176.4 2387.68
#Mann= 3 ,-1 , 0
  4693.4     .05       0    4996     .05       0    5004     .05       0
#XS Ineff= 2 , 0
       0    4920          5006.5       0 2364.35
Permanent Ineff=
       T       F
Bank Sta=4996,5004
Exp/Cntr=0.5,0.3

Type RM Length L Ch R = 3 ,22121   ,,,
BEGIN DESCRIPTION:
200
Structure ID: driveway
Approximate Survey Structure
END DESCRIPTION:
Bridge Culvert--1,0,-1,-1, 0
Deck Dist Width WeirC Skew NumUp NumDn MinLoCord MaxHiCord MaxSubmerge Is_Ogee
1,18,3,0, 60, 60, , , , 0, 0.5,0.5,,
    4654  4681.1  4689.1  4694.8  4700.1  4714.1  4721.5  4727.8  4735.4  4752.6
  4756.4    4761  4765.4  4770.6  4773.5    4779  4782.4  4785.5    4798  4810.8
  4812.5  4815.7  4832.4  4839.2  4846.5  4852.1    4864  4873.7  4878.8  4884.7
  4892.3  4895.1  4898.9  4905.6  4912.9  4933.5  4937.9  4943.4  4949.9  4953.9
  4957.6  4969.6  4981.2  4991.5  4991.5  5008.5  5008.5  5020.1  5020.6  5030.1
  5056.3  5082.8  5123.9  5144.1  5147.2  5152.7  5156.1  5161.2  5172.2  5175.2
 2371.97  2370.9 2370.22 2370.29 2370.12 2370.07 2369.84 2369.43 2369.58 2369.17
 2369.29 2369.09 2369.12 2369.97 2369.68 2369.72 2368.73  2368.4  2368.5 2369.16
 2369.03 2369.07  2368.1 2367.29 2367.07 2366.61 2366.41    2367 2367.58 2369.35
 2369.69 2370.17 2370.07 2368.83 2368.08  2367.2 2366.92 2366.25 2366.29 2365.98
 2366.09 2365.33 2365.33    2364    2364    2364    2364 2369.13 2369.22  2369.3
 2370.58  2372.9 2374.92 2377.14 2377.31 2377.13 2377.48 2379.97 2386.13 2387.42
    2338    2338    2338    2338    2338    2338    2338    2338    2338    2338
    2338    2338    2338    2338    2338    2338    2338    2338    2338    2338
    2338    2338    2338    2338    2338    2338    2338    2338    2338    2338
    2338    2338    2338    2338    2338    2338    2338    2338    2338    2338
    2338    2338    2338    2338    2362    2362    2338    2338    2338    2338
    2338    2338    2338    2338    2338    2338    2338    2338    2338    2338
    4654  4681.1  4689.1  4694.8  4700.1  4714.1  4721.5  4727.8  4735.4  4752.6
  4756.4    4761  4765.4  4770.6  4773.5    4779  4782.4  4785.5    4798  4810.8
  4812.5  4815.7  4832.4  4839.2  4846.5  4852.1    4864  4873.7  4878.8  4884.7
  4892.3  4895.1  4898.9  4905.6  4912.9  4933.5  4937.9  4943.4  4949.9  4953.9
  4957.6  4969.6  4981.2  4991.5  4991.5  5008.5  5008.5  5020.1  5020.6  5030.1
  5056.3  5082.8  5123.9  5144.1  5147.2  5152.7  5156.1  5161.2  5172.2  5175.2
 2371.97  2370.9 2370.22 2370.29 2370.12 2370.07 2369.84 2369.43 2369.58 2369.17
 2369.29 2369.09 2369.12 2369.97 2369.68 2369.72 2368.73  2368.4  2368.5 2369.16
 2369.03 2369.07  2368.1 2367.29 2367.07 2366.61 2366.41    2367 2367.58 2369.35
 2369.69 2370.17 2370.07 2368.83 2368.08  2367.2 2366.92 2366.25 2366.29 2365.98
 2366.09 2365.33 2365.33    2364    2364    2364    2364 2369.13 2369.22  2369.3
 2370.58  2372.9 2374.92 2377.14 2377.31 2377.13 2377.48 2379.97 2386.13 2387.42
    2338    2338    2338    2338    2338    2338    2338    2338    2338    2338
    2338    2338    2338    2338    2338    2338    2338    2338    2338    2338
    2338    2338    2338    2338    2338    2338    2338    2338    2338    2338
    2338    2338    2338    2338    2338    2338    2338    2338    2338    2338
    2338    2338    2338    2338    2362    2362    2338    2338    2338    2338
    2338    2338    2338    2338    2338    2338    2338    2338    2338    2338
BR Coef= 1 , 1 , 0 ,1.25, 0 ,,,0.8,0,2,0,
WSPro=,,,, 1 ,,,, 0 ,,,, 0 ,,,,-1 ,-1 ,-1 , 0 , 0 , 0 , 0 , 0
BC Design=,, 0 ,, 0 ,,,,,,
BC HTab HWMax=2387.68

Type RM Length L Ch R = 1 ,22107   ,244,244,244
BEGIN DESCRIPTION:
202
END DESCRIPTION:
XS GIS Cut Line= 6
        957203.8       788975.21       956910.69       788880.15
       956884.66       788894.86       956877.87       788931.08
       956899.37       788963.89       956967.27       789095.17
#Sta/Elev= 30
  4608.7 2372.01  4664.4 2369.85  4742.7 2368.09  4749.4  2368.7  4792.5 2368.33
  4802.1 2367.39  4829.2 2366.56  4846.6 2367.56  4850.1 2368.65  4857.7 2368.91
    4865    2370    4877 2367.88  4904.4 2367.09  4926.1  2365.5  4946.8 2365.08
    4969 2365.93    4990 2363.04    4996 2358.75  4996.5 2357.75  5003.5 2357.75
    5004 2358.75  5010.6 2365.28  5014.9 2365.65  5018.4 2367.22  5024.7 2368.58
    5081 2372.79  5114.8 2374.67  5143.5 2377.21  5159.9 2380.39  5170.6 2385.26
#Mann= 3 ,-1 , 0
  4608.7     .05       0    4996     .05       0    5004     .05       0
#XS Ineff= 2 , 0
       0    4945          5010.5       0 2365.76
Permanent Ineff=
       T       F
Bank Sta=4996,5004
Exp/Cntr=0.5,0.3

Type RM Length L Ch R = 1 ,21863   ,141,141,141
BEGIN DESCRIPTION:
xs46
END DESCRIPTION:
XS GIS Cut Line= 6
       957120.32       788745.77       956911.81       788751.58
       956821.25       788736.63       956766.43       788752.41
       956717.41       788780.66       956675.88       788850.44
#Sta/Elev= 30
    4657 2370.25  4728.5 2368.47    4738 2368.17    4756 2367.27  4807.3 2365.64
    4818 2365.17  4873.3 2363.61  4897.3 2363.01  4918.9 2362.75  4946.2 2362.12
  4964.3  2361.9  4974.1 2362.06  4993.3    2362 4993.45 2360.87  4993.6 2357.75
  5006.4 2357.75 5010.67 2360.98  5014.6 2363.38  5035.8 2371.79  5037.6 2372.65
  5038.6 2373.74  5057.5 2384.43    5066 2388.95  5079.9 2395.18  5084.2 2397.66
  5094.7 2403.22  5099.2 2405.86  5130.5 2425.12  5140.9 2430.95  5152.4 2436.58
#Mann= 4 ,-1 , 0
    4657     .05       0  4974.1     .09       0  4993.3     .05       0
 5010.67     .09       0
Bank Sta=4993.45,5010.67
Exp/Cntr=0.5,0.3

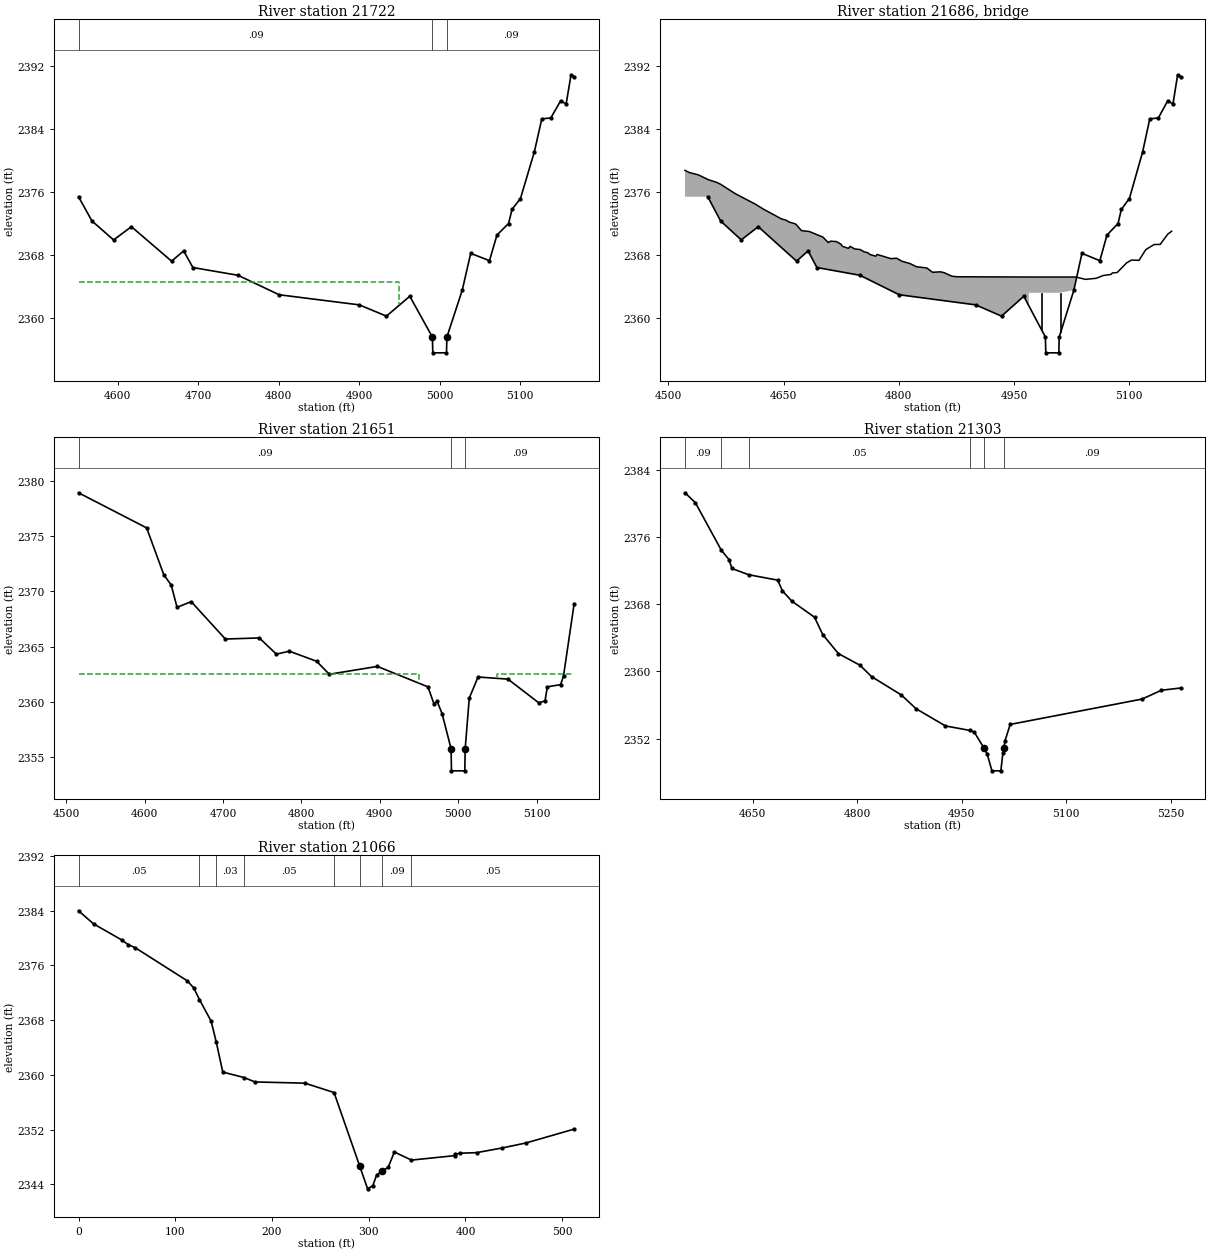
Type RM Length L Ch R = 1 ,21722   ,71,71,71
BEGIN DESCRIPTION:
xs47
END DESCRIPTION:
XS GIS Cut Line= 5
       957120.32       788582.94       956724.06       788642.76
       956685.01        788651.9       956645.97       788661.86
       956515.54       788695.09
#Sta/Elev= 30
  4551.4 2375.37  4568.1  2372.3    4595  2369.9  4617.1 2371.58    4667 2367.21
    4682 2368.51  4693.5  2366.4  4749.5 2365.42  4800.7 2362.95  4900.2 2361.67
  4933.9 2360.24  4962.9 2362.76    4991 2357.59  4991.5 2355.59  5008.5 2355.59
    5009 2357.59  5028.1 2363.54  5038.6  2368.2  5061.9 2367.27  5071.2 2370.52
  5085.6 2371.98  5089.9 2373.77  5100.4 2375.15  5117.6 2381.05  5126.9 2385.24
  5138.1 2385.36  5150.4 2387.55  5157.1 2387.11  5163.2 2390.83  5167.1 2390.54
#Mann= 3 ,-1 , 0
  4551.4     .09       0    4991     .05       0    5009     .09       0
#XS Ineff= 2 , 0
       0  4949.5  2364.6  5050.5       0 2364.93
Permanent Ineff=
       F       F
Bank Sta=4991,5009
Exp/Cntr=0.5,0.3

Type RM Length L Ch R = 3 ,21686   ,,,
BEGIN DESCRIPTION:
xs48
Structure ID: sprinkle Crk Rd
Approximate Survey Structure
END DESCRIPTION:
Bridge Culvert--1,0,-1,-1, 0
Deck Dist Width WeirC Skew NumUp NumDn MinLoCord MaxHiCord MaxSubmerge Is_Ogee
20,32,3,0, 59, 59, , , , 0, 0.5,0.5,,
  4521.7  4527.3    4539  4552.7  4562.1    4568  4587.2  4613.4  4623.9  4647.8
  4652.7    4657  4665.8  4673.4  4683.7  4701.3  4708.2  4711.4  4718.9  4725.1
  4726.3  4734.4  4736.8  4742.7  4749.9  4754.7  4759.7  4762.5  4770.2    4772
  4789.7  4797.2  4804.2  4814.8  4823.2  4836.5  4844.1  4854.2  4858.9    4869
  4876.2  4969.5  4969.5  5030.5  5030.5  5043.3  5057.3  5066.3  5076.2  5078.2
  5084.5  5096.9  5103.2  5112.9  5121.7  5132.6  5140.5  5150.3  5155.4
 2378.72 2378.44 2378.15 2377.51 2377.23 2376.96 2375.76 2374.43  2373.8 2372.54
 2372.43 2372.18 2371.92 2371.08 2370.96 2370.26 2369.57 2369.74 2369.69 2369.34
 2369.11 2368.83 2369.08 2368.76 2368.68  2368.4 2368.28 2368.05 2367.84 2368.06
 2367.53 2367.58  2367.2  2366.9  2366.5 2366.35  2365.8 2365.86 2365.76 2365.31
 2365.23  2365.2  2365.2  2365.2  2365.2  2364.9 2365.04 2365.39 2365.52 2365.71
 2365.77    2367 2367.35 2367.31 2368.67 2369.32 2369.33 2370.63    2371
    2334    2334    2334    2334    2334    2334    2334    2334    2334    2334
    2334    2334    2334    2334    2334    2334    2334    2334    2334    2334
    2334    2334    2334    2334    2334    2334    2334    2334    2334    2334
    2334    2334    2334    2334    2334    2334    2334    2334    2334    2334
    2334    2334  2363.2  2363.2    2334    2334    2334    2334    2334    2334
    2334    2334    2334    2334    2334    2334    2334    2334    2334
  4521.7  4527.3    4539  4552.7  4562.1    4568  4587.2  4613.4  4623.9  4647.8
  4652.7    4657  4665.8  4673.4  4683.7  4701.3  4708.2  4711.4  4718.9  4725.1
  4726.3  4734.4  4736.8  4742.7  4749.9  4754.7  4759.7  4762.5  4770.2    4772
  4789.7  4797.2  4804.2  4814.8  4823.2  4836.5  4844.1  4854.2  4858.9    4869
  4876.2  4969.5  4969.5  5030.5  5030.5  5043.3  5057.3  5066.3  5076.2  5078.2
  5084.5  5096.9  5103.2  5112.9  5121.7  5132.6  5140.5  5150.3  5155.4
 2378.72 2378.44 2378.15 2377.51 2377.23 2376.96 2375.76 2374.43  2373.8 2372.54
 2372.43 2372.18 2371.92 2371.08 2370.96 2370.26 2369.57 2369.74 2369.69 2369.34
 2369.11 2368.83 2369.08 2368.76 2368.68  2368.4 2368.28 2368.05 2367.84 2368.06
 2367.53 2367.58  2367.2  2366.9  2366.5 2366.35  2365.8 2365.86 2365.76 2365.31
 2365.23  2365.2  2365.2  2365.2  2365.2  2364.9 2365.04 2365.39 2365.52 2365.71
 2365.77    2367 2367.35 2367.31 2368.67 2369.32 2369.33 2370.63    2371
    2334    2334    2334    2334    2334    2334    2334    2334    2334    2334
    2334    2334    2334    2334    2334    2334    2334    2334    2334    2334
    2334    2334    2334    2334    2334    2334    2334    2334    2334    2334
    2334    2334    2334    2334    2334    2334    2334    2334    2334    2334
    2334    2334  2363.2  2363.2    2334    2334    2334    2334    2334    2334
    2334    2334    2334    2334    2334    2334    2334    2334    2334
Pier Skew, UpSta & Num, DnSta & Num=  ,4986, 2 ,4986, 2 , 0 , 0 , 0 ,0,0
       1       1
 2358.13  2363.2
       1       1
 2357.06  2363.2
Pier Skew, UpSta & Num, DnSta & Num=  ,5011, 2 ,5011, 2 , 0 , 0 , 0 ,0,0
       1       1
 2358.98  2363.2
       1       1
 2358.57  2363.2
BR Coef= 1 , 1 , 0 ,1.25, 0 ,,,0.8,0,2,0,
WSPro=,,,, 1 ,,,, 0 ,,,, 0 ,,,,-1 ,-1 ,-1 , 0 , 0 , 0 , 0 , 0
BC Design=,, 0 ,, 0 ,,,,,,
BC HTab HWMax=2390.83

Type RM Length L Ch R = 1 ,21651   ,348,348,348
BEGIN DESCRIPTION:
xs49
END DESCRIPTION:
XS GIS Cut Line= 5
       957107.03       788517.32       956724.06       788582.11
       956630.18       788601.38       956533.82        788630.3
       956489.79       788647.74
#Sta/Elev= 30
  4515.8 2378.94  4602.7 2375.76  4624.6 2371.51    4634 2370.59  4641.5 2368.56
  4659.5 2369.08  4703.1 2365.69  4746.4 2365.79  4768.2 2364.32  4784.6 2364.59
  4819.4 2363.68  4835.7  2362.5    4897 2363.21  4961.5 2361.36  4969.3 2359.79
    4973 2360.08  4979.5 2358.94    4991 2355.75  4991.5 2353.75  5008.5 2353.75
    5009 2355.75  5014.2 2360.34  5025.4 2362.25  5063.5 2362.06  5102.7 2359.92
  5110.8 2360.08  5113.8 2361.36  5130.7 2361.56  5134.4 2362.34    5148  2368.9
#Mann= 3 ,-1 , 0
  4515.8     .09       0    4991     .05       0    5009     .09       0
#XS Ineff= 2 , 0
       0  4950.5  2362.5  5049.5       0  2362.5
Permanent Ineff=
       F       F
Bank Sta=4991,5009
Exp/Cntr=0.5,0.3

Type RM Length L Ch R = 1 ,21303   ,237,237,237
BEGIN DESCRIPTION:
xs50
END DESCRIPTION:
XS GIS Cut Line= 6
       956905.99       788226.56       956693.32       788283.88
       956557.91         788298.       956431.64       788340.37
       956351.06       788412.64       956287.92       788506.52
#Sta/Elev= 30
    4553 2381.29    4568  2380.1  4605.2 2374.44  4616.2 2373.33  4620.4 2372.27
  4644.2 2371.53  4686.1 2370.88  4692.9  2369.6  4706.4 2368.38    4739 2366.46
  4750.7  2364.4  4773.2 2362.13  4804.3 2360.74  4820.8 2359.39  4863.6  2357.2
  4884.7 2355.56  4926.9 2353.51  4961.7 2352.98  4968.4 2352.76 4982.23 2350.87
  4986.8 2350.17  4993.6 2348.16  5006.4 2348.16 5009.32 2350.24 5010.93 2350.93
  5012.2 2351.68  5019.8 2353.69  5209.1 2356.71  5236.9 2357.76  5264.5 2358.03
#Mann= 6 ,-1 , 0
    4553     .09       0  4605.2     .03       0  4644.2     .05       0
  4961.7     .09       0 4982.23    .052       0 5010.93     .09       0
Bank Sta=4982.23,5010.93
Exp/Cntr=0.3,0.1

Type RM Length L Ch R = 1 ,21066   ,0,0,0
BEGIN DESCRIPTION:
tie to dtl
END DESCRIPTION:
XS GIS Cut Line= 6
       956667.95       787939.68        956548.7       787964.24
       956501.18       788001.73       956429.21       788093.19
       956423.44       788106.11       956307.87       788268.04
#Sta/Elev= 30
       0 2383.99   15.55 2382.08   44.75 2379.72   51.25 2379.05   58.89 2378.57
   112.6 2373.74  119.19  2372.7  124.99 2371.02  137.06 2367.87  142.33 2364.85
  149.13 2360.42  171.47 2359.61 182.269 2358.98  234.06  2358.8 264.131 2357.43
  290.77 2346.64 298.863 2343.36 304.293 2343.84 308.084 2345.36 313.258 2345.93
 320.072 2346.49 326.475 2348.74   344.2 2347.56 388.768 2348.21  388.82 2348.41
  394.22 2348.56  411.56 2348.65  437.79 2349.33  462.52 2350.06  512.35 2352.09
#Mann= 8 ,-1 , 0
       0     .05       0  124.99     .09       0  142.33     .03       0
  171.47     .05       0 264.131     .09       0  290.77     .05       0
 313.258     .09       0   344.2     .05       0
Bank Sta=290.77,313.258
Exp/Cntr=0.3,0.1
Stream Node=California Creek,Reach-1         , 0 , 0 ,Upstream end
Stream Node=California Creek,Reach-1         , 0 , 1 ,Downstream end

Chan Stop Cuts=-1
Use User Specified Reach Order=0
User Specified Reach Order=California Creek,Reach-1