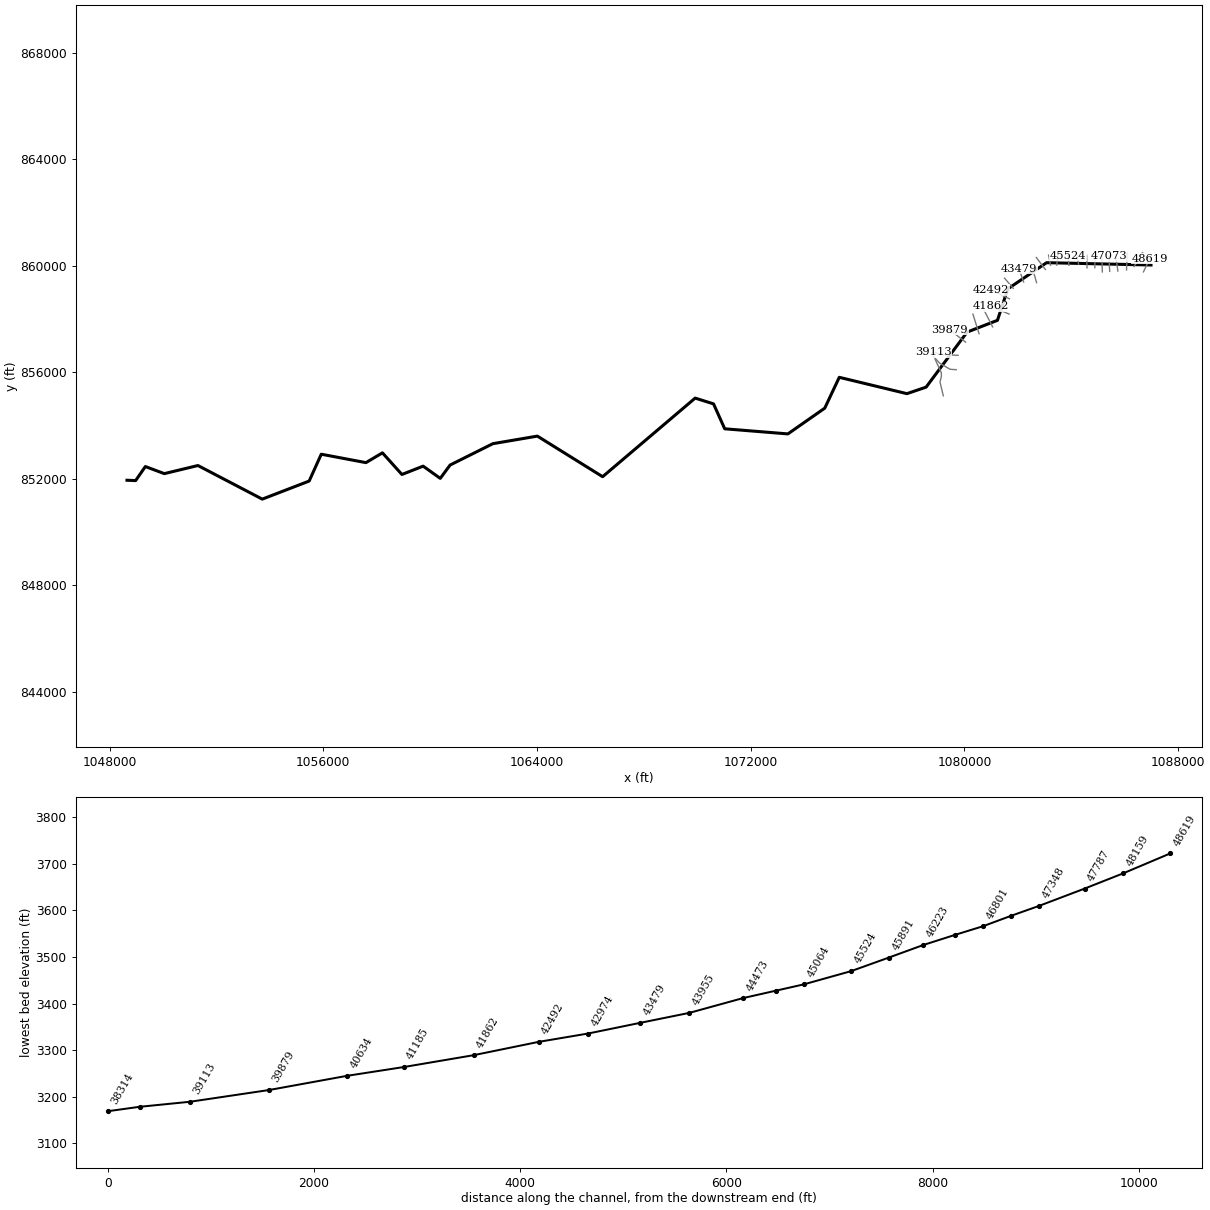
--- lds_little_rock_crk.prj (project) ---

Proj Title=Little Rock Creek Limited Detail Study
Current Plan=p02
Default Exp/Contr=0.3,0.1
English Units
Geom File=g01
Flow File=f02
Plan File=p02
Y Axis Title=Elevation
X Axis Title(PF)=Main Channel Distance
X Axis Title(XS)=Station
BEGIN DESCRIPTION:
1610
2440
2730
3550
4620
5060
5300
5670
5830
6010
6310
6530
6720
6910
7030
7220
7420
Little Rock Creek
END DESCRIPTION:
DSS Export Rating Curves= 0
DSS Export Rating Curve Sorted= 0
DSS Export Volume Flow Curves= 0
DXF OffsetX= 0
DXF OffsetY= 0
DXF ScaleX= 1
DXF ScaleY= 10

--- lds_little_rock_crk.p02 (plan) ---

Plan Title=Floodway Run
Program Version=3.13
Short Identifier=Floodway
Geom File=g01
Flow File=f02
Subcritical Flow
K Sum by GR= 0
Std Step Tol= 0.01
Critical Tol= 0.01
Num of Std Step Trials= 20
Max Error Tol= 0.3
Flow Tol Ratio= 0.001
Split Flow NTrial= 30
Split Flow Tol= 0.02
Split Flow Ratio= 0.02
Log Output Level= 0
Friction Slope Method= 0
Unsteady Friction Slope Method= 2
Unsteady Bridges Friction Slope Method= 1
Parabolic Critical Depth
Global Vel Dist= 0 , 0 , 0
Global Log Level= 0
CheckData=True
Encroach Param= 0 ,10,10, 2
Encroach River=Little Rock Cree
Encroach Reach=Reach-1
Encroach Node=48619
       4      .7
Encroach Node=48159
       1 4981.98 5016.44
Encroach Node=47787
       1 4948.94 5015.87
Encroach Node=47348
       1 4986.39  5033.8
Encroach Node=47073
       4      .7
Encroach Node=46801
       1 4978.97 5017.26
Encroach Node=46530
       1  4984.5  5019.9
Encroach Node=46223
       4      .7
Encroach Node=45891
       4      .7
Encroach Node=45524
       4      .7
Encroach Node=45064
       1  4983.9 5015.47
Encroach Node=44791
       1 4970.07 5012.71
Encroach Node=44473
       1 4974.18 5020.28
Encroach Node=43955
       1  4973.4 5020.32
Encroach Node=43479
       1  4989.1 5034.48
Encroach Node=42974
       1 4968.08  5017.6
Encroach Node=42492
       1    4925  5023.3
Encroach Node=41862
       1  4972.6  5008.6
Encroach Node=41185
       4      .7
Encroach Node=40634
       1  4987.7 5020.07
Encroach Node=39879
       1    4980    5042
Encroach Node=39113
       1 4985.21 5013.83
Encroach Node=38623
       1  4937.7    5170
Encroach Node=38314
       1    4840    5055
Encroach Node=38219
       1    4890    5040
Encroach Node=37969
       4      .7
Encroach Node=37260
       4      .7
Encroach Node=37160
       4      .7
Encroach Node=36400
       4      .7
Encroach Node=35741
       4      .7
Encroach Node=34805
       1    4977    5111
Encroach Node=33905
       4      .7
Encroach Node=33497
       1    4966    5058
Encroach Node=33300
       1  4820.8    5173
Encroach Node=33236
       1 4961.85 5110.35
Encroach Node=32978
       1    4965    5038
Encroach Node=32671
       4      .7
Encroach Node=32039
       1    4794  5110.2
Encroach Node=31814
       1  4927.5  5072.4
Encroach Node=31754
       1    4958 5042.01
Encroach Node=31340
       1    4870  5023.9
Encroach Node=30773
       4      .7
Encroach Node=30708
       4      .7
Encroach Node=30163
       1  4964.7  5041.2
Encroach Node=29681
       1    4977 5033.12
Encroach Node=29076
       1  4971.3  5022.2
Encroach Node=28698
       1  4979.3    5036
Encroach Node=28455
       1    4914    5023
Encroach Node=28375
       1    4956    5044
Encroach Node=27714
       1  4973.7 5020.42
Encroach Node=27363
       1 4965.54 5029.75
Encroach Node=26983
       1    4888    5100
Encroach Node=26919
       1    4890    5100
Encroach Node=26602
       4      .7
Encroach Node=26237
       4      .7
Encroach Node=25510
       4      .7
Encroach Node=24742
       1  4980.9 5036.41
Encroach Node=24339
       1  4963.5  5054.9
Encroach Node=23875
       1  3787.4    3884
Encroach Node=23643
       1  3778.1    3860
Encroach Node=23215
       1    4878  5027.9
Encroach Node=22633
       1  4973.4  5040.3
Encroach Node=21982
       1    4966    5038
Encroach Node=21214
       4      .7
Encroach Node=20526
       1  4975.4    5032
Encroach Node=20026
       1  4949.6    5054
Encroach Node=19683
       1  4952.5    5070
Encroach Node=19466
       1    4953    5129
Encroach Node=19405
       1  4947.4  5071.2
Encroach Node=19286
       1  4970.3    5043
Encroach Node=19037
       1    4865 5030.33
Encroach Node=18691
       1    4840  5068.5
Encroach Node=18620
       1    4840    5077
Encroach Node=18251
       1  4977.7    5133
Encroach Node=17851
       1    4935  5032.9
Encroach Node=17578
       1    4905    5044
Encroach Node=17456
       1    4950  5070.3
Encroach Node=17184
       1    4959  5049.3
Encroach Node=16853
       1    4946    5039
Encroach Node=16598
       1    4910    5030
Encroach Node=16480
       1    4957    5035
Encroach Node=16280
       1    4973  5026.4
Encroach Node=16021
       4      .7
Encroach Node=15562
       1  4966.9    5052
Encroach Node=15013
       1    4897  5026.7
Encroach Node=14469
       1    4972    5080
Encroach Node=13963
       4      .7
Encroach Node=13589
       1    4906  5021.5
Encroach Node=13329
       1    4838  5034.4
Encroach Node=13253
       1    4884    5040
Encroach Node=13011
       1    4944    5100
Encroach Node=12822
       1  4966.1    5290
Encroach Node=12675
       1    4945    5320
Encroach Node=12617
       1  4941.1    5300
Encroach Node=12466
       1    4944    5238
Encroach Node=12250
       1  4962.5 5181.03
Encroach Node=12005
       1    4920  5115.9
Encroach Node=11954
       1    4888 5105.15
Encroach Node=11809
       1    4883    5026
Encroach Node=11578
       1    4940    5024
Encroach Node=11072
       4      .7
Encroach Node=10590
       1    4970    5024
Encroach Node=10147
       1    4971    5042
Encroach Node=9715
       1    4950    5060
Encroach Node=9419
       1    4979    5020
Encroach Node=9048
       1  4971.2    5041
Encroach Node=8744
       1  4945.3 5033.87
Encroach Node=8306
       1    4979    5042
Encroach Node=7971
       1  4976.7    5065
Encroach Node=7697
       1  4950.6    5040
Encroach Node=7266
       1    4950 5037.06
Encroach Node=6876
       1 4975.66    5042
Encroach Node=6480
       1    4964    5027
Encroach Node=6203
       1  4968.8 5041.37
Encroach Node=5836
       1 4976.16  5060.5
Encroach Node=5407
       1    4972    5020
Encroach Node=5324
       1    4977    5026
Encroach Node=4950
       1  4974.5  5057.7
Encroach Node=4405
       1  4976.9    5037
Encroach Node=4108
       1    4975    5035
Encroach Node=4035
       1    4969    5018
Encroach Node=3946
       1    4942    5020
Encroach Node=3604
       1    4977    5070
Encroach Node=3186
       1    4895    5021
Encroach Node=2644
       1    4972    5035
Encroach Node=2243
       1    4960    5045
Encroach Node=1945
       1    4960    5040
Encroach Node=1590
       4      .7
Encroach Node=1023
       1    4971  5031.3
Encroach Node=590
       1  4968.7    5038
Encroach Node=70
       4      .7
BEGIN DESCRIPTION:
Floodway Run
END DESCRIPTION:
Computation Interval=1HOUR
Output Interval=1HOUR
Run HTab= 0
Run UNet= 0
Run PostProcess= 0
UNET Theta= 1
UNET Theta Warmup= 1
UNET ZTol= 0.02
UNET ZSATol= 0.05
UNET MxIter= 20
UNET MaxInSteps= 0
UNET DtIC= 0
UNET DtMin= 0
UNET MaxCRTS= 20
UNET WFStab= 2
UNET SFStab= 1
UNET WFX= 1
UNET SFX= 1
UNET DSS MLevel= 4
UNET DZMax Abort= 100
UNET Convert EG Bridges=-1
UNET Use Existing IB Tables=-1
UNET Froude Reduction=False
UNET Froude Limit= 1
UNET Froude Power= 10
Instantaneous Interval=1HOUR
Write IC File= 0
Echo Input=False
Echo Output=False
Write Detailed= 0
Detailed Automatic Start=False, 10

--- lds_little_rock_crk.f02 (steady flow) ---

Flow Title=Floodway
Program Version=3.13
Number of Profiles= 2
Profile Names=100-year,100-FW
River Rch & RM=Little Rock Cree,Reach-1         ,48619
    1610    1610
River Rch & RM=Little Rock Cree,Reach-1         ,45524
    2440    2440
River Rch & RM=Little Rock Cree,Reach-1         ,44473
    2730    2730
River Rch & RM=Little Rock Cree,Reach-1         ,39879
    3550    3550
River Rch & RM=Little Rock Cree,Reach-1         ,36400
    4620    4620
River Rch & RM=Little Rock Cree,Reach-1         ,34805
    5060    5060
River Rch & RM=Little Rock Cree,Reach-1         ,33497
    5300    5300
River Rch & RM=Little Rock Cree,Reach-1         ,30163
    5670    5670
River Rch & RM=Little Rock Cree,Reach-1         ,27714
    5830    5830
River Rch & RM=Little Rock Cree,Reach-1         ,24742
    6010    6010
River Rch & RM=Little Rock Cree,Reach-1         ,21982
    6310    6310
River Rch & RM=Little Rock Cree,Reach-1         ,20526
    6530    6530
River Rch & RM=Little Rock Cree,Reach-1         ,17184
    6720    6720
River Rch & RM=Little Rock Cree,Reach-1         ,13329
    6910    6910
River Rch & RM=Little Rock Cree,Reach-1         ,11578
    7030    7030
River Rch & RM=Little Rock Cree,Reach-1         ,9419
    7220    7220
River Rch & RM=Little Rock Cree,Reach-1         ,5836
    7420    7420
Boundary for River Rch & Prof#=Little Rock Cree,Reach-1         , 1
Up Type= 0
Dn Type= 3
Dn Slope=0.015
Boundary for River Rch & Prof#=Little Rock Cree,Reach-1         , 2
Up Type= 0
Dn Type= 3
Dn Slope=0.015
DSS Import GetInterval= 0
DSS Import GetPeak= 0
DSS Import FillOption= 0

--- lds_little_rock_crk.g01 (geometry) ---

Geom Title=Existing Conditions
Program Version=3.13

River Reach=Little Rock Cree,Reach-1
Reach XY= 30
      1086986.21       860025.29      1083077.35       860112.65
      1081623.68       859127.72      1081237.52        857947.2
      1080102.21       857505.36      1078567.09       855437.32
      1077847.65       855191.92      1075315.82       855806.02
      1074772.34       854647.24      1073392.11         853680.
      1071026.72       853871.72      1070608.88       854807.66
      1069921.26       855025.05      1066455.89       852072.45
      1064013.32       853596.99      1062348.18       853313.04
      1060746.44       852510.79      1060377.03       852009.04
      1059736.68       852468.52      1058942.08       852155.79
      1058212.39       852968.09      1057594.81       852600.29
      1055923.01       852916.95      1055468.67       851907.97
      1053714.27       851229.42      1051304.91       852492.12
      1050046.14       852187.26      1049336.93       852453.99
      1048972.89       851926.06      1048649.38       851938.84

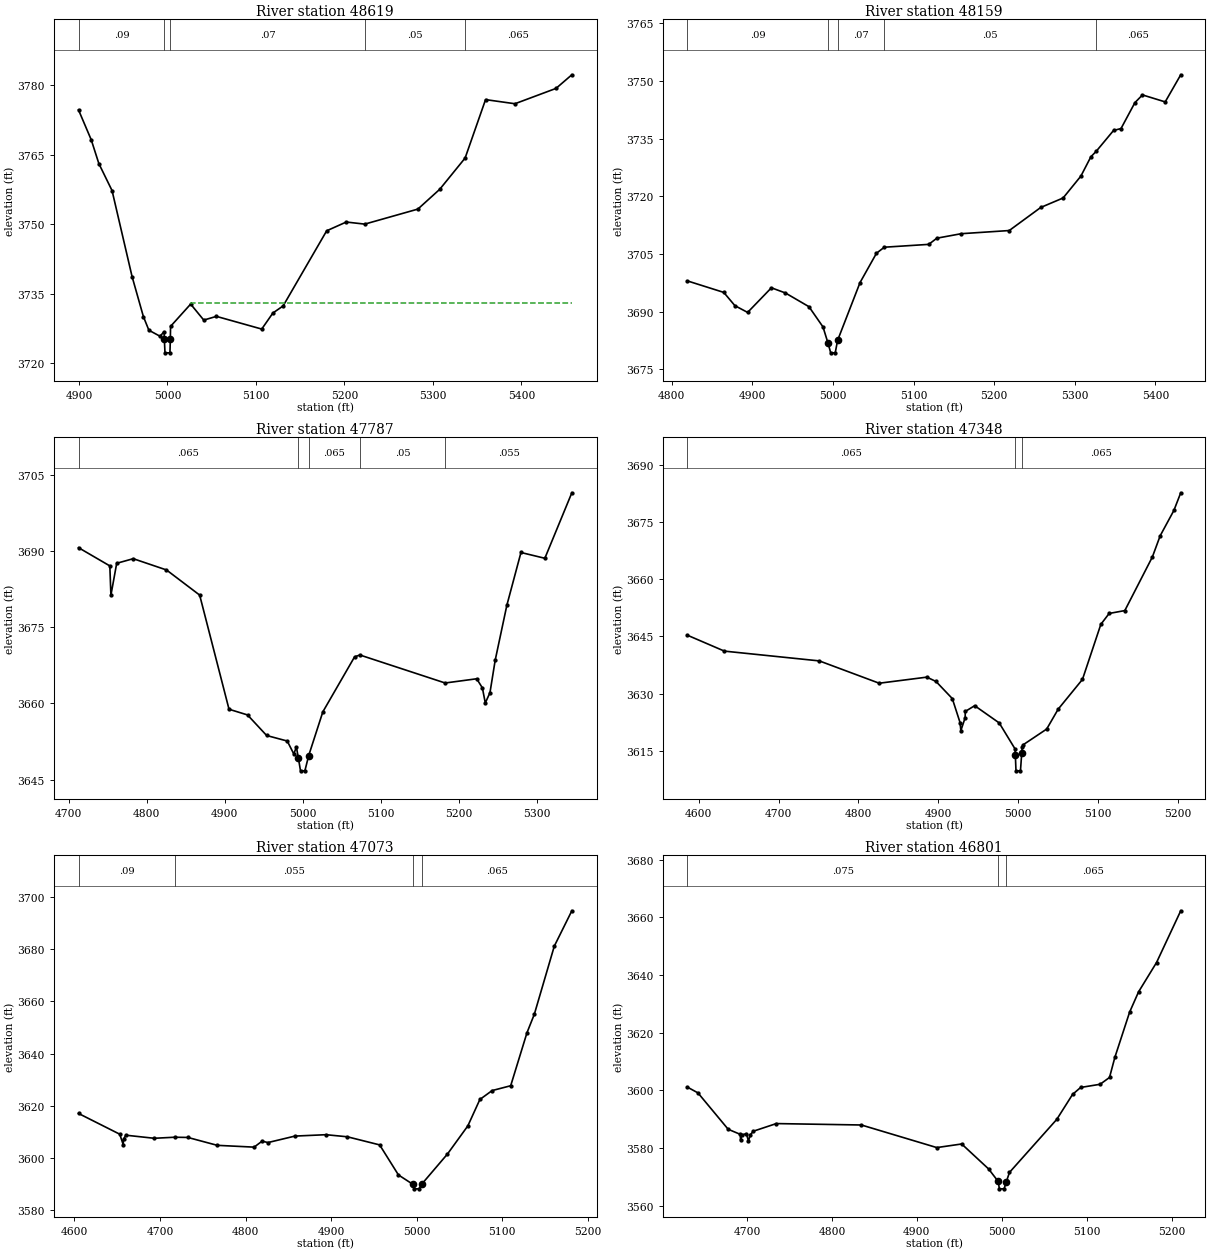
Type RM Length L Ch R = 1 ,48619   ,460,460,460
BEGIN DESCRIPTION:
Little_Rock_Crk_129
END DESCRIPTION:
XS GIS Cut Line= 2
      1086703.33       859766.24      1086942.86        860269.5
#Sta/Elev= 30
  4899.5 3774.73  4913.9 3768.26  4922.5 3763.13  4937.4 3757.31    4960 3738.76
  4972.8 3730.12    4979 3727.18  4991.6 3725.88  4996.2 3726.87 4996.47 3725.25
  4997.2  3722.3  5002.8  3722.3 5003.23 3725.19  5003.5 3728.01  5026.2 3732.82
    5041 3729.37  5055.3 3730.17  5106.5 3727.43  5119.1 3730.89  5130.7 3732.43
  5179.9 3748.64    5202 3750.53  5222.9 3750.08  5282.9 3753.32  5307.6 3757.59
  5336.3 3764.34  5359.4 3776.95  5392.6 3776.06    5439 3779.37  5456.9 3782.31
#Mann= 5 ,-1 , 0
  4899.5     .09       0 4996.47     .05       0 5003.23     .07       0
  5222.9     .05       0  5336.3    .065       0
#XS Ineff= 2 , 0
       0                  5026.2       0    3733
Permanent Ineff=
       F       F
Bank Sta=4996.47,5003.23
Exp/Cntr=0.3,0.1

Type RM Length L Ch R = 1 ,48159   ,372,372,372
BEGIN DESCRIPTION:
Little_Rock_Crk_128
END DESCRIPTION:
XS GIS Cut Line= 2
       1086352.5       859967.06      1086667.04        860492.1
#Sta/Elev= 30
  4819.4 3697.99  4864.5    3695  4878.3 3691.55  4894.1 3689.79  4923.6  3696.2
    4941 3694.85  4970.2 3691.28  4987.6 3686.02 4993.93 3681.74  4997.2 3679.27
  5002.8 3679.27  5005.7 3682.49  5033.6 3697.57    5054  3705.2  5063.7 3706.76
  5118.8  3707.5  5128.9 3709.11  5159.2 3710.28  5218.7  3711.1  5257.8 3717.11
  5285.5 3719.57  5307.6 3725.27    5320  3730.3  5326.6 3731.72  5348.1 3737.14
  5357.4 3737.65  5374.6 3744.38    5384  3746.4  5412.2 3744.58  5431.5 3751.64
#Mann= 5 ,-1 , 0
  4819.4     .09       0 4993.93     .05       0  5005.7     .07       0
  5063.7     .05       0  5326.6    .065       0
Bank Sta=4993.93,5005.7
Exp/Cntr=0.3,0.1

Type RM Length L Ch R = 1 ,47787   ,439,439,439
BEGIN DESCRIPTION:
Little_Rock_Crk_127
END DESCRIPTION:
XS GIS Cut Line= 2
      1086069.42       859841.25      1086096.03       860472.74
#Sta/Elev= 30
  4712.8 3690.67  4752.9 3687.08  4754.3 3681.31  4761.7 3687.59  4782.9  3688.5
  4825.5 3686.28    4868 3681.33  4905.6 3658.85  4929.3 3657.73  4953.8 3653.68
  4980.2 3652.59  4988.6 3650.04  4991.9 3651.42 4994.41 3649.28  4997.2 3646.72
  5002.8 3646.72 5007.64 3649.71  5025.8 3658.34  5066.5 3669.18  5073.3 3669.53
  5182.5 3664.02  5222.9 3664.85  5230.2 3663.05  5233.9 3660.09  5239.9 3662.11
  5246.6 3668.51  5261.6 3679.37  5279.6 3689.72  5310.2 3688.58  5344.8 3701.48
#Mann= 5 ,-1 , 0
  4712.8    .065       0 4994.41     .05       0 5007.64    .065       0
  5073.3     .05       0  5182.5    .055       0
Bank Sta=4994.41,5007.64
Exp/Cntr=0.3,0.1

Type RM Length L Ch R = 1 ,47348   ,275,275,275
BEGIN DESCRIPTION:
Little_Rock_Crk_126
END DESCRIPTION:
XS GIS Cut Line= 2
       1085745.2        859797.7      1085665.36       860409.84
#Sta/Elev= 30
    4586 3645.32  4632.3 3641.16  4751.1  3638.6    4826 3632.76  4885.6 3634.35
  4897.1 3633.22  4917.5 3628.74  4927.2 3622.46  4928.2 3620.35  4933.6 3623.75
  4933.7 3625.37  4945.5 3626.88  4976.2 3622.37    4996 3615.57 4996.39 3614.02
  4997.2 3609.83  5002.8 3609.83 5004.38 3614.44    5005 3615.95  5006.4 3616.68
  5035.6 3620.76    5050 3625.97  5080.4 3633.76  5103.4 3648.17  5113.8 3651.02
  5133.4 3651.77  5167.9 3665.81  5177.7 3671.37  5194.8 3677.97  5203.4  3682.6
#Mann= 3 , 0 , 0
    4586    .065       0 4996.39     .05       0 5004.38    .065       0
Bank Sta=4996.39,5004.38
Exp/Cntr=0.3,0.1

Type RM Length L Ch R = 1 ,47073   ,272,272,272
BEGIN DESCRIPTION:
Little_Rock_Crk_125
END DESCRIPTION:
XS GIS Cut Line= 2
      1085440.34        859785.6      1085408.89       860361.45
#Sta/Elev= 30
  4604.8 3617.09    4653 3609.15    4657  3605.2  4657.4 3607.22  4660.1 3608.77
  4693.3 3607.59  4717.1 3607.99  4732.6 3607.91    4767 3604.89  4810.1  3604.2
  4819.4  3606.5  4826.2 3605.95  4857.8 3608.43  4894.1 3608.96  4919.1 3608.16
  4956.8 3605.06  4978.8 3593.55 4995.46 3590.02  4997.2 3588.24  5002.8 3588.24
 5006.38 3590.17  5036.1 3601.57  5059.9 3612.33    5074 3622.45  5088.3 3625.85
    5110  3627.7  5129.1 3648.04  5137.6 3655.02    5161 3681.14  5181.5 3694.66
#Mann= 4 ,-1 , 0
  4604.8     .09       0  4717.1    .055       0 4995.46     .05       0
 5006.38    .065       0
Bank Sta=4995.46,5006.38
Exp/Cntr=0.3,0.1

Type RM Length L Ch R = 1 ,46801   ,271,271,271
BEGIN DESCRIPTION:
Little_Rock_Crk_124
END DESCRIPTION:
XS GIS Cut Line= 2
      1085164.52       859763.82      1085145.16       860344.51
#Sta/Elev= 30
  4629.8 3601.15  4642.2 3599.16  4677.8 3586.55    4692 3584.79  4692.4 3582.75
  4693.7 3584.53  4699.2 3585.04  4701.7 3582.47  4703.7 3584.54  4707.3 3585.86
  4734.5 3588.52  4834.7 3588.03  4923.5  3580.2  4952.8 3581.45  4984.5  3572.8
 4995.83 3568.45  4997.2  3565.9  5002.8  3565.9 5005.24 3568.25  5009.1  3571.6
  5064.8 3589.98  5083.4 3598.63  5092.9 3601.04  5115.8 3602.14  5126.9  3604.5
  5133.2 3611.48  5150.6 3627.16  5161.1 3634.17  5182.3 3644.35  5210.8 3662.28
#Mann= 3 , 0 , 0
  4629.8    .075       0 4995.83     .05       0 5005.24    .065       0
Bank Sta=4995.83,5005.24
Exp/Cntr=0.3,0.1

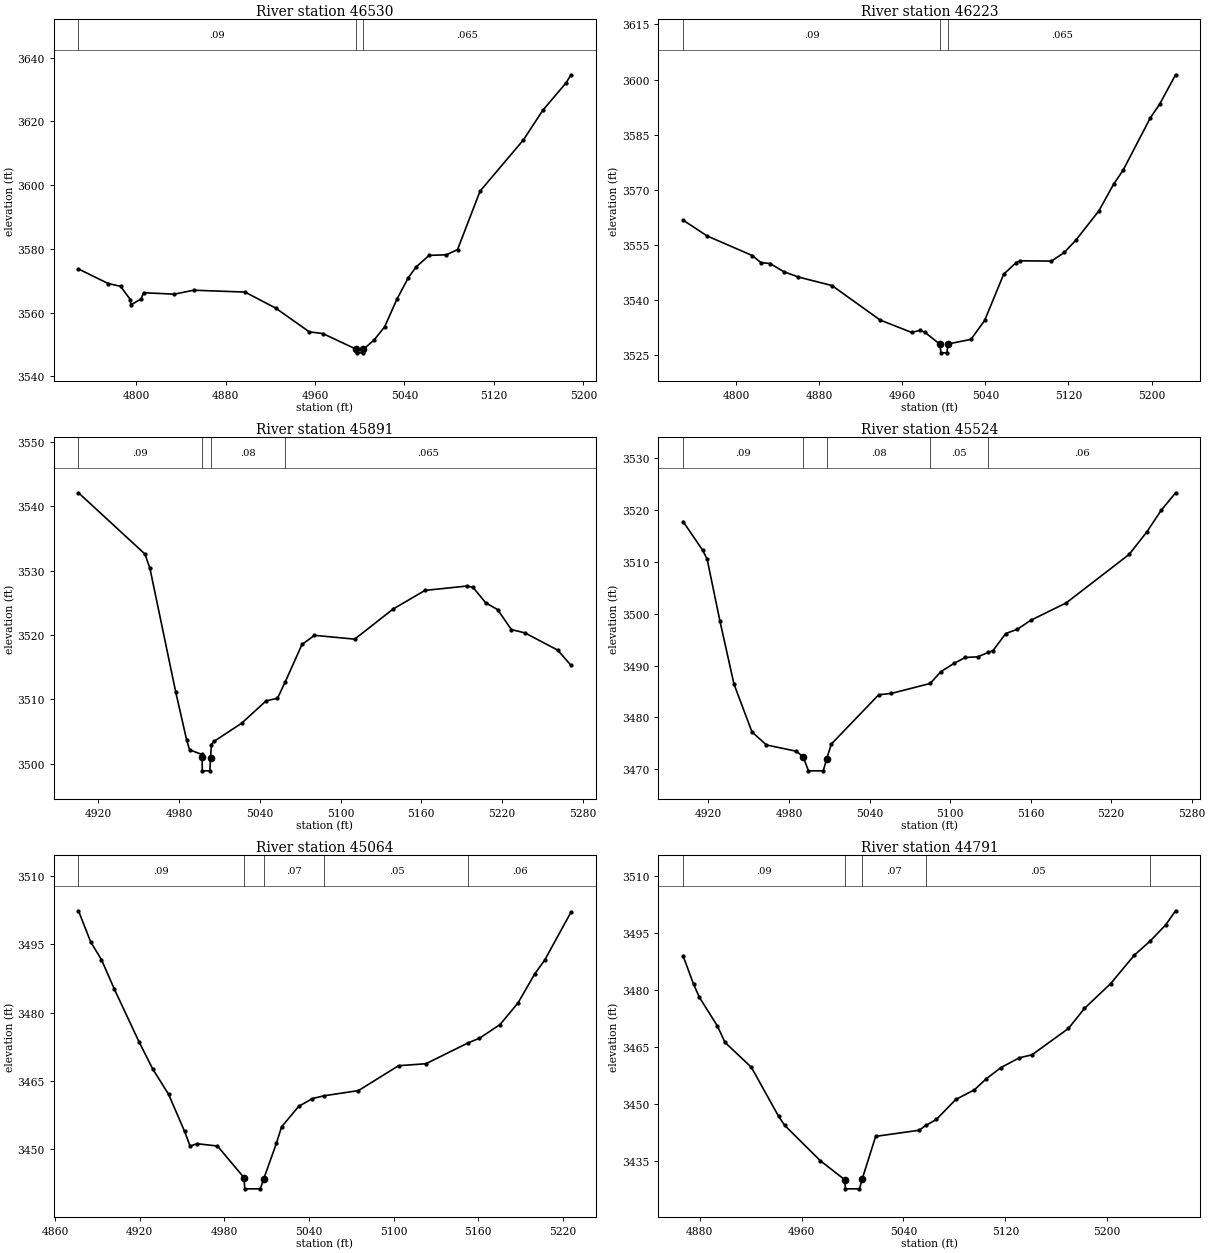
Type RM Length L Ch R = 1 ,46530   ,307,307,307
BEGIN DESCRIPTION:
Little_Rock_Crk_123
END DESCRIPTION:
XS GIS Cut Line= 2
      1084883.85       859923.51      1084886.27       860363.87
#Sta/Elev= 30
  4748.5 3573.71    4775 3569.14  4786.1 3568.27    4795 3564.04  4795.2 3562.39
  4804.5 3564.32  4806.7 3566.25  4834.2  3565.8  4851.4 3567.04  4897.4 3566.46
  4924.7 3561.46  4954.9 3553.99    4967 3553.45  4996.3 3548.63  4997.2  3547.4
  5002.8  3547.4  5003.3 3548.52    5013 3551.49  5022.3 3555.56  5033.2 3564.17
  5043.5 3570.99  5050.5 3574.36  5062.1 3577.97  5077.6 3578.15  5087.5  3579.8
  5107.6 3598.11  5146.4 3614.18  5163.7 3623.45  5184.6 3632.09  5188.9  3634.6
#Mann= 3 , 0 , 0
  4748.5     .09       0  4996.3     .05       0  5003.3    .065       0
Bank Sta=4996.3,5003.3
Exp/Cntr=0.3,0.1

Type RM Length L Ch R = 1 ,46223   ,332,332,332
BEGIN DESCRIPTION:
Little_Rock_Crk_122
END DESCRIPTION:
XS GIS Cut Line= 2
      1084591.09       859918.67      1084576.57        860392.9
#Sta/Elev= 30
  4748.8 3561.78    4772 3557.47  4815.6 3552.14  4823.6 3550.25  4832.6 3549.98
  4845.7 3547.78  4859.8 3546.32  4892.2    3544  4938.6 3534.62    4969 3531.24
    4977 3531.82  4981.6 3531.31  4996.1 3528.05  4997.2  3525.7  5002.8  3525.7
  5004.2 3528.12  5026.1 3529.36  5039.3 3534.53  5057.6 3547.07  5069.5 3550.21
  5073.3 3550.73  5103.6 3550.64    5116 3552.99  5127.1 3556.34  5149.3 3564.29
  5163.5 3571.56  5172.6 3575.34  5198.8 3589.56  5207.8 3593.31  5223.2 3601.31
#Mann= 3 , 0 , 0
  4748.8     .09       0  4996.1     .05       0  5004.2    .065       0
Bank Sta=4996.1,5004.2
Exp/Cntr=0.3,0.1

Type RM Length L Ch R = 1 ,45891   ,367,367,367
BEGIN DESCRIPTION:
Little_Rock_Crk_121
END DESCRIPTION:
XS GIS Cut Line= 2
      1084274.13       860056.59      1084211.23       860417.09
#Sta/Elev= 30
  4905.2  3542.1  4954.6 3532.58  4958.3 3530.35  4977.4 3511.21  4985.6 3503.68
  4987.8 3502.16    4997 3501.44  4997.1 3501.12  4997.2  3498.9  5002.8  3498.9
 5003.35 3500.97    5004 3502.99  5005.8 3503.46  5026.4 3506.29  5044.7 3509.78
  5053.1 3510.17  5058.9 3512.74  5071.3 3518.53  5080.6 3519.95  5110.5 3519.36
  5138.9 3524.02  5162.7 3526.93  5193.8 3527.61  5198.4 3527.41  5207.9 3524.99
  5216.7 3523.95  5226.9 3520.85    5237 3520.33  5261.3 3517.66  5271.2  3515.3
#Mann= 4 ,-1 , 0
  4905.2     .09       0  4997.1     .05       0 5003.35     .08       0
  5058.9    .065       0
Bank Sta=4997.1,5003.35
Exp/Cntr=0.3,0.1

Type RM Length L Ch R = 1 ,45524   ,460,460,460
BEGIN DESCRIPTION:
Little_Rock_Crk_120
END DESCRIPTION:
XS GIS Cut Line= 2
      1083913.63       860015.45      1083879.75        860380.8
#Sta/Elev= 30
  4901.1  3517.8  4915.7 3512.25    4919 3510.54  4928.5 3498.65    4939 3486.44
  4952.4  3477.2  4963.2 3474.69  4985.5 3473.48  4990.6 3472.38  4994.5  3469.7
  5005.5  3469.7    5008 3471.95  5011.5 3474.86  5046.8 3484.37  5056.3 3484.64
  5085.2 3486.56  5093.2 3488.86  5103.1 3490.45  5111.3 3491.58  5120.6 3491.69
  5128.3 3492.54  5131.9 3492.87  5141.4 3496.18  5150.2 3497.03  5160.2 3498.76
  5186.5  3502.1  5233.4 3511.46  5246.5 3515.77  5257.3 3519.98    5268 3523.35
#Mann= 5 ,-1 , 0
  4901.1     .09       0  4990.6     .05       0    5008     .08       0
  5085.2     .05       0  5128.3     .06       0
Bank Sta=4990.6,5008
Exp/Cntr=0.3,0.1

Type RM Length L Ch R = 1 ,45064   ,273,273,273
BEGIN DESCRIPTION:
Little_Rock_Crk_119
END DESCRIPTION:
XS GIS Cut Line= 2
      1083453.92       860020.29      1083502.31       860366.28
#Sta/Elev= 30
  4876.5 3502.39  4885.2 3495.51  4892.8 3491.64    4902 3485.12  4919.4 3473.59
  4929.1 3467.63  4940.4 3462.03  4951.8 3453.84  4955.7 3450.62  4960.5 3451.15
  4975.1 3450.64  4993.9 3443.69  4994.5 3441.22  5005.5 3441.22 5007.91  3443.4
  5016.9 3451.22  5020.6 3454.87  5032.8 3459.38  5042.5 3461.08  5050.9  3461.7
  5075.1 3462.83  5103.6 3468.31    5123 3468.74  5153.2 3473.37    5161 3474.35
  5175.6 3477.37  5188.3  3482.1  5200.2  3488.5  5207.3 3491.56  5225.9 3502.07
#Mann= 5 ,-1 , 0
  4876.5     .09       0  4993.9     .05       0 5007.91     .07       0
  5050.9     .05       0  5153.2     .06       0
Bank Sta=4993.9,5007.91
Exp/Cntr=0.3,0.1

Type RM Length L Ch R = 1 ,44791   ,318,318,318
BEGIN DESCRIPTION:
Little_Rock_Crk_118
END DESCRIPTION:
XS GIS Cut Line= 2
      1083224.06       860017.87      1083151.48       860397.74
#Sta/Elev= 30
    4867    3489  4875.3 3481.46  4879.8 3478.07  4893.9 3470.53  4899.9 3466.18
  4920.6 3459.62    4942 3446.67  4946.7 3444.32  4974.7 3434.99  4993.8 3429.99
  4994.5 3427.56  5005.5 3427.56  5007.6 3430.13  5018.2  3441.4  5052.3 3443.01
  5057.7  3444.3  5065.9 3445.87  5081.1 3451.13  5095.8 3453.69  5104.8 3456.52
  5116.6 3459.55    5131 3462.12    5141 3462.92  5169.6 3469.87  5182.1 3475.13
  5202.7 3481.69  5221.3 3489.19  5233.7 3492.91  5245.8 3497.13  5253.7  3500.9
#Mann= 5 ,-1 , 0
    4867     .09       0  4993.8     .05       0  5007.6     .07       0
  5057.7     .05       0  5233.7     .06       0
Bank Sta=4993.8,5007.6
Exp/Cntr=0.3,0.1

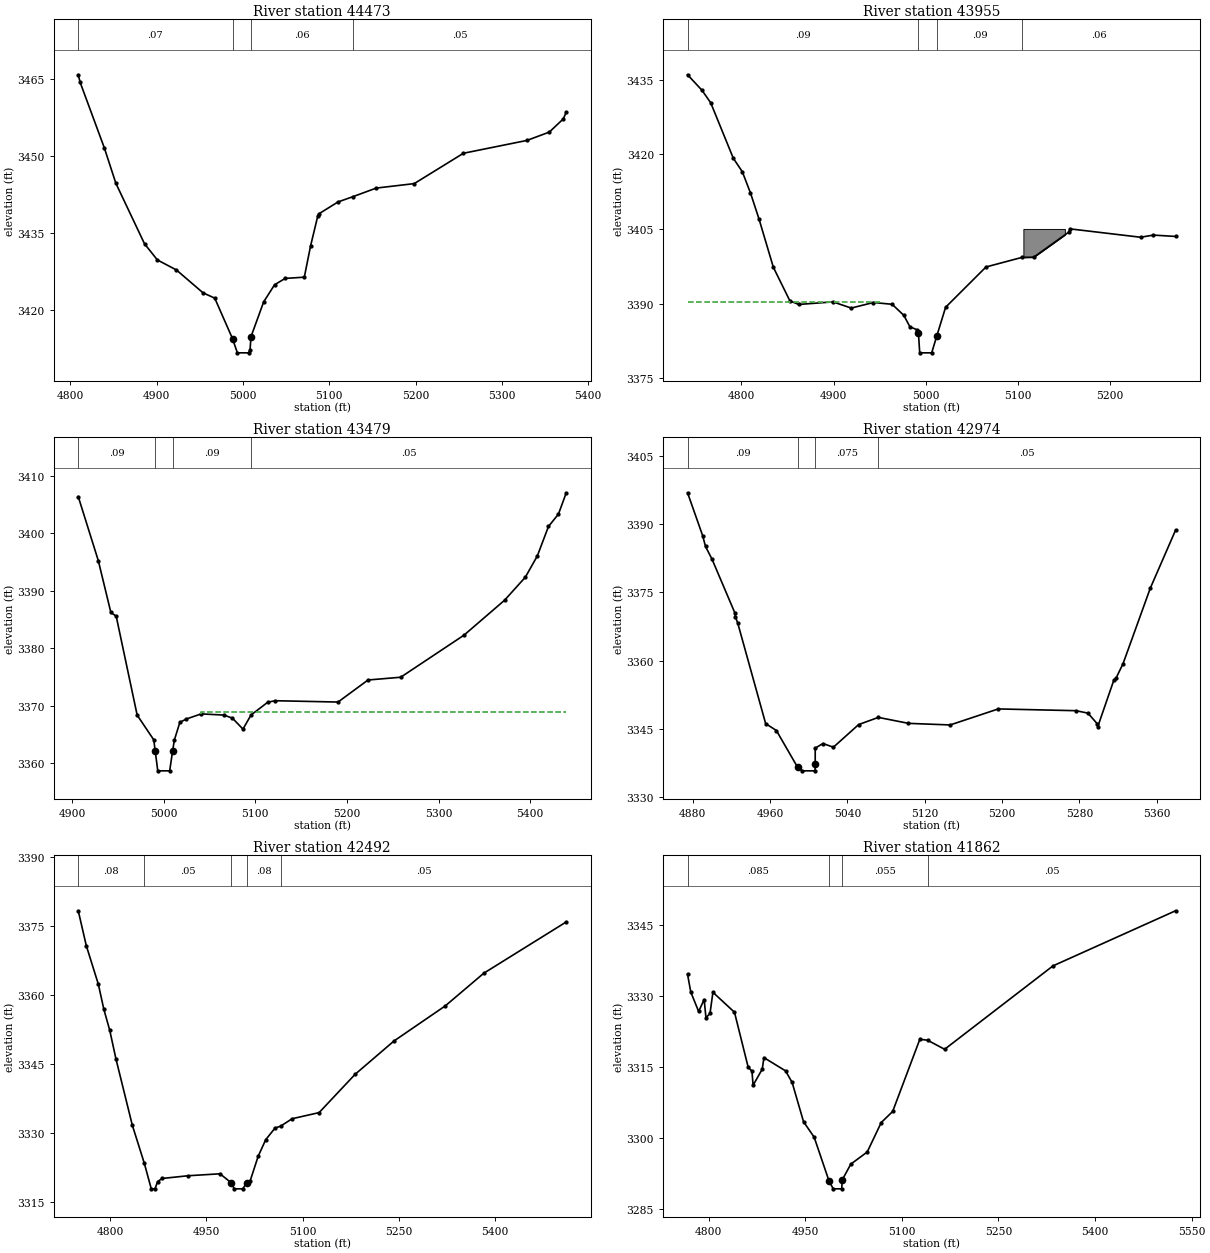
Type RM Length L Ch R = 1 ,44473   ,518,518,518
BEGIN DESCRIPTION:
Little_Rock_Crk_117
END DESCRIPTION:
XS GIS Cut Line= 2
      1083032.28       859857.09      1082691.57       860308.48
#Sta/Elev= 30
  4809.1 3465.73  4811.2  3464.3  4839.3 3451.53  4852.7 3444.63  4885.9 3432.87
  4900.8 3429.73  4922.9 3427.78  4953.7 3423.34  4967.3  3422.3 4987.94 3414.41
  4993.5 3411.67  5006.5 3411.67  5008.2 3412.22  5009.3  3414.8    5024 3421.58
  5036.6  3424.9  5048.9 3426.14  5071.1 3426.38  5078.4 3432.48  5086.7 3438.27
  5088.1 3438.71  5110.2 3441.01  5127.1 3442.01  5154.4  3443.7  5198.5 3444.57
  5255.5 3450.47  5329.2 3452.97  5355.1 3454.59  5371.3 3457.16  5374.7 3458.48
#Mann= 4 ,-1 , 0
  4809.1     .07       0 4987.94     .05       0  5009.3     .06       0
  5127.1     .05       0
Bank Sta=4987.94,5009.3
Exp/Cntr=0.3,0.1

Type RM Length L Ch R = 1 ,43955   ,476,476,476
BEGIN DESCRIPTION:
Little_Rock_Crk_116
END DESCRIPTION:
XS GIS Cut Line= 2
       1082703.5       859360.91      1082558.06       859869.97
#Sta/Elev= 30
  4741.6 3435.99  4757.3 3432.87  4766.7 3430.37  4791.3 3419.19    4801 3416.51
  4809.9 3412.22  4819.1 3407.02  4834.7 3397.29  4852.7 3390.52  4862.3 3389.82
  4899.5 3390.33  4919.2 3389.09  4943.3 3390.21  4963.6 3389.85  4976.3 3387.62
  4982.8 3385.35  4990.7 3384.71  4992.1 3384.17  4993.5 3380.09  5006.5 3380.09
    5012 3383.46  5021.6 3389.25  5065.4 3397.35  5104.5 3399.28  5117.2 3399.32
  5155.1 3404.34  5156.7 3405.01  5233.1 3403.33  5247.1 3403.76  5271.1 3403.49
#Mann= 4 ,-1 , 0
  4741.6     .09       0  4992.1     .05       0    5012     .09       0
  5104.5     .06       0
#XS Ineff= 2 , 0
       0  4952.3 3390.27               0
Permanent Ineff=
       F       F
#Block Obstruct= 1 ,-1
    5106    5151    3405
Bank Sta=4992.1,5012
Exp/Cntr=0.3,0.1

Type RM Length L Ch R = 1 ,43479   ,505,505,505
BEGIN DESCRIPTION:
Little_Rock_Crk_115
END DESCRIPTION:
XS GIS Cut Line= 2
      1082218.48       859388.34      1082038.36       859889.64
#Sta/Elev= 30
  4906.7 3406.35  4928.6 3395.22  4942.3 3386.23  4948.1 3385.59    4971  3368.4
  4989.1 3364.11 4990.76 3362.11  4993.5 3358.72  5006.5 3358.72 5009.64 3362.11
  5011.6 3364.06  5017.6 3367.14  5024.6 3367.72  5040.9 3368.61  5065.6 3368.41
    5075 3367.87  5086.5 3365.97  5095.3 3368.42  5113.6 3370.64  5121.7  3370.9
  5190.3 3370.67    5223  3374.5  5258.7 3374.98  5327.8 3382.29  5372.1 3388.36
  5394.7 3392.35  5407.8 3396.04    5420 3401.17  5430.9 3403.32  5439.4 3407.02
#Mann= 4 ,-1 , 0
  4906.7     .09       0 4990.76     .05       0 5009.64     .09       0
  5095.3     .05       0
#XS Ineff= 2 , 0
       0                    5041       0    3369
Permanent Ineff=
       F       F
Bank Sta=4990.76,5009.64
Exp/Cntr=0.3,0.1

Type RM Length L Ch R = 1 ,42974   ,482,482,482
BEGIN DESCRIPTION:
Little_Rock_Crk_114
END DESCRIPTION:
XS GIS Cut Line= 2
      1081830.03       859147.46      1081502.33       859531.57
#Sta/Elev= 30
  4874.6 3396.89  4890.2 3387.49  4893.2 3385.09  4899.9 3382.31  4923.5 3370.53
  4924.2 3369.58  4926.4 3368.36  4955.4 3346.19  4966.5 3344.67  4988.5 3336.58
  4993.5 3335.81  5006.5 3335.81 5006.67 3337.25  5006.7  3340.8  5014.7 3341.81
  5025.5    3341  5051.6 3345.97    5072 3347.55  5103.2 3346.24  5146.3 3345.89
  5196.1 3349.41  5276.6 3349.02  5288.9 3348.48  5298.7 3346.09    5299  3345.5
  5315.7 3355.76  5318.2 3356.29  5325.2 3359.36  5353.4 3375.95  5379.5 3388.67
#Mann= 4 ,-1 , 0
  4874.6     .09       0  4988.5     .05       0 5006.67    .075       0
    5072     .05       0
Bank Sta=4988.5,5006.67
Exp/Cntr=0.3,0.1

Type RM Length L Ch R = 1 ,42492   ,630,630,630
BEGIN DESCRIPTION:
Little_Rock_Crk_113
END DESCRIPTION:
XS GIS Cut Line= 2
       1081686.8       858754.66       1081003.2       859086.69
#Sta/Elev= 30
  4750.5 3378.38    4763 3370.79  4781.8 3362.37  4790.3 3356.94  4799.5 3352.36
  4809.3 3346.05  4834.7 3331.66  4853.4 3323.36  4864.2 3317.81    4870  3317.8
  4874.1 3319.38  4881.1 3320.06  4921.4 3320.65  4971.3 3321.08  4988.7 3319.11
  4993.5  3317.8  5006.5  3317.8  5013.3 3319.13  5018.2 3319.52  5030.7  3324.9
  5042.5 3328.52    5057 3331.05  5065.5 3331.44  5083.5 3333.07  5125.6 3334.41
  5181.8 3342.77  5242.2 3350.01  5322.1 3357.66    5382 3364.77  5510.5 3375.95
#Mann= 5 ,-1 , 0
  4750.5     .08       0  4853.4     .05       0  4988.7     .05       0
  5013.3     .08       0  5065.5     .05       0
Bank Sta=4988.7,5013.3
Exp/Cntr=0.3,0.1

Type RM Length L Ch R = 1 ,41862   ,677,677,677
BEGIN DESCRIPTION:
Little_Rock_Crk_112
END DESCRIPTION:
XS GIS Cut Line= 2
      1081673.78       858181.74      1080974.99       858474.71
#Sta/Elev= 30
  4767.2 3334.57  4772.2 3330.83  4784.4 3326.72    4793 3329.24  4795.8 3325.37
  4802.1 3326.33  4806.6 3330.77  4840.1 3326.55  4861.4 3314.91  4867.2 3314.13
    4869 3311.14  4883.2 3314.53  4885.8 3316.97  4919.4 3314.17  4929.6 3311.73
  4947.3 3303.43  4963.8 3300.17 4987.07 3290.84  4993.5 3289.25  5006.5 3289.25
 5007.66  3291.2  5020.7 3294.47  5046.2 3297.03    5068 3303.26  5085.7 3305.59
  5127.9 3320.84  5139.9 3320.65  5166.4 3318.73  5334.7 3336.35    5525 3347.99
#Mann= 4 ,-1 , 0
  4767.2    .085       0 4987.07     .05       0 5007.66    .055       0
  5139.9     .05       0
Bank Sta=4987.07,5007.66
Exp/Cntr=0.3,0.1

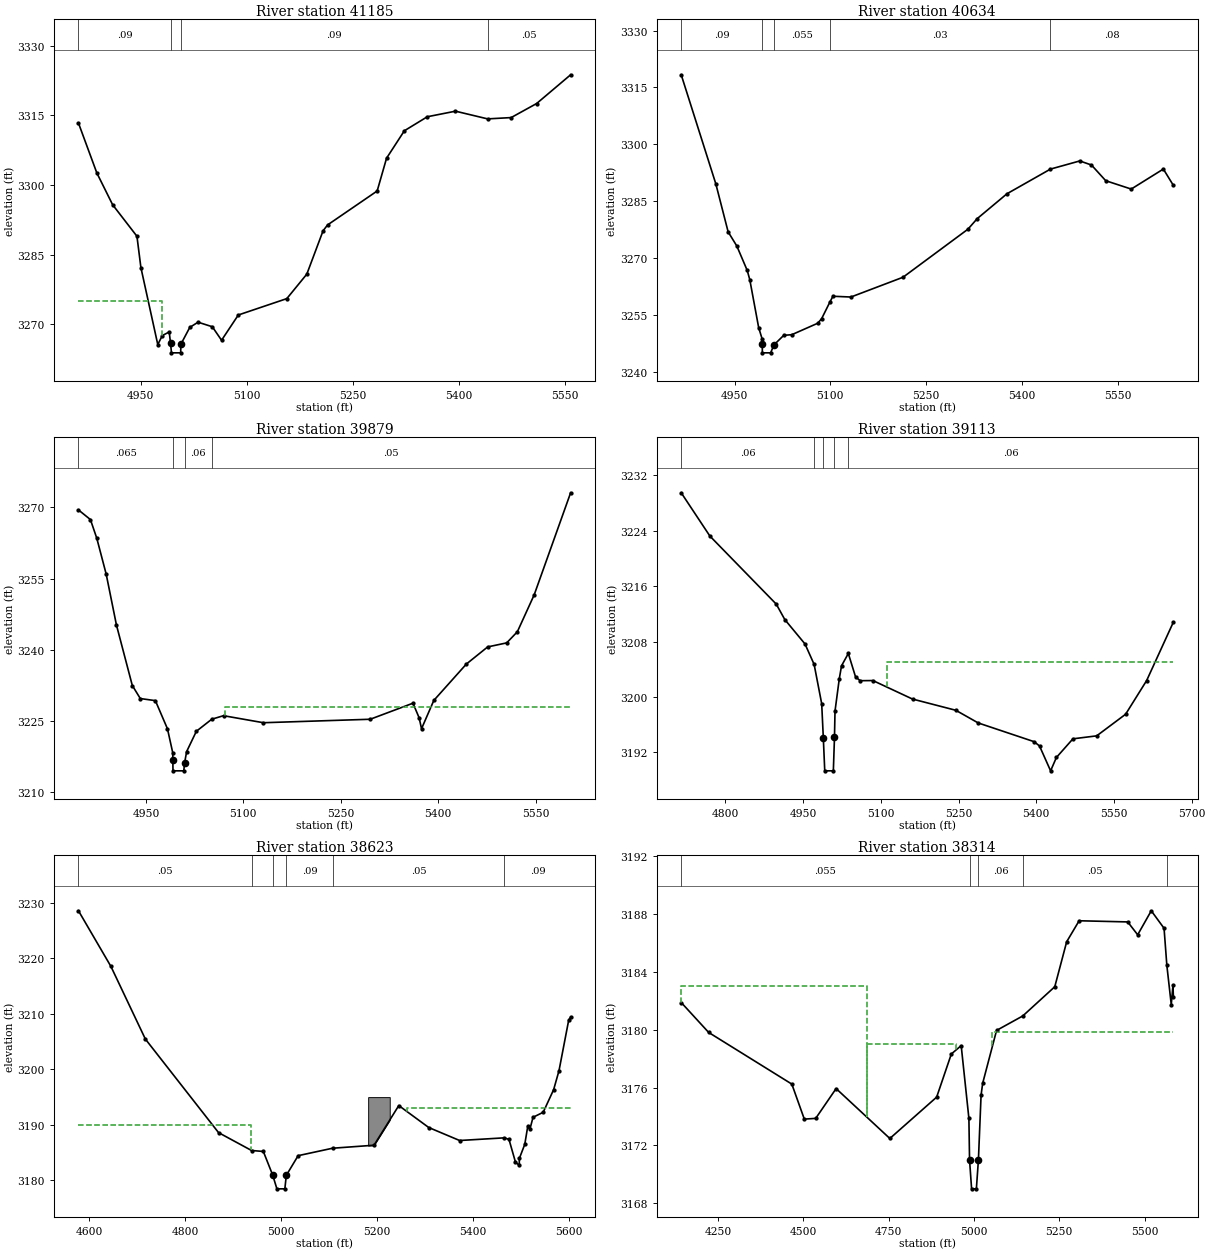
Type RM Length L Ch R = 1 ,41185   ,551,551,551
BEGIN DESCRIPTION:
Little_Rock_Crk_111
END DESCRIPTION:
XS GIS Cut Line= 2
      1081057.46       857699.97      1080740.62       858320.63
#Sta/Elev= 30
  4861.8 3313.32  4887.8 3302.58  4910.2 3295.72  4944.6 3288.94  4950.2 3282.19
  4974.1 3265.61  4980.5 3267.55  4990.3 3268.33 4992.18 3265.86  4993.5 3263.83
  5006.5 3263.83 5006.81 3265.68  5019.4 3269.31  5031.1 3270.43  5051.3 3269.45
  5064.4 3266.54  5088.1 3271.98  5156.8 3275.51  5185.1 3280.78  5208.1 3290.11
  5214.5 3291.38  5284.7 3298.69    5298 3305.75  5323.2 3311.66  5355.7 3314.68
  5395.6 3315.88  5441.1 3314.22  5474.4  3314.5  5510.5 3317.53  5558.6 3323.72
#Mann= 4 ,-1 , 0
  4861.8     .09       0 4992.18     .05       0 5006.81     .09       0
  5441.1     .05       0
#XS Ineff= 2 , 0
       0  4980.5    3275               0
Permanent Ineff=
       F       F
Bank Sta=4992.18,5006.81
Exp/Cntr=0.3,0.1

Type RM Length L Ch R = 1 ,40634   ,755,755,755
BEGIN DESCRIPTION:
Little_Rock_Crk_110
END DESCRIPTION:
XS GIS Cut Line= 2
      1080549.64        857443.9      1080319.61       858179.57
#Sta/Elev= 30
  4866.4 3318.32  4920.6 3289.54  4939.9 3276.86  4953.5 3273.13  4969.8 3266.68
  4973.8 3264.25  4987.7 3251.61  4993.3 3248.51 4993.33 3247.34  4993.5 3244.94
  5006.5 3244.94  5011.6 3247.03    5027 3249.56  5039.6 3249.73  5080.2 3252.75
  5086.3 3253.95  5099.5 3258.42    5104 3259.87  5132.2 3259.67  5213.8 3264.89
  5315.4 3277.56    5330 3280.36  5376.6 3286.92  5444.7 3293.43  5490.6 3295.58
  5508.9 3294.51  5531.3 3290.36  5571.2 3288.16  5621.5 3293.44  5637.2 3289.13
#Mann= 5 ,-1 , 0
  4866.4     .09       0 4993.33     .05       0  5011.6    .055       0
  5099.5     .03       0  5444.7     .08       0
Bank Sta=4993.33,5011.6
Exp/Cntr=0.3,0.1

Type RM Length L Ch R = 1 ,39879   ,766,766,766
BEGIN DESCRIPTION:
Little_Rock_Crk_109
END DESCRIPTION:
XS GIS Cut Line= 2
        1080044.       857127.06      1079447.21       857593.64
#Sta/Elev= 30
  4846.2 3269.46  4864.6 3267.43  4874.4  3263.5  4888.9 3255.93  4904.7 3245.21
  4929.1 3232.49  4941.4 3229.75  4964.6 3229.31  4983.2 3223.38  4991.3 3218.36
 4991.48 3216.83  4991.7 3214.53  5008.3 3214.53 5009.69 3216.28  5012.7 3218.58
  5027.7 3222.86  5051.4  3225.4  5069.5 3226.14  5130.9 3224.66  5295.3 3225.39
  5361.1 3228.77  5370.6  3225.7  5374.3  3223.4  5393.2 3229.35  5443.3 3237.01
  5476.1 3240.62  5505.4 3241.47  5521.8 3243.81  5547.7 3251.58  5603.8 3273.07
#Mann= 4 ,-1 , 0
  4846.2    .065       0 4991.48     .05       0 5009.69     .06       0
  5051.4     .05       0
#XS Ineff= 2 , 0
       0                 5072.39       0    3228
Permanent Ineff=
       F       F
Bank Sta=4991.48,5009.69
Exp/Cntr=0.3,0.1

Type RM Length L Ch R = 1 ,39113   ,490,490,490
BEGIN DESCRIPTION:
Little_Rock_Crk_108
END DESCRIPTION:
XS GIS Cut Line= 3
      1079764.05       856632.27      1079288.79        856651.8
      1078822.43       856739.14
#Sta/Elev= 30
  4714.6 3229.48    4770 3223.23  4898.1 3213.41  4914.6 3211.18  4953.6 3207.66
  4971.2 3204.71  4985.8 3199.04 4988.92 3194.12  4991.7 3189.35  5008.3 3189.35
  5010.5 3194.23  5011.5 3197.97  5019.8 3202.66  5024.1 3204.51  5037.2 3206.29
  5051.2  3202.9  5060.1 3202.36  5084.7 3202.38  5161.1 3199.71  5244.7 3198.09
    5288 3196.26  5395.8 3193.56  5406.3 3192.94  5427.7 3189.35  5438.9 3191.28
  5470.8 3193.97  5516.7  3194.4  5572.5 3197.52  5613.1 3202.38  5664.7 3210.81
#Mann= 5 ,-1 , 0
  4714.6     .06       0  4971.2     .09       0 4988.92     .05       0
  5010.5     .09       0  5037.2     .06       0
#XS Ineff= 2 , 0
       0                    5112       0    3205
Permanent Ineff=
       F       F
Bank Sta=4988.92,5010.5
Exp/Cntr=0.3,0.1

Type RM Length L Ch R = 1 ,38623   ,309,309,309
BEGIN DESCRIPTION:
little_rock_crk_a1
END DESCRIPTION:
XS GIS Cut Line= 4
      1079695.15       856093.17      1079464.98       856107.56
      1079072.96       856337.73      1078842.78       856589.49
#Sta/Elev= 30
  4577.9 3228.54  4645.6 3218.52  4717.4 3205.45    4870 3188.61  4938.9 3185.39
  4963.4 3185.22 4982.95 3180.96  4991.7 3178.49  5008.3 3178.49  5011.3 3180.92
    5036 3184.46  5107.7  3185.8  5194.2 3186.34  5245.9 3193.48  5308.3 3189.53
  5372.7 3187.19  5466.1 3187.67  5475.7 3187.38  5489.1 3183.32  5497.1  3182.7
  5497.3 3183.97  5508.6  3186.5  5514.8 3189.74  5519.2 3189.19  5525.8 3191.37
    5547 3192.27  5568.8 3196.35    5580 3199.77  5600.1 3208.82  5604.2 3209.42
#Mann= 6 ,-1 , 0
  4577.9     .05       0  4938.9     .09       0 4982.95     .05       0
  5011.3     .09       0  5107.7     .05       0  5466.1     .09       0
#XS Ineff= 2 , 0
       0  4937.7    3190  5263.1       0    3193
Permanent Ineff=
       F       F
#Block Obstruct= 1 ,-1
    5182    5227    3195
Bank Sta=4982.95,5011.3
Exp/Cntr=0.5,0.3

Type RM Length L Ch R = 1 ,38314   ,95,95,95
BEGIN DESCRIPTION:
Little_Rock_Crk_107
END DESCRIPTION:
XS GIS Cut Line= 6
      1079210.93        855108.8      1079087.17       855629.09
      1079123.52       855776.93      1079141.46       855868.76
       1079133.3       855987.23      1078905.33       856480.23
#Sta/Elev= 30
  4141.9 3181.88  4222.4 3179.81  4466.1 3176.24  4502.7 3173.82  4536.1 3173.87
  4595.9 3175.93  4753.4 3172.48  4890.6 3175.34  4933.6 3178.32  4962.5  3178.9
  4985.1 3173.87    4987    3171    4993    3169    5007    3169    5013    3171
  5020.8 3175.48  5025.5  3176.3  5066.2 3179.95    5143 3180.95  5236.8 3182.97
  5271.7 3186.08  5308.2 3187.53  5450.6 3187.45  5479.8 3186.56  5519.6 3188.22
  5557.1 3187.01  5565.3 3184.44  5578.2 3181.74  5583.2 3183.06  5584.4 3182.29
#Mann= 5 ,-1 , 0
  4141.9    .055       0    4987     .05       0    5013     .06       0
    5143     .05       0  5565.3     .08       0
#XS Ineff= 3 ,-1
  4141.9    4686    3183    4686    4946    3179    5054  5583.2 3179.87
Permanent Ineff=
       F       F       F
Bank Sta=4987,5013
Exp/Cntr=0.5,0.3