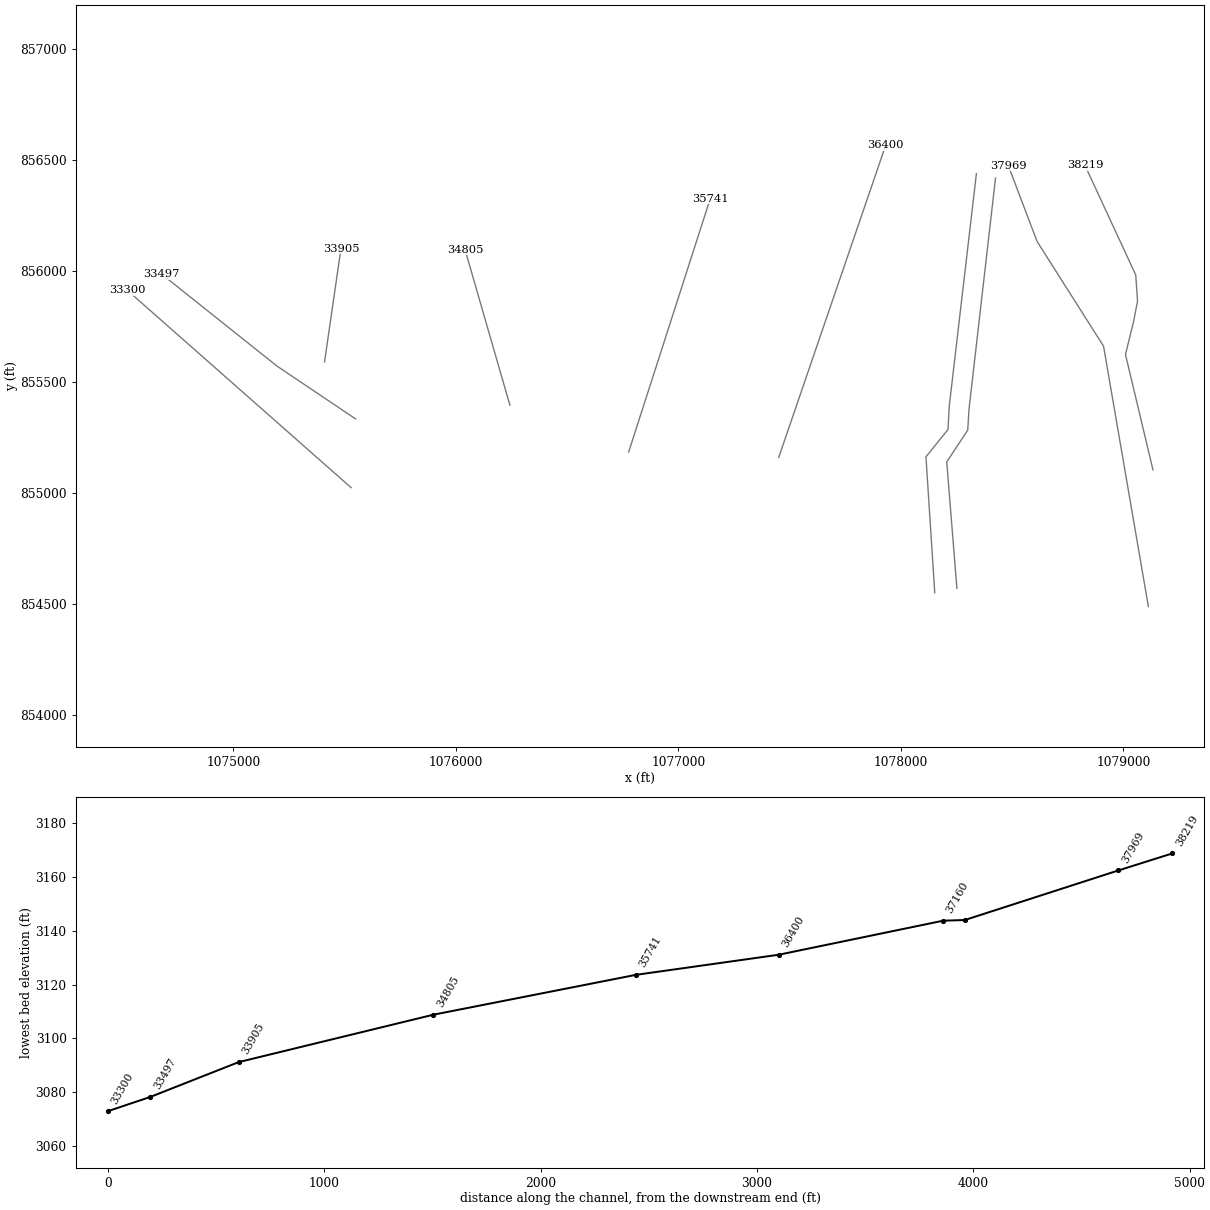
HEC-RAS study lds_little_rock_crk.prj: Little Rock Creek Limited Detail Study

--- lds_little_rock_crk.g01 (geometry) --- (continued)

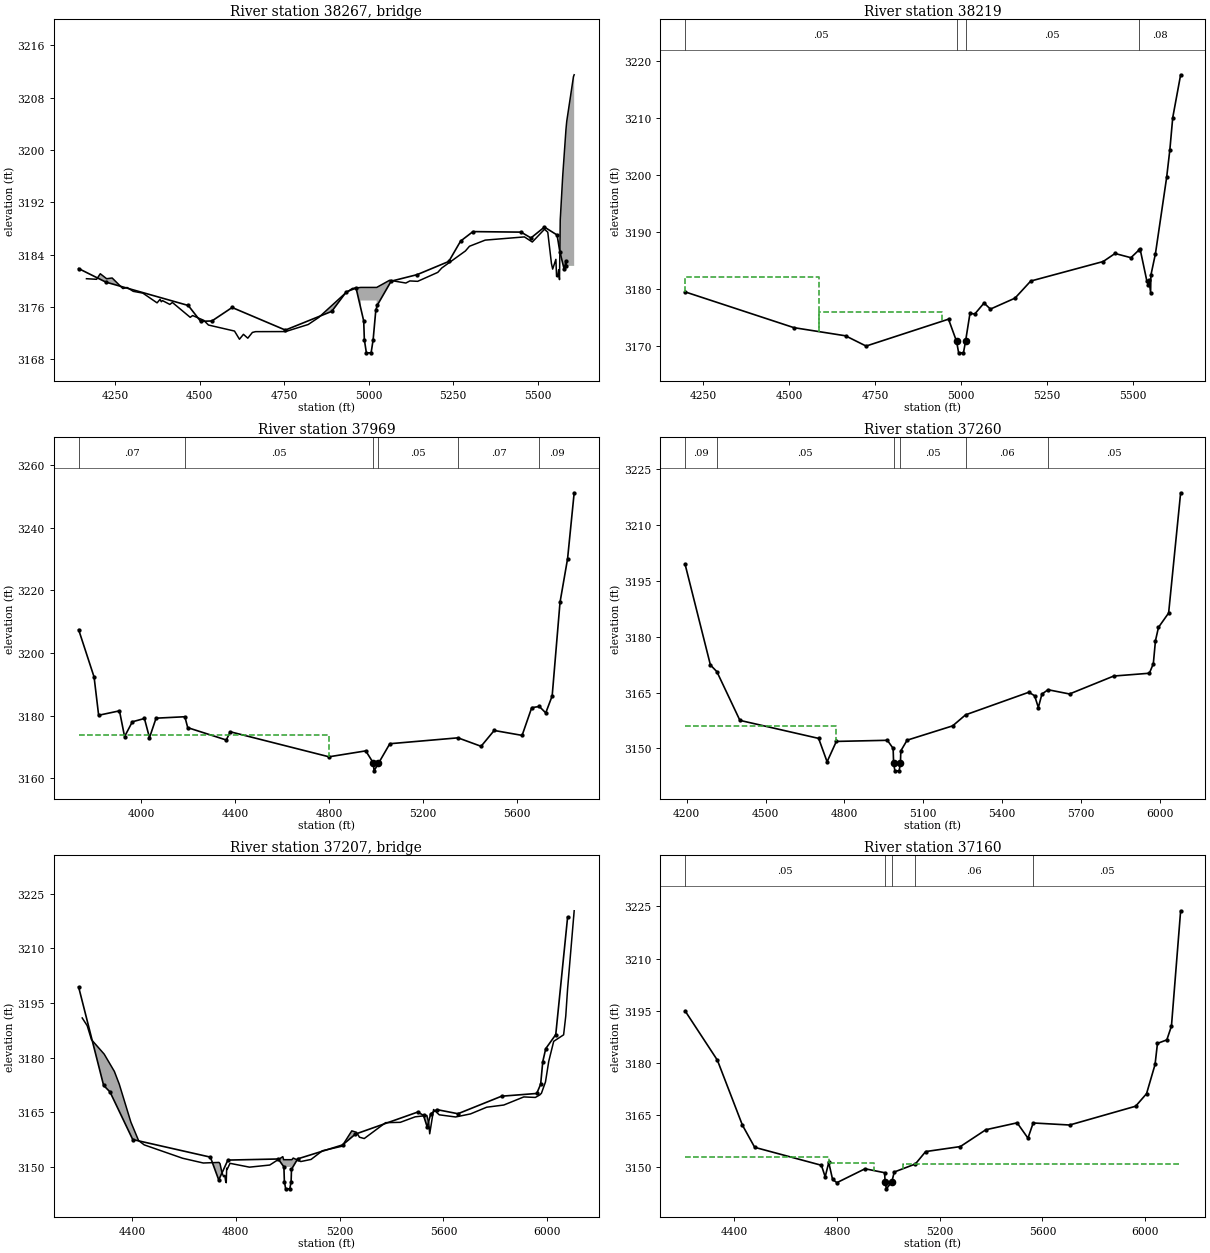
Type RM Length L Ch R = 3 ,38267   ,,,
BEGIN DESCRIPTION:
Little_Rock_Crk_106
Structure ID: Greene Creek Road bridge
Approximate Survey Structure
END DESCRIPTION:
Bridge Culvert--1,0,-1,-1, 0
Deck Dist Width WeirC Skew NumUp NumDn MinLoCord MaxHiCord MaxSubmerge Is_Ogee
30.5,33,3,0, 60, 60, , , , 0, 1,1,,
  4165.1    4195  4205.9  4224.7  4241.1  4272.8  4285.2  4303.4  4331.8  4373.9
  4382.8  4386.4    4390  4411.7  4419.2  4471.9  4479.1  4511.9  4525.9  4602.9
  4617.6  4629.4  4642.2  4655.9  4665.3  4753.9  4820.9  4852.1  4928.4  4951.6
  4976.5  4976.5  5023.5  5023.5  5061.6  5109.7  5121.6  5144.7  5204.2    5216
  5285.9  5297.9  5344.5  5460.4  5483.8  5519.8  5529.5  5540.4    5544  5553.5
  5555.5  5558.6  5561.5  5564.2  5566.4  5573.7  5583.3  5585.6  5605.5  5607.6
 3180.33 3180.24 3181.09 3180.33 3180.44 3178.82 3178.99  3178.4 3178.13 3176.64
 3177.18 3176.81 3176.98  3176.4  3176.7 3174.43  3174.7 3173.97 3173.25 3172.33
 3171.08 3171.83 3171.24 3172.12 3172.24 3172.25 3173.33 3174.41 3178.01 3178.85
    3179    3179    3179    3179 3180.09 3179.67 3179.99 3179.93  3181.3 3181.97
 3184.57 3185.29 3186.23 3186.72 3185.94 3187.89 3187.44 3182.65  3181.8 3183.29
 3180.68 3180.61 3181.69 3180.19 3189.32 3196.05 3203.14 3204.39 3211.22  3211.5
    3149    3149    3149    3149    3149    3149    3149    3149    3149    3149
    3149    3149    3149    3149    3149    3149    3149    3149    3149    3149
    3149    3149    3149    3149    3149    3149    3149    3149    3149    3149
    3149    3177    3177    3149    3149    3149    3149    3149    3149    3149
    3149    3149    3149    3149    3149    3149    3149    3149    3149    3149
    3149    3149    3149    3149    3149    3149    3149    3149    3149    3149
  4165.1    4195  4205.9  4224.7  4241.1  4272.8  4285.2  4303.4  4331.8  4373.9
  4382.8  4386.4    4390  4411.7  4419.2  4471.9  4479.1  4511.9  4525.9  4602.9
  4617.6  4629.4  4642.2  4655.9  4665.3  4753.9  4820.9  4852.1  4928.4  4951.6
  4976.5  4976.5  5023.5  5023.5  5061.6  5109.7  5121.6  5144.7  5204.2    5216
  5285.9  5297.9  5344.5  5460.4  5483.8  5519.8  5529.5  5540.4    5544  5553.5
  5555.5  5558.6  5561.5  5564.2  5566.4  5573.7  5583.3  5585.6  5605.5  5607.6
 3180.33 3180.24 3181.09 3180.33 3180.44 3178.82 3178.99  3178.4 3178.13 3176.64
 3177.18 3176.81 3176.98  3176.4  3176.7 3174.43  3174.7 3173.97 3173.25 3172.33
 3171.08 3171.83 3171.24 3172.12 3172.24 3172.25 3173.33 3174.41 3178.01 3178.85
    3179    3179    3179    3179 3180.09 3179.67 3179.99 3179.93  3181.3 3181.97
 3184.57 3185.29 3186.23 3186.72 3185.94 3187.89 3187.44 3182.65  3181.8 3183.29
 3180.68 3180.61 3181.69 3180.19 3189.32 3196.05 3203.14 3204.39 3211.22  3211.5
    3149    3149    3149    3149    3149    3149    3149    3149    3149    3149
    3149    3149    3149    3149    3149    3149    3149    3149    3149    3149
    3149    3149    3149    3149    3149    3149    3149    3149    3149    3149
    3149    3177    3177    3149    3149    3149    3149    3149    3149    3149
    3149    3149    3149    3149    3149    3149    3149    3149    3149    3149
    3149    3149    3149    3149    3149    3149    3149    3149    3149    3149
BR Coef= 1 , 1 , 0 ,1.25, 0 ,,,0.8,0,2,0,
WSPro=,,,, 1 ,,,, 0 ,,,, 0 ,,,,-1 ,-1 ,-1 , 0 , 0 , 0 , 0 , 0
BC Design=,, 0 ,, 0 ,,,,,,
BC HTab HWMax=3188.22

Type RM Length L Ch R = 1 ,38219   ,250,250,250
BEGIN DESCRIPTION:
Little_Rock_Crk_105
END DESCRIPTION:
XS GIS Cut Line= 6
      1079133.35       855104.12      1079009.59        855624.4
      1079045.94       855772.24      1079063.88       855864.07
      1079055.73       855982.54      1078827.75       856475.54
#Sta/Elev= 30
  4196.7 3179.45  4513.5 3173.17  4663.7 3171.74  4723.6 3169.94  4963.5 3174.66
    4987 3170.75    4993 3168.75    5007 3168.75    5013 3170.75    5026 3175.68
    5040 3175.57  5066.9 3177.49  5085.5 3176.43    5157 3178.35  5202.8 3181.35
  5413.8 3184.78  5448.2 3186.19  5494.5 3185.45  5517.3 3186.77    5521 3187.03
  5540.9 3181.36  5545.6 3180.63  5547.2 3181.52  5551.8 3179.33  5552.6 3182.37
  5565.9 3186.17  5598.5 3199.56  5607.8 3204.39  5616.2 3210.04  5639.2 3217.56
#Mann= 4 ,-1 , 0
  4196.7     .05       0    4987     .05       0    5013     .05       0
  5517.3     .08       0
#XS Ineff= 3 ,-1
  4196.7    4586    3182    4586    4945    3176    5055  5639.2    3176
Permanent Ineff=
       F       F       F
Bank Sta=4987,5013
Exp/Cntr=0.5,0.3

Type RM Length L Ch R = 1 ,37969   ,709,709,709
BEGIN DESCRIPTION:
little_rock_crk_a2
END DESCRIPTION:
XS GIS Cut Line= 4
      1079112.52       854489.13      1078911.11       855661.59
       1078612.6       856132.73      1078483.13        856474.4
#Sta/Elev= 30
  3732.1 3207.45    3798 3192.34  3817.4 3180.14  3906.2 3181.55    3928 3173.34
  3961.1 3178.06  4012.6 3179.11  4034.2 3172.98  4062.2 3179.21    4185 3179.67
  4197.2 3176.19  4361.5 3172.25  4378.6 3174.87  4799.5 3166.89  4956.3 3168.78
  4988.1 3164.96  4991.7 3162.41  5010.4  3164.8  5058.8 3171.06  5349.4 3172.94
  5447.9 3170.24  5503.8 3175.29  5622.8 3173.72  5663.8 3182.56  5696.3 3182.95
  5723.6 3180.89    5751 3186.31  5784.5  3216.2  5816.7 3230.09  5844.8 3251.12
#Mann= 6 ,-1 , 0
  3732.1     .07       0    4185     .05       0  4988.1     .05       0
  5010.4     .05       0  5349.4     .07       0  5696.3     .09       0
#XS Ineff= 2 , 0
       0  4799.5    3174               0
Permanent Ineff=
       F       F
Bank Sta=4988.1,5010.4
Exp/Cntr=0.5,0.3

Type RM Length L Ch R = 1 ,37260   ,100,100,100
BEGIN DESCRIPTION:
Little_Rock_Crk_104
END DESCRIPTION:
XS GIS Cut Line= 5
       1078251.9       854570.74      1078206.11        855140.2
      1078300.55       855283.28      1078306.27       855377.71
      1078425.43       856418.54
#Sta/Elev= 30
  4193.9 3199.38  4290.2 3172.38  4314.7  3170.6  4402.4 3157.53  4701.8  3152.7
    4734 3146.43  4769.2 3151.89  4963.2 3152.19  4985.2 3150.02    4987    3146
    4992    3144    5008    3144    5013    3146  5014.4 3149.35  5038.3 3152.22
  5211.6 3156.06  5260.8 3159.02  5501.5 3165.08  5523.4 3164.13  5537.5 3160.98
  5551.2 3164.58  5574.3 3165.75  5656.1 3164.61  5824.3 3169.42  5959.8 3170.17
  5974.9 3172.71    5983 3178.88  5994.5 3182.47  6033.1 3186.32  6078.8 3218.56
#Mann= 6 ,-1 , 0
  4193.9     .09       0  4314.7     .05       0    4987     .05       0
    5013     .05       0  5260.8     .06       0  5574.3     .05       0
#XS Ineff= 3 ,-1
  4193.9  4769.2    3156  4769.2  4937.5 3150.85  5062.5  6078.8 3151.62
Permanent Ineff=
       F       F       F
Bank Sta=4987,5013
Exp/Cntr=0.5,0.3

Type RM Length L Ch R = 3 ,37207   ,,,
BEGIN DESCRIPTION:
Little_Rock_Crk_103
Structure ID: Greene Creek Road side street 1
Approximate Survey Structure
END DESCRIPTION:
Bridge Culvert--1,0,-1,-1, 0
Deck Dist Width WeirC Skew NumUp NumDn MinLoCord MaxHiCord MaxSubmerge Is_Ogee
46.5,13,3,0, 60, 60, , , , 0, 1,1,,
  4207.7  4226.8  4243.4  4292.4  4331.7  4350.4  4395.3  4425.1  4446.8  4594.4
  4674.3  4735.1    4739  4745.7  4752.6  4757.2  4760.4  4762.9  4764.6  4766.3
  4777.4  4852.4  4930.6    4981    4984    4984    5016    5016    5021  5050.3
  5089.9  5133.5  5209.1  5246.8    5265  5276.4  5294.8  5377.2  5433.8  5491.2
  5536.2  5543.3  5547.2  5562.2    5584  5646.9  5704.4  5766.9  5832.8  5909.9
  5954.4  5971.5  5977.9  5993.5  6006.1  6025.2  6063.4  6071.7  6078.6  6104.1
 3190.89 3188.78 3184.93 3180.97 3176.22 3172.75 3162.31 3157.23 3156.06  3152.4
 3151.09 3151.25 3150.89 3148.64 3147.33  3147.7 3146.11 3145.68 3149.67 3149.31
    3151 3149.95 3150.53 3152.83    3152    3152    3152    3152 3152.45 3151.49
 3152.07 3154.45 3155.69 3159.91 3159.52 3158.17  3157.8 3162.16 3162.25 3163.76
 3164.13 3162.18  3159.1 3165.76 3164.31 3163.72 3164.56  3166.4    3167 3169.22
 3169.08 3169.77 3170.23 3173.33    3179 3184.48 3186.26 3191.43 3198.76  3220.3
    3124    3124    3124    3124    3124    3124    3124    3124    3124    3124
    3124    3124    3124    3124    3124    3124    3124    3124    3124    3124
    3124    3124    3124    3124    3124    3150    3150    3124    3124    3124
    3124    3124    3124    3124    3124    3124    3124    3124    3124    3124
    3124    3124    3124    3124    3124    3124    3124    3124    3124    3124
    3124    3124    3124    3124    3124    3124    3124    3124    3124    3124
  4207.7  4226.8  4243.4  4292.4  4331.7  4350.4  4395.3  4425.1  4446.8  4594.4
  4674.3  4735.1    4739  4745.7  4752.6  4757.2  4760.4  4762.9  4764.6  4766.3
  4777.4  4852.4  4930.6    4981    4984    4984    5016    5016    5021  5050.3
  5089.9  5133.5  5209.1  5246.8    5265  5276.4  5294.8  5377.2  5433.8  5491.2
  5536.2  5543.3  5547.2  5562.2    5584  5646.9  5704.4  5766.9  5832.8  5909.9
  5954.4  5971.5  5977.9  5993.5  6006.1  6025.2  6063.4  6071.7  6078.6  6104.1
 3190.89 3188.78 3184.93 3180.97 3176.22 3172.75 3162.31 3157.23 3156.06  3152.4
 3151.09 3151.25 3150.89 3148.64 3147.33  3147.7 3146.11 3145.68 3149.67 3149.31
    3151 3149.95 3150.53 3152.83    3152    3152    3152    3152 3152.45 3151.49
 3152.07 3154.45 3155.69 3159.91 3159.52 3158.17  3157.8 3162.16 3162.25 3163.76
 3164.13 3162.18  3159.1 3165.76 3164.31 3163.72 3164.56  3166.4    3167 3169.22
 3169.08 3169.77 3170.23 3173.33    3179 3184.48 3186.26 3191.43 3198.76  3220.3
    3124    3124    3124    3124    3124    3124    3124    3124    3124    3124
    3124    3124    3124    3124    3124    3124    3124    3124    3124    3124
    3124    3124    3124    3124    3124    3150    3150    3124    3124    3124
    3124    3124    3124    3124    3124    3124    3124    3124    3124    3124
    3124    3124    3124    3124    3124    3124    3124    3124    3124    3124
    3124    3124    3124    3124    3124    3124    3124    3124    3124    3124
BR Coef= 1 , 1 , 0 ,1.25, 0 ,,,0.8,0,2,0,
WSPro=,,,, 1 ,,,, 0 ,,,, 0 ,,,,-1 ,-1 ,-1 , 0 , 0 , 0 , 0 , 0
BC Design=,, 0 ,, 0 ,,,,,,
BC HTab HWMax=3218.56

Type RM Length L Ch R = 1 ,37160   ,760,760,760
BEGIN DESCRIPTION:
Little_Rock_Crk_102
END DESCRIPTION:
XS GIS Cut Line= 5
      1078152.33       854551.29      1078112.77       855163.14
      1078211.84       855286.14      1078217.56       855392.02
      1078339.56       856438.74
#Sta/Elev= 30
  4207.6 3194.94  4333.4 3180.76  4430.9 3162.08  4478.8 3155.69  4738.7 3150.53
  4753.4 3147.21  4767.4 3151.34  4782.3 3146.44  4799.2 3145.53  4908.7 3149.52
    4985 3148.39    4987 3145.75    4992 3143.75    5013 3145.75  5022.6 3148.59
  5104.9  3150.9  5144.9 3154.47  5280.1 3155.91  5379.4 3160.75  5501.4 3162.74
  5543.6 3158.33  5563.9  3162.7  5706.1 3162.11  5963.2 3167.52  6005.7 3171.13
  6038.8 3179.52  6048.2 3185.59  6084.7  3186.6  6102.7 3190.57  6138.5 3223.74
#Mann= 5 ,-1 , 0
  4207.6     .05       0    4987     .05       0    5013     .05       0
  5104.9     .06       0  5563.9     .05       0
#XS Ineff= 3 ,-1
  4207.6  4766.9    3153  4766.9  4943.5 3151.12  5056.5  6138.5    3151
Permanent Ineff=
       F       F       F
Bank Sta=4987,5013
Exp/Cntr=0.5,0.3

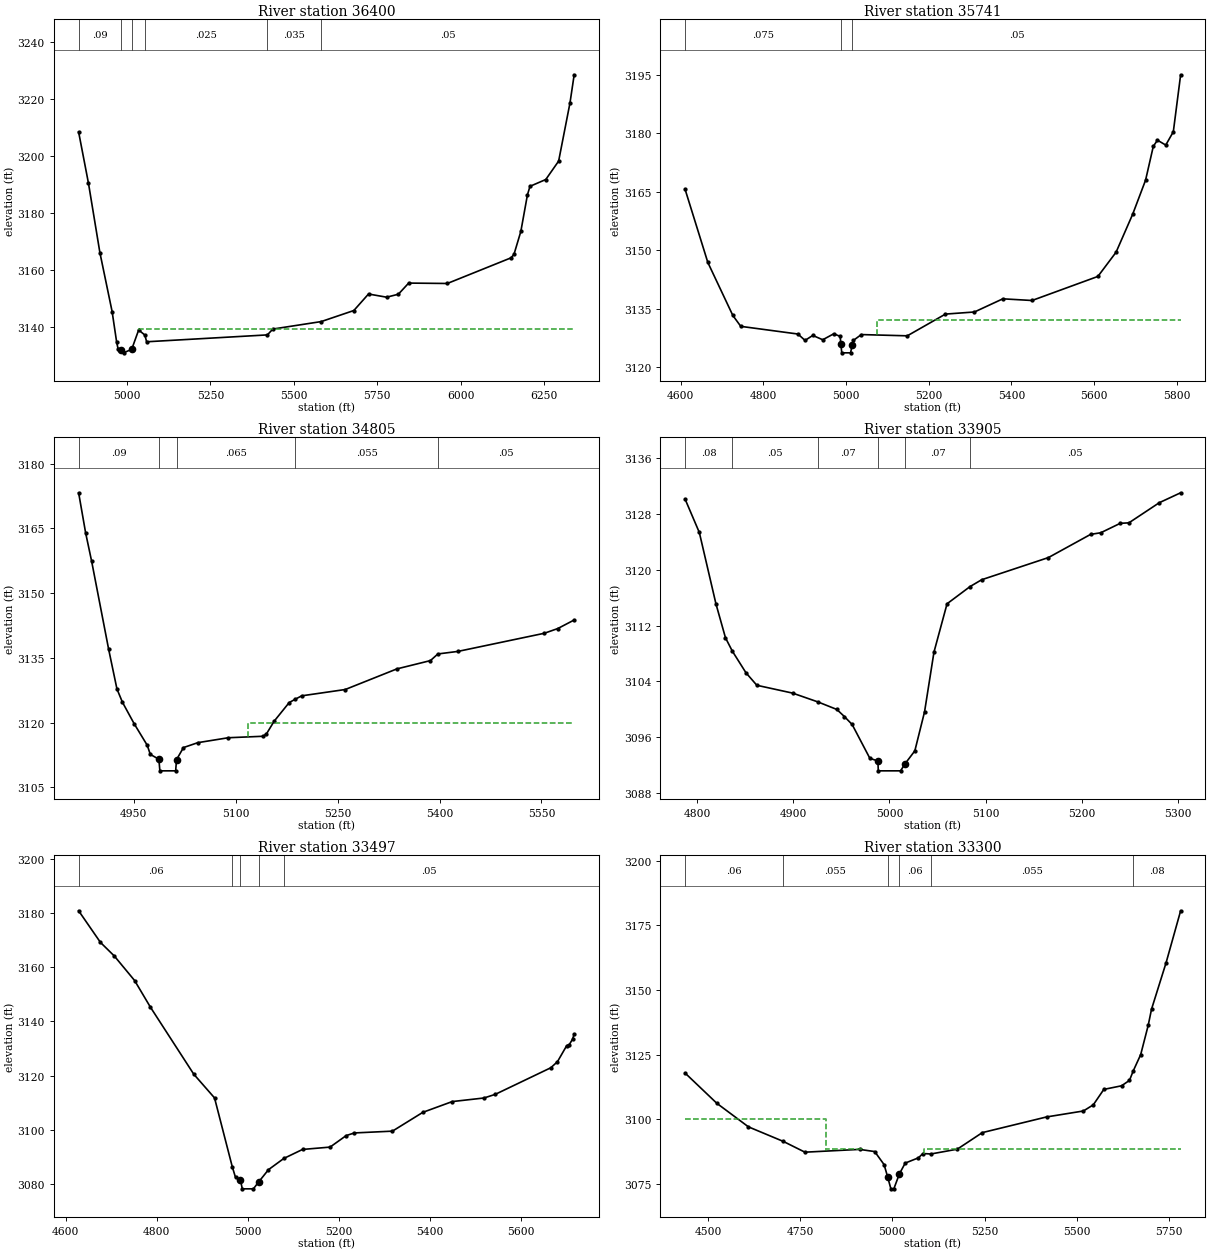
Type RM Length L Ch R = 1 ,36400   ,659,659,659
BEGIN DESCRIPTION:
Little_Rock_Crk_101
END DESCRIPTION:
XS GIS Cut Line= 2
      1077451.01       855160.65      1077931.74       856566.73
#Sta/Elev= 30
  4854.8 3208.52  4884.3 3190.57  4918.6 3166.21  4955.2 3145.58  4968.8 3134.86
  4972.9 3132.61  4982.2 3132.09  4989.4  3131.1    5014 3132.34  5034.8 3139.11
  5053.4 3137.34  5058.7 3134.98  5420.8 3137.39  5437.2 3139.44  5582.2 3142.06
  5680.1 3145.94  5724.1 3151.73  5778.4 3150.61  5813.6 3151.65  5844.5 3155.56
  5960.4 3155.42  6151.4 3164.41  6160.3 3165.63  6180.9 3173.69  6200.6 3186.48
  6208.3 3189.49  6255.6 3191.87  6294.2 3198.33  6328.2 3218.71  6340.8  3228.6
#Mann= 6 ,-1 , 0
  4854.8     .09       0  4982.2     .05       0    5014    .075       0
  5053.4    .025       0  5420.8    .035       0  5582.2     .05       0
#XS Ineff= 2 , 0
       0                    5035       0  3139.6
Permanent Ineff=
       F       F
Bank Sta=4982.2,5014
Exp/Cntr=0.3,0.1

Type RM Length L Ch R = 1 ,35741   ,936,936,936
BEGIN DESCRIPTION:
Little_Rock_Crk_100.5
END DESCRIPTION:
XS GIS Cut Line= 2
      1076776.49       855185.05      1077143.24       856326.54
#Sta/Elev= 30
  4610.4 3165.62  4665.4 3146.85  4725.9 3133.24  4745.1 3130.44  4883.4 3128.47
  4900.6 3126.83  4919.3 3128.11  4943.4    3127  4970.1 3128.53  4985.5 3127.87
 4987.24 3126.01  4989.4 3123.64  5010.6 3123.64    5015 3125.65  5017.6 3126.84
  5036.8 3128.33    5148 3128.01  5240.3 3133.59  5310.4 3134.13  5379.1 3137.51
  5449.7 3137.08  5609.1 3143.26  5653.1 3149.48  5693.3 3159.24  5724.5 3167.99
  5743.2 3176.68  5753.2 3178.24  5773.3 3176.99  5791.6 3180.41  5809.3 3195.04
#Mann= 3 , 0 , 0
  4610.4    .075       0 4987.24     .05       0    5015     .05       0
#XS Ineff= 2 , 0
       0                  5075.5       0    3132
Permanent Ineff=
       F       F
Bank Sta=4987.24,5015
Exp/Cntr=0.3,0.1

Type RM Length L Ch R = 1 ,34805   ,900,900,900
BEGIN DESCRIPTION:
Little_Rock_Crk_99
END DESCRIPTION:
XS GIS Cut Line= 2
      1076242.63       855395.55      1076040.81       856096.51
#Sta/Elev= 30
  4868.8 3173.25  4879.1 3163.96  4887.9 3157.42    4913 3136.98  4925.2  3127.8
  4933.2 3124.75  4950.4 3119.78  4969.8 3114.75  4974.3 3112.64  4986.9 3111.52
  4988.4 3108.83  5011.6 3108.83  5012.9 3111.42  5023.1 3114.22  5044.3 3115.36
  5089.2  3116.5  5140.3 3116.84  5145.1 3117.35  5156.6 3120.33  5178.7 3124.64
  5187.7 3125.43  5197.2 3126.21  5261.2 3127.67  5337.3 3132.45  5386.6 3134.37
  5397.6 3135.91  5427.1  3136.5  5554.2  3140.7    5574 3141.79  5598.2 3143.78
#Mann= 5 ,-1 , 0
  4868.8     .09       0  4986.9     .05       0  5012.9    .065       0
  5187.7    .055       0  5397.6     .05       0
#XS Ineff= 2 , 0
       0                    5118       0    3120
Permanent Ineff=
       F       F
Bank Sta=4986.9,5012.9
Exp/Cntr=0.3,0.1

Type RM Length L Ch R = 1 ,33905   ,408,408,408
BEGIN DESCRIPTION:
Little_Rock_Crk_98
END DESCRIPTION:
XS GIS Cut Line= 2
       1075409.3       855590.86      1075483.08       856100.85
#Sta/Elev= 30
  4787.5 3130.08  4802.3 3125.31  4819.6 3115.09  4829.5 3110.24  4836.6 3108.34
  4850.8 3105.24  4862.1 3103.45  4899.3 3102.33  4925.8 3101.06  4945.3 3099.99
  4953.2 3098.97  4961.2 3097.84  4979.6 3093.01    4988 3092.61  4988.4 3091.21
  5011.6 3091.21  5016.1  3092.2  5026.4 3094.07  5036.5 3099.65  5046.3  3108.2
  5059.9 3115.11  5083.8 3117.57  5095.9 3118.55  5165.3 3121.72  5209.2 3125.04
  5219.7 3125.27    5240 3126.62    5249 3126.69  5280.6 3129.57  5302.8 3130.99
#Mann= 6 ,-1 , 0
  4787.5     .08       0  4836.6     .05       0  4925.8     .07       0
    4988     .05       0  5016.1     .07       0  5083.8     .05       0
Bank Sta=4988,5016.1
Exp/Cntr=0.3,0.1

Type RM Length L Ch R = 1 ,33497   ,197,197,197
BEGIN DESCRIPTION:
little_rock_crk_a3
END DESCRIPTION:
XS GIS Cut Line= 3
      1075548.38       855334.31      1075195.92       855571.68
      1074678.02       855985.28
#Sta/Elev= 30
  4628.6 3180.75  4676.5 3169.09  4706.9 3164.09  4751.5 3155.04  4786.2 3145.22
  4881.3 3120.54  4926.9 3111.79    4966 3086.31    4973 3082.47  4983.7 3081.59
  4987.8 3078.28  5012.2 3078.28 5023.52 3080.77  5045.3 3085.34    5079 3089.48
  5120.1  3092.8  5180.5 3093.66    5216 3097.92  5233.9 3098.88  5317.4 3099.54
  5384.2 3106.48  5448.7 3110.44  5518.4 3111.76  5543.1  3113.1  5664.9 3122.89
  5679.6 3125.13  5699.8 3131.02  5705.5 3131.43  5712.7 3133.39  5716.3 3135.31
#Mann= 5 ,-1 , 0
  4628.6     .06       0    4966     .09       0  4983.7     .05       0
 5023.52     .09       0    5079     .05       0
Bank Sta=4983.7,5023.52
Exp/Cntr=0.5,0.3

Type RM Length L Ch R = 1 ,33300   ,64,64,64
BEGIN DESCRIPTION:
Little_Rock_Crk_97
END DESCRIPTION:
XS GIS Cut Line= 2
      1075528.66       855024.46      1074521.71       855914.21
#Sta/Elev= 30
    4438 3117.81  4524.2 3106.08  4609.8 3096.97  4704.5 3091.32    4763 3087.16
  4911.1 3088.24  4952.1  3087.4  4977.6 3082.34 4987.11 3077.64    4996 3072.96
    5004 3072.96  5019.2 3078.78  5034.9 3082.94  5070.7 3084.97  5082.8 3086.64
  5104.4 3086.46    5176 3088.32  5243.9 3094.74  5418.1 3100.81    5518 3103.12
  5544.9 3105.51  5573.4 3111.48  5621.5 3112.88    5643 3114.98  5653.1 3118.62
  5673.4 3124.97  5693.7 3136.27  5702.8 3142.57  5742.3 3160.58  5781.7 3180.68
#Mann= 6 ,-1 , 0
    4438     .06       0  4704.5    .055       0 4987.11    .045       0
  5019.2     .06       0  5104.4    .055       0  5653.1     .08       0
#XS Ineff= 3 ,-1
    4438  4820.8    3100    4821  4916.8 3088.23    5085  5781.7 3088.23
Permanent Ineff=
       F       F       F
Bank Sta=4987.11,5019.2
Exp/Cntr=0.5,0.3