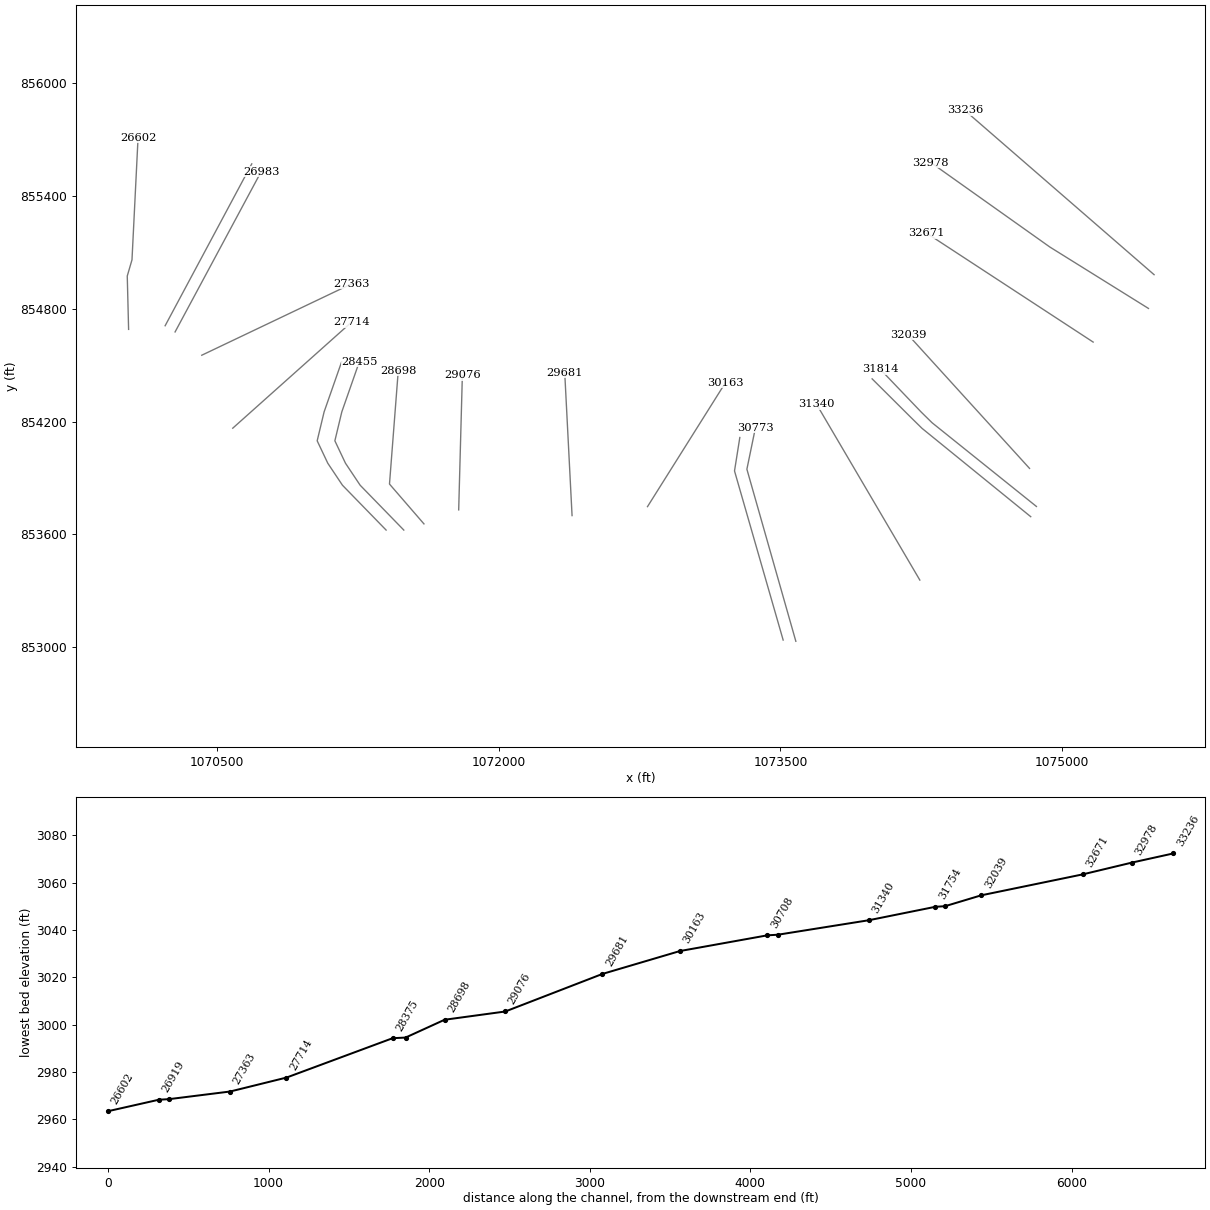
HEC-RAS study lds_little_rock_crk.prj: Little Rock Creek Limited Detail Study

--- lds_little_rock_crk.g01 (geometry) --- (continued)

Type RM Length L Ch R = 3 ,33267   ,,,
BEGIN DESCRIPTION:
Little_Rock_Crk_96
Structure ID: Roan Mountain Road side street 6
Approximate Survey Structure
END DESCRIPTION:
Bridge Culvert--1,0,-1,-1, 0
Deck Dist Width WeirC Skew NumUp NumDn MinLoCord MaxHiCord MaxSubmerge Is_Ogee
24,15,3,0, 60, 60, , , , 0, 0.5,0.5,,
  4431.1  4433.7  4440.3  4457.4  4460.7  4476.8  4484.7  4493.6  4512.9  4544.4
  4571.6  4615.2  4626.5    4645  4654.3  4695.5  4711.5  4737.5  4794.5  4818.6
  4831.3    4839  4845.9  4896.7  4922.2    4946    4961    4967    4967    5033
    5033    5104  5106.6    5132    5148  5279.6    5373    5414    5470  5481.8
  5491.6  5501.4  5529.8  5542.8  5555.1    5566  5591.4  5604.9  5617.7  5640.5
    5651  5658.8  5669.6  5674.4    5678  5693.4  5726.4    5738  5749.7  5760.7
 3121.63 3120.69 3119.22 3114.63 3113.14 3109.52 3108.46 3106.59 3104.47 3099.44
 3095.86 3091.85 3090.35  3089.3 3089.16 3086.92 3085.64 3085.34 3085.36 3086.33
 3087.27 3086.63 3086.47 3087.16 3087.24 3086.92    3085  3084.5  3084.5  3084.5
  3084.5    3085 3086.05 3086.54 3087.17 3094.63 3098.25 3099.02 3098.65 3099.17
  3099.1 3100.42 3103.37 3105.17 3109.06 3111.07 3111.14 3111.57 3112.34 3114.41
 3116.14 3119.47 3122.92 3123.93 3126.09  3134.2 3151.22 3156.48 3162.37 3167.45
 3052.96 3052.96 3052.96 3052.96 3052.96 3052.96 3052.96 3052.96 3052.96 3052.96
 3052.96 3052.96 3052.96 3052.96 3052.96 3052.96 3052.96 3052.96 3052.96 3052.96
 3052.96 3052.96 3052.96 3052.96 3052.96 3052.96 3052.96 3052.96  3082.5  3082.5
 3052.96 3052.96 3052.96 3052.96 3052.96 3052.96 3052.96 3052.96 3052.96 3052.96
 3052.96 3052.96 3052.96 3052.96 3052.96 3052.96 3052.96 3052.96 3052.96 3052.96
 3052.96 3052.96 3052.96 3052.96 3052.96 3052.96 3052.96 3052.96 3052.96 3052.96
  4431.1  4433.7  4440.3  4457.4  4460.7  4476.8  4484.7  4493.6  4512.9  4532.7
  4544.4  4571.6  4615.2  4626.5    4645  4654.3  4695.5  4703.9  4711.5  4774.4
  4779.2  4798.3    4961    4967    4967    5033    5033    5104    5148  5170.1
  5182.3  5239.9  5279.6  5291.3  5310.4    5373    5414    5470  5481.8  5491.6
  5496.1  5501.4  5529.8  5542.8  5555.1    5566  5591.4  5604.9  5617.7  5640.5
    5651  5658.8  5669.6  5674.4    5678  5693.4  5726.4    5738  5749.7  5760.7
 3121.63 3120.69 3119.22 3114.63 3113.14 3109.52 3108.46 3106.59 3104.47 3101.45
 3099.44 3095.86 3091.85 3090.35  3089.3 3089.16 3086.92 3086.39 3085.64 3085.24
 3085.43 3085.45    3085  3084.5  3084.5  3084.5  3084.5    3085 3087.17  3088.6
 3089.01 3092.55 3094.63 3094.97 3095.97 3098.25 3099.02 3098.65 3099.17  3099.1
 3099.55 3100.42 3103.37 3105.17 3109.06 3111.07 3111.14 3111.57 3112.34 3114.41
 3116.14 3119.47 3122.92 3123.93 3126.09  3134.2 3151.22 3156.48 3162.37 3167.45
 3052.96 3052.96 3052.96 3052.96 3052.96 3052.96 3052.96 3052.96 3052.96 3052.96
 3052.96 3052.96 3052.96 3052.96 3052.96 3052.96 3052.96 3052.96 3052.96 3052.96
 3052.96 3052.96 3052.96 3052.96  3082.5  3082.5 3052.96 3052.96 3052.96 3052.96
 3052.96 3052.96 3052.96 3052.96 3052.96 3052.96 3052.96 3052.96 3052.96 3052.96
 3052.96 3052.96 3052.96 3052.96 3052.96 3052.96 3052.96 3052.96 3052.96 3052.96
 3052.96 3052.96 3052.96 3052.96 3052.96 3052.96 3052.96 3052.96 3052.96 3052.96
BR Coef= 1 , 1 , 0 ,1, 0 ,,,0.8,0,2,0,
WSPro=,,,, 1 ,,,, 0 ,,,, 0 ,,,,-1 ,-1 ,-1 , 0 , 0 , 0 , 0 , 0
BC Design=,, 0 ,, 0 ,,,,,,
BC HTab HWMax=3180.68

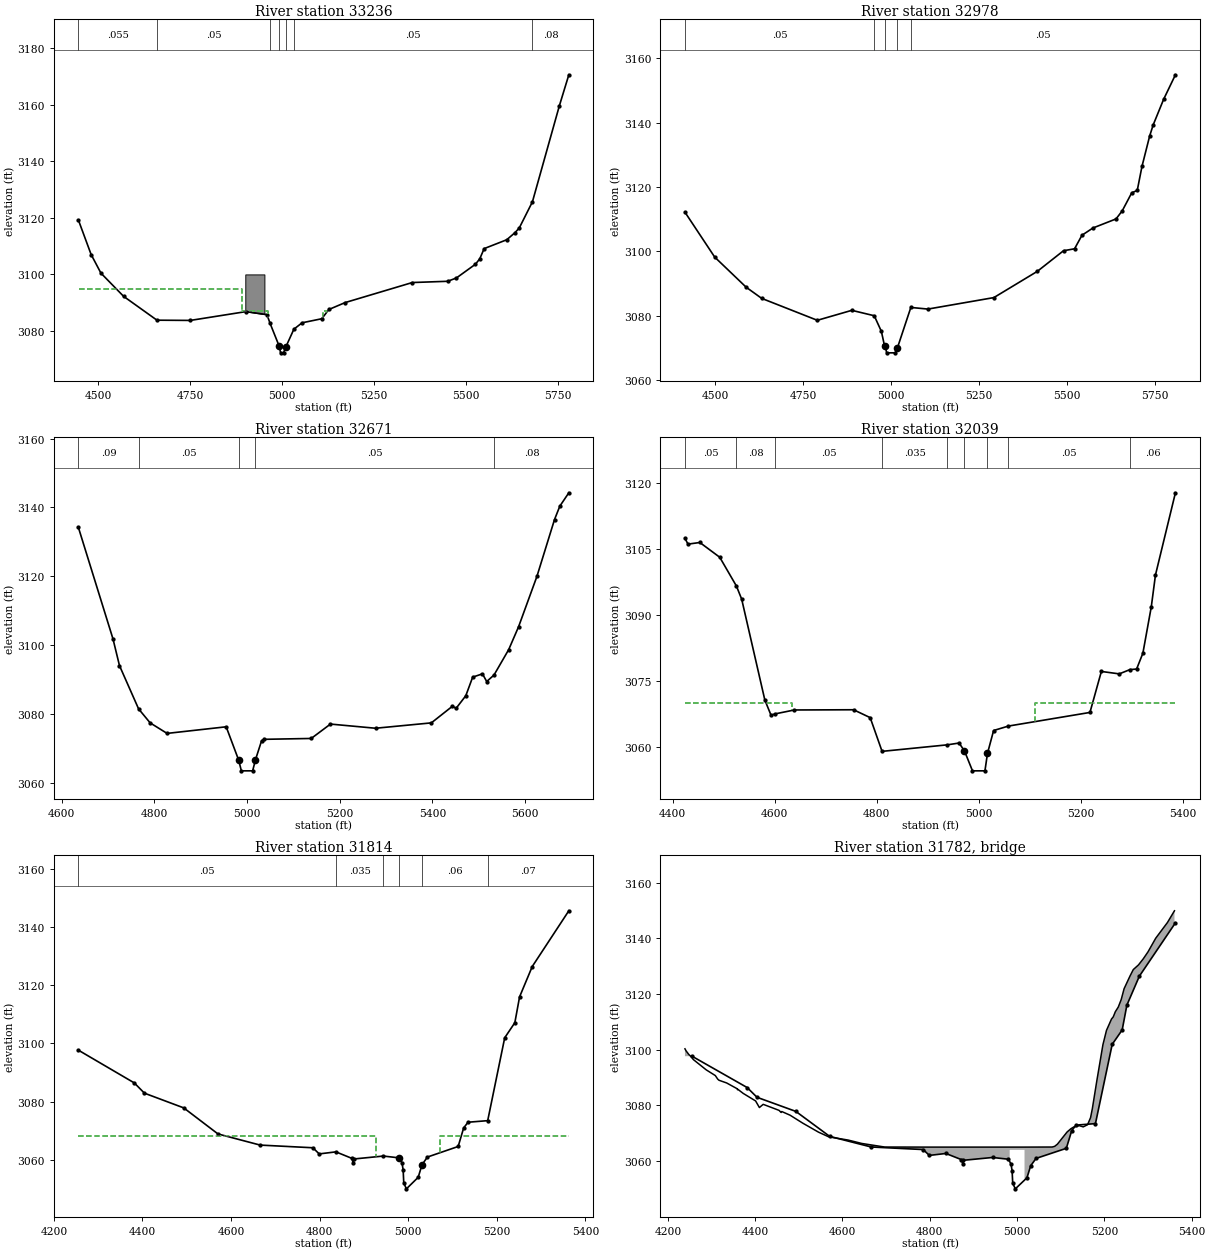
Type RM Length L Ch R = 1 ,33236   ,258,258,258
BEGIN DESCRIPTION:
Little_Rock_Crk_95
END DESCRIPTION:
XS GIS Cut Line= 2
      1075488.28       854981.91      1074481.34       855856.48
#Sta/Elev= 30
  4446.1 3119.22  4480.8 3107.01  4507.5 3100.44  4569.1 3092.25  4659.8 3083.83
  4750.6 3083.75  4902.2 3086.87  4958.9  3085.8  4967.5 3082.67    4992 3074.71
    4996  3072.3    5004  3072.3 5009.66 3074.22  5032.1 3080.65 5054.41 3082.91
 5107.84 3084.34  5127.3 3087.61  5171.7 3090.06  5354.2 3097.13  5450.5 3097.57
  5474.3 3098.76  5525.8 3103.59  5537.6 3105.51  5549.5 3109.11    5611 3112.24
  5633.5 3114.76    5645  3116.4  5680.8 3125.64  5754.2 3159.62  5779.8  3170.5
#Mann= 7 ,-1 , 0
  4446.1    .055       0  4659.8     .05       0  4967.5     .09       0
    4992    .052       0 5009.66     .09       0  5032.1     .05       0
  5680.8     .08       0
#XS Ineff= 3 ,-1
  4446.7    4891    3095    4891 4961.75    3087 5110.35 5120.95    3087
Permanent Ineff=
       T       F       F
#Block Obstruct= 1 ,-1
    4900    4952    3100
Bank Sta=4992,5009.66
Exp/Cntr=0.5,0.3

Type RM Length L Ch R = 1 ,32978   ,307,307,307
BEGIN DESCRIPTION:
little_rock_crk_a4
END DESCRIPTION:
XS GIS Cut Line= 3
      1075458.46       854802.03      1074933.37       855129.31
      1074300.39       855578.87
#Sta/Elev= 30
  4414.1 3112.17  4498.7 3098.21  4588.4 3088.82  4632.5 3085.36  4790.6 3078.55
  4888.7 3081.65  4952.5 3079.97  4972.8 3075.11  4981.4 3070.79  4983.9 3070.48
  4987.8 3068.43  5012.2 3068.43  5018.3 3069.93  5056.6 3082.55  5105.1 3082.04
  5292.7 3085.61  5416.5 3093.78  5490.9 3100.19  5522.3 3100.79  5543.4 3105.01
  5574.6 3107.26  5640.3 3110.08  5657.9 3112.59    5685 3118.21  5700.6 3118.93
  5714.1 3126.42  5735.9 3135.86  5745.9  3139.3  5775.7 3147.29  5809.2 3154.91
#Mann= 5 ,-1 , 0
  4414.1     .05       0  4952.5     .09       0  4983.9     .05       0
  5018.3     .09       0  5056.6     .05       0
Bank Sta=4983.9,5018.3
Exp/Cntr=0.3,0.1

Type RM Length L Ch R = 1 ,32671   ,632,632,632
BEGIN DESCRIPTION:
Little_Rock_Crk_94
END DESCRIPTION:
XS GIS Cut Line= 2
      1075164.07       854622.98      1074278.66       855202.41
#Sta/Elev= 30
  4636.2 3134.19  4710.9 3101.77  4724.9 3094.01  4766.1 3081.45  4791.1 3077.37
  4827.6 3074.32  4955.1 3076.24  4982.2  3066.5  4987.8 3063.44  5012.2 3063.44
 5018.35 3066.68  5031.5 3072.19  5036.7  3072.6  5138.6 3072.85  5180.1 3077.03
  5277.4 3075.82  5397.8 3077.38  5443.2 3082.21  5451.2 3081.61  5472.1 3085.27
  5486.9 3090.67    5508 3091.63  5517.2  3089.4  5532.9 3091.27  5564.6 3098.66
  5585.8 3105.26  5625.5 3119.93  5663.5 3136.47    5675 3140.37  5694.4 3144.25
#Mann= 5 ,-1 , 0
  4636.2     .09       0  4766.1     .05       0  4982.2     .05       0
 5018.35     .05       0  5532.9     .08       0
Bank Sta=4982.2,5018.35
Exp/Cntr=0.3,0.1

Type RM Length L Ch R = 1 ,32039   ,225,225,225
BEGIN DESCRIPTION:
Little_Rock_Crk_93
END DESCRIPTION:
XS GIS Cut Line= 2
      1074825.53       853950.24      1074178.83       854662.04
#Sta/Elev= 30
    4424 3107.35  4429.9 3106.03  4453.2  3106.4  4492.2 3103.05  4524.9 3096.52
  4535.2 3093.55  4580.6 3070.67  4592.8  3067.2  4600.2  3067.5  4638.5  3068.4
  4754.6 3068.45  4787.2 3066.66  4810.5 3059.01  4938.5 3060.49  4961.5  3060.9
  4972.1  3059.1  4987.8 3054.59  5012.2 3054.59  5017.2 3058.55  5029.2 3063.74
  5058.3 3064.75  5218.1 3067.84  5240.5 3077.14  5275.6 3076.59  5296.3 3077.55
  5309.6 3077.69  5321.9 3081.28  5338.4 3091.82  5346.6 3099.04  5385.7 3117.68
#Mann= 9 ,-1 , 0
    4424     .05       0  4524.9     .08       0  4600.2     .05       0
  4810.5    .035       0  4938.5     .09       0  4972.1     .05       0
  5017.2     .09       0  5058.3     .05       0  5296.3     .06       0
#XS Ineff= 2 , 0
       0  4634.4    3070  5110.2       0    3070
Permanent Ineff=
       F       F
Bank Sta=4972.1,5017.2
Exp/Cntr=0.5,0.3

Type RM Length L Ch R = 1 ,31814   ,60,60,60
BEGIN DESCRIPTION:
Little_Rock_Crk_92.75
END DESCRIPTION:
XS GIS Cut Line= 4
      1074862.32       853747.49      1074306.84       854193.44
      1074249.67        854249.6      1074032.02       854477.28
#Sta/Elev= 30
  4255.3 3097.67  4381.6 3086.41  4404.4 3082.89  4493.2 3077.83  4570.6 3068.86
  4665.8 3065.04  4784.8 3064.12    4799 3062.01  4836.8 3062.71  4872.6 3060.49
    4876 3058.85  4877.1 3060.26  4943.9 3061.27 4980.17 3060.64  4986.1  3058.9
 4988.63 3056.45    4990    3052    4996    3050  5022.6 3053.97  5031.2 3058.29
  5043.4 3060.93  5112.8 3064.56  5125.2 3070.93  5135.1  3072.9  5179.5 3073.44
  5217.9 3101.93  5240.8 3107.12  5251.5 3116.01  5280.1 3126.43  5362.7 3145.59
#Mann= 6 ,-1 , 0
  4255.3     .05       0  4836.8    .035       0  4943.9     .05       0
 4980.17     .05       0  5031.2     .06       0  5179.5     .07       0
#XS Ineff= 2 , 0
       0    4928    3068    5072       0    3068
Permanent Ineff=
       F       F
Bank Sta=4980.17,5031.2
Exp/Cntr=0.5,0.3

Type RM Length L Ch R = 3 ,31782   ,,,
BEGIN DESCRIPTION:
Little_Rock_Crk_92.5
Structure ID: Roan Mountain Road side street 5
Approximate Survey Structure
END DESCRIPTION:
Bridge Culvert--1,0,-1,-1, 0
Deck Dist Width WeirC Skew NumUp NumDn MinLoCord MaxHiCord MaxSubmerge Is_Ogee
24,14,3,0, 60, 60, , , , 0, 1,1,,
  4239.2  4241.6    4248  4255.1  4258.1  4287.9  4308.7  4314.2  4317.2  4334.7
  4358.8  4359.3  4360.4  4372.7    4401  4409.7  4418.4  4454.6  4459.6    4461
    4480  4508.9    4545  4568.5  4613.1    4644  4696.6  4798.7    4983    4983
    5017    5017  5080.4  5086.1  5092.4  5114.6  5123.5  5130.2  5142.2  5151.5
  5161.4  5168.3  5172.4  5182.8  5196.6  5204.8  5216.3  5220.3  5225.1  5231.8
  5238.6  5245.1  5258.7  5266.2  5278.1    5289  5299.9  5317.6  5344.4  5360.5
 3100.32 3099.62 3098.28 3097.24  3096.5 3092.76 3090.71 3089.44 3089.02 3088.05
 3085.97 3085.63 3085.76 3084.29 3081.59 3079.22 3080.37 3078.21 3077.44 3077.78
 3076.47 3073.62 3070.38 3068.69 3067.53 3066.32 3065.03    3065    3065    3065
    3065    3065 3065.03 3065.28 3066.06 3070.44 3071.63 3072.26 3072.71 3072.27
 3073.04 3075.58 3078.83 3088.98 3101.79 3106.97 3111.03 3111.81 3113.67 3115.33
 3118.07 3121.92  3126.5  3128.8 3130.48 3132.66 3135.17 3140.08 3145.71 3149.93
    3030    3030    3030    3030    3030    3030    3030    3030    3030    3030
    3030    3030    3030    3030    3030    3030    3030    3030    3030    3030
    3030    3030    3030    3030    3030    3030    3030    3030    3030    3064
    3064    3030    3030    3030    3030    3030    3030    3030    3030    3030
    3030    3030    3030    3030    3030    3030    3030    3030    3030    3030
    3030    3030    3030    3030    3030    3030    3030    3030    3030    3030
  4239.2  4241.6    4248  4255.1  4258.1  4287.9  4308.7  4314.2  4317.2  4334.7
  4358.8  4359.3  4360.4  4372.7    4401  4409.7  4418.4  4454.6  4459.6    4461
    4480  4508.9    4545  4568.5  4613.1    4644  4696.6  4798.7    4983    4983
    5017    5017  5080.4  5086.1  5092.4  5114.6  5123.5  5130.2  5142.2  5151.5
  5161.4  5168.3  5172.4  5182.8  5196.6  5204.8  5216.3  5220.3  5225.1  5231.8
  5238.6  5245.1  5258.7  5266.2  5278.1    5289  5299.9  5317.6  5344.4  5360.5
 3100.32 3099.62 3098.28 3097.24  3096.5 3092.76 3090.71 3089.44 3089.02 3088.05
 3085.97 3085.63 3085.76 3084.29 3081.59 3079.22 3080.37 3078.21 3077.44 3077.78
 3076.47 3073.62 3070.38 3068.69 3067.53 3066.32 3065.03    3065    3065    3065
    3065    3065 3065.03 3065.28 3066.06 3070.44 3071.63 3072.26 3072.71 3072.27
 3073.04 3075.58 3078.83 3088.98 3101.79 3106.97 3111.03 3111.81 3113.67 3115.33
 3118.07 3121.92  3126.5  3128.8 3130.48 3132.66 3135.17 3140.08 3145.71 3149.93
    3030    3030    3030    3030    3030    3030    3030    3030    3030    3030
    3030    3030    3030    3030    3030    3030    3030    3030    3030    3030
    3030    3030    3030    3030    3030    3030    3030    3030    3030    3064
    3064    3030    3030    3030    3030    3030    3030    3030    3030    3030
    3030    3030    3030    3030    3030    3030    3030    3030    3030    3030
    3030    3030    3030    3030    3030    3030    3030    3030    3030    3030
BR Coef= 1 , 1 , 0 ,1.25, 0 ,,,0.8,0,2,0,
WSPro=,,,, 1 ,,,, 0 ,,,, 0 ,,,,-1 ,-1 ,-1 , 0 , 0 , 0 , 0 , 0
BC Design=,, 0 ,, 0 ,,,,,,
BC HTab HWMax=3145.59

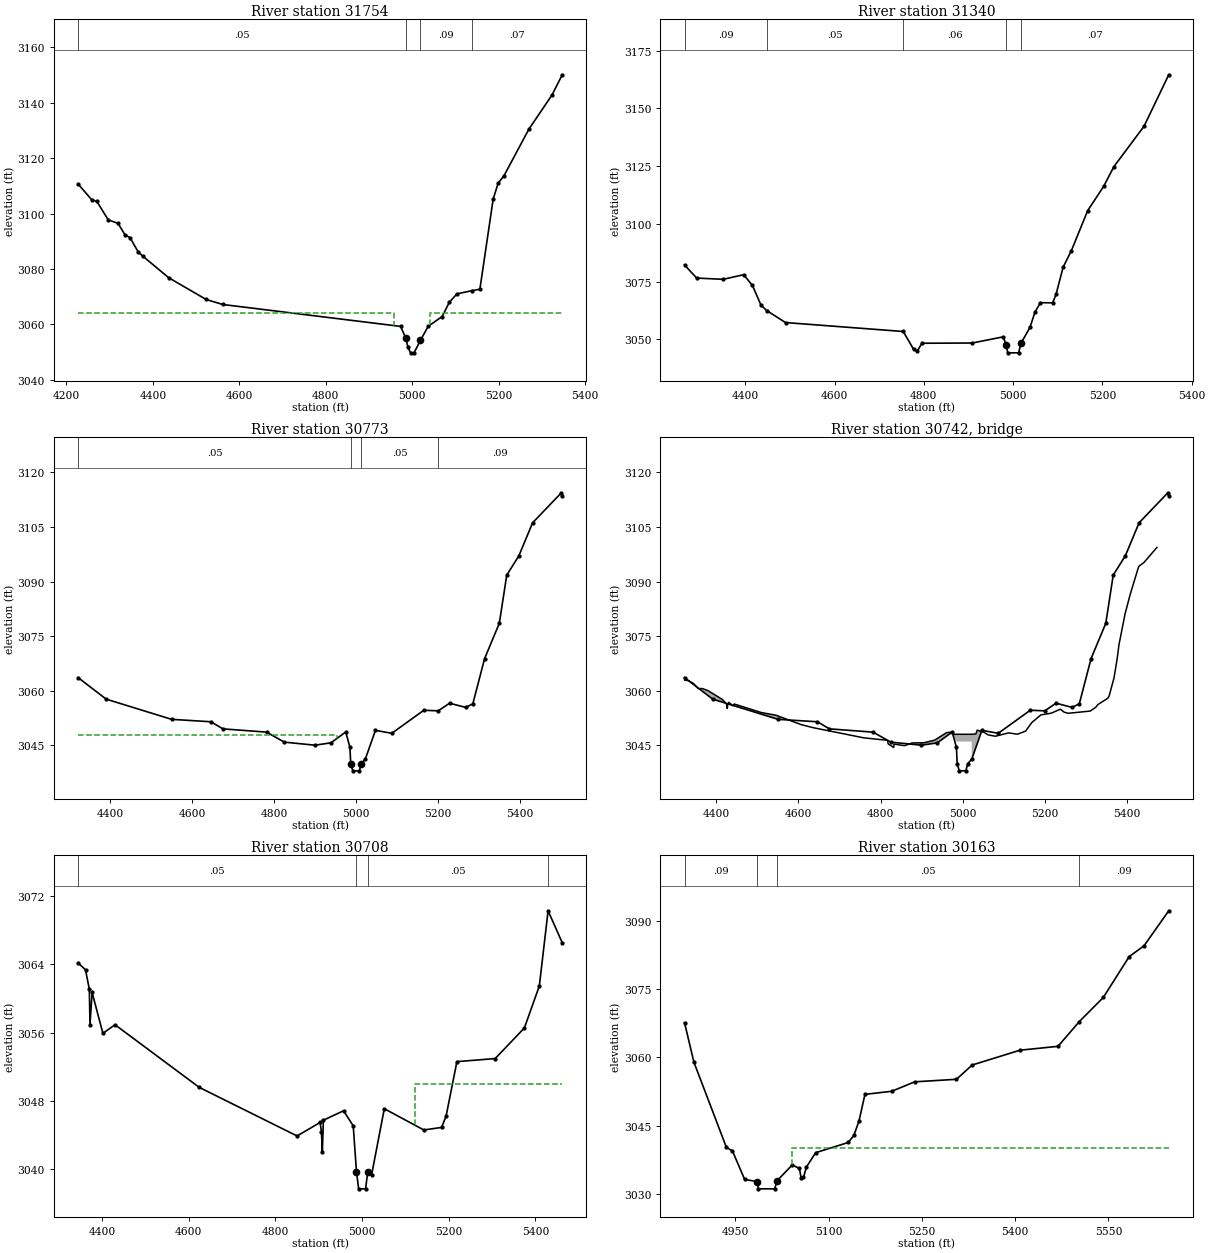
Type RM Length L Ch R = 1 ,31754   ,414,414,414
BEGIN DESCRIPTION:
Little_Rock_Crk_92.25
END DESCRIPTION:
XS GIS Cut Line= 4
      1074831.86       853693.19      1074253.68       854163.35
      1074200.52        854215.5      1073987.88       854427.13
#Sta/Elev= 30
  4227.1 3110.71    4259 3104.94  4270.6 3104.38  4296.9 3097.75  4319.6 3096.48
    4336 3092.24  4347.3 3091.34  4366.2 3086.15  4377.3 3084.58  4436.7 3076.86
  4523.3 3069.01  4561.7  3067.2    4973 3059.29    4985 3055.03    4990 3051.75
    4996 3049.75    5004 3049.75 5018.96 3054.29  5036.8 3059.33    5069 3062.86
  5085.6 3067.97  5103.1 3071.02  5137.1 3072.16  5156.3 3072.72    5187 3105.21
  5198.6 3111.03  5211.8  3113.6  5269.5 3130.45  5323.1 3142.82  5346.8 3150.11
#Mann= 4 ,-1 , 0
  4227.1     .05       0    4985     .05       0 5018.96     .09       0
  5137.1     .07       0
#XS Ineff= 2 , 0
       0    4958    3064    5042       0    3064
Permanent Ineff=
       F       F
Bank Sta=4985,5018.96
Exp/Cntr=0.5,0.3

Type RM Length L Ch R = 1 ,31340   ,567,567,567
BEGIN DESCRIPTION:
Little_Rock_Crk_92
END DESCRIPTION:
XS GIS Cut Line= 2
      1074241.76       853355.62      1073692.72       854290.95
#Sta/Elev= 30
  4263.9 3082.16  4291.1 3076.49  4350.4 3075.95  4396.4 3077.95    4416 3073.27
  4435.2 3064.74  4448.1 3062.38  4490.1 3057.21  4753.8 3053.33    4777  3045.6
  4785.3 3044.82  4795.5 3048.24  4908.6 3048.34  4977.7 3051.01 4984.37 3047.62
  4987.8 3044.08  5012.2 3044.08  5017.7 3048.29  5037.6 3055.08  5048.8 3061.67
    5061 3065.83  5088.5 3065.74  5096.2 3069.49    5112 3081.26  5130.5 3088.41
  5166.8 3105.67  5202.7 3116.24  5225.8 3124.83  5293.1 3142.28  5348.5 3164.61
#Mann= 5 ,-1 , 0
  4263.9     .09       0  4448.1     .05       0  4753.8     .06       0
 4984.37     .05       0  5017.7     .07       0
Bank Sta=4984.37,5017.7
Exp/Cntr=0.5,0.3

Type RM Length L Ch R = 1 ,30773   ,65,65,65
BEGIN DESCRIPTION:
Little_Rock_Crk_91
END DESCRIPTION:
XS GIS Cut Line= 4
      1073581.94       853029.65      1073321.47        853945.9
      1073367.05       854167.25      1073364.88       854167.25
#Sta/Elev= 30
  4322.1 3063.59  4390.7 3057.66  4550.1 3052.11    4646 3051.44  4675.4 3049.49
    4782 3048.59    4825 3045.84  4899.9    3045  4938.8 3045.65  4974.9 3048.63
  4985.1 3044.41    4987 3039.95    4992 3037.95    5008 3037.95    5013 3039.95
  5022.6 3041.18  5047.3 3049.08  5087.2 3048.27  5165.3 3054.61  5200.4 3054.44
  5228.1 3056.54  5267.3 3055.39  5284.8 3056.37  5313.4 3068.77  5349.4 3078.51
  5367.5 3091.75    5397 3097.05  5430.6 3106.14  5500.7 3114.39  5502.9 3113.53
#Mann= 4 ,-1 , 0
  4322.1     .05       0    4987     .05       0    5013     .05       0
  5200.4     .09       0
#XS Ineff= 2 , 0
       0    4953 3047.69    5047       0 3048.77
Permanent Ineff=
       F       F
Bank Sta=4987,5013
Exp/Cntr=0.5,0.3

Type RM Length L Ch R = 3 ,30742   ,,,
BEGIN DESCRIPTION:
Little_Rock_Crk_90
Structure ID: Roan Mountain Road side street 4
Approximate Survey Structure
END DESCRIPTION:
Bridge Culvert--1,0,-1,-1, 0
Deck Dist Width WeirC Skew NumUp NumDn MinLoCord MaxHiCord MaxSubmerge Is_Ogee
24.5,13,3,0, 60, 60, , , , 0, 1,1,,
  4322.6  4331.2    4344  4355.3    4366  4379.5  4414.8  4424.7  4426.3  4427.5
    4430  4439.8  4443.4  4509.1  4545.3  4606.9  4635.5  4759.3  4817.2  4818.7
  4832.4  4832.9  4858.4  4877.4  4906.1  4932.2  4960.9  4970.7  4977.5  4977.5
  5022.5  5022.5  5032.6  5035.7  5052.1  5062.3  5080.3  5112.1  5133.7  5153.7
  5169.2  5191.1  5216.2  5238.5    5248  5257.5  5311.3  5324.9  5330.5  5353.9
  5357.4  5369.6  5377.1  5381.5  5396.2  5408.7  5428.7  5430.1  5442.6    5474
 3062.89 3062.75 3061.96 3060.57 3060.56 3059.99 3057.54 3056.26 3055.08 3056.15
 3056.78 3055.82 3056.32 3053.98 3053.23 3050.64 3049.82 3047.02 3046.34 3045.35
 3044.37 3045.31 3044.87 3045.62 3045.67  3046.4 3048.44 3048.58    3048    3048
    3048    3048  3048.1 3049.13 3048.58 3047.84 3047.46 3048.38 3048.02 3048.86
 3051.25 3053.33 3053.79 3054.89 3054.08 3053.77 3054.38 3055.42  3056.2 3057.87
 3058.47 3063.57 3068.74 3072.59 3081.01 3086.38  3093.8 3094.17 3095.24 3099.36
 3017.95 3017.95 3017.95 3017.95 3017.95 3017.95 3017.95 3017.95 3017.95 3017.95
 3017.95 3017.95 3017.95 3017.95 3017.95 3017.95 3017.95 3017.95 3017.95 3017.95
 3017.95 3017.95 3017.95 3017.95 3017.95 3017.95 3017.95 3017.95 3017.95    3046
    3046 3017.95 3017.95 3017.95 3017.95 3017.95 3017.95 3017.95 3017.95 3017.95
 3017.95 3017.95 3017.95 3017.95 3017.95 3017.95 3017.95 3017.95 3017.95 3017.95
 3017.95 3017.95 3017.95 3017.95 3017.95 3017.95 3017.95 3017.95 3017.95 3017.95
  4322.6  4331.2    4344  4355.3    4366  4379.5  4414.8  4424.7  4426.3  4427.5
    4430  4439.8  4443.4  4509.1  4545.3  4606.9  4635.5  4759.3  4817.2  4818.7
  4832.4  4832.9  4858.4  4877.4  4906.1  4932.2  4960.9  4970.7  4977.5  4977.5
  5022.5  5022.5  5032.6  5035.7  5052.1  5062.3  5080.3  5112.1  5133.7  5153.7
  5169.2  5191.1  5216.2  5238.5    5248  5257.5  5311.3  5324.9  5330.5  5353.9
  5357.4  5369.6  5377.1  5381.5  5396.2  5408.7  5428.7  5430.1  5442.6    5474
 3062.89 3062.75 3061.96 3060.57 3060.56 3059.99 3057.54 3056.26 3055.08 3056.15
 3056.78 3055.82 3056.32 3053.98 3053.23 3050.64 3049.82 3047.02 3046.34 3045.35
 3044.37 3045.31 3044.87 3045.62 3045.67  3046.4 3048.44 3048.58    3048    3048
    3048    3048  3048.1 3049.13 3048.58 3047.84 3047.46 3048.38 3048.02 3048.86
 3051.25 3053.33 3053.79 3054.89 3054.08 3053.77 3054.38 3055.42  3056.2 3057.87
 3058.47 3063.57 3068.74 3072.59 3081.01 3086.38  3093.8 3094.17 3095.24 3099.36
 3017.95 3017.95 3017.95 3017.95 3017.95 3017.95 3017.95 3017.95 3017.95 3017.95
 3017.95 3017.95 3017.95 3017.95 3017.95 3017.95 3017.95 3017.95 3017.95 3017.95
 3017.95 3017.95 3017.95 3017.95 3017.95 3017.95 3017.95 3017.95 3017.95    3046
    3046 3017.95 3017.95 3017.95 3017.95 3017.95 3017.95 3017.95 3017.95 3017.95
 3017.95 3017.95 3017.95 3017.95 3017.95 3017.95 3017.95 3017.95 3017.95 3017.95
 3017.95 3017.95 3017.95 3017.95 3017.95 3017.95 3017.95 3017.95 3017.95 3017.95
BR Coef= 1 , 1 , 0 ,1.25, 0 ,,,0.8,0,2,0,
WSPro=,,,, 1 ,,,, 0 ,,,, 0 ,,,,-1 ,-1 ,-1 , 0 , 0 , 0 , 0 , 0
BC Design=,, 0 ,, 0 ,,,,,,
BC HTab HWMax=3114.39

Type RM Length L Ch R = 1 ,30708   ,545,545,545
BEGIN DESCRIPTION:
Little_Rock_Crk_89
END DESCRIPTION:
XS GIS Cut Line= 3
      1073514.44       853036.18      1073255.61       853936.74
      1073283.83       854114.69
#Sta/Elev= 30
  4344.6 3064.14  4361.8 3063.34  4370.6 3061.06  4372.1 3056.92    4377 3060.69
  4401.9  3055.9  4429.9 3056.91  4624.1 3049.58    4850 3043.89    4903 3045.47
  4906.2 3044.38  4908.2 3042.04  4910.6 3045.73  4957.1 3046.84  4979.5 3045.07
    4987  3039.7    4992  3037.7    5008  3037.7    5013  3039.7  5021.8 3039.31
  5051.2 3047.08  5142.4 3044.59  5183.3 3044.89  5193.7  3046.2  5218.7 3052.59
    5307 3052.95  5374.4 3056.53  5408.9 3061.45  5429.1 3070.25  5461.8  3066.5
#Mann= 4 ,-1 , 0
  4344.6     .05       0    4987     .05       0    5013     .05       0
  5429.1     .09       0
#XS Ineff= 3 ,-1
  4344.6    4950    3045    5050  5122.2    3045  5122.2  5461.8    3050
Permanent Ineff=
       F       F       F
Bank Sta=4987,5013
Exp/Cntr=0.5,0.3

Type RM Length L Ch R = 1 ,30163   ,482,482,482
BEGIN DESCRIPTION:
Little_Rock_Crk_88
END DESCRIPTION:
XS GIS Cut Line= 2
      1072792.61        853746.7       1073207.1       854406.42
#Sta/Elev= 30
    4868 3067.65  4883.1 3058.94  4935.4 3040.17  4945.1  3039.4  4964.7 3033.12
  4985.2 3032.64  4986.8 3031.05  5013.2 3031.05  5016.5 3032.77  5041.2  3036.3
  5052.9 3035.55  5055.7 3033.34  5059.4 3033.55    5064 3035.83    5079 3039.02
  5131.4 3041.26  5140.5 3042.83  5148.7    3046  5158.3 3051.86  5201.4 3052.54
  5238.3 3054.62  5305.5 3055.18  5330.9 3058.33  5407.8 3061.59  5468.9 3062.44
  5503.2 3067.89  5541.8  3073.2  5583.5 3082.21  5607.4 3084.59  5647.1  3092.3
#Mann= 4 ,-1 , 0
    4868     .09       0  4985.2     .05       0  5016.5     .05       0
  5503.2     .09       0
#XS Ineff= 2 , 0
       0                  5041.2       0    3040
Permanent Ineff=
       F       F
Bank Sta=4985.2,5016.5
Exp/Cntr=0.3,0.1

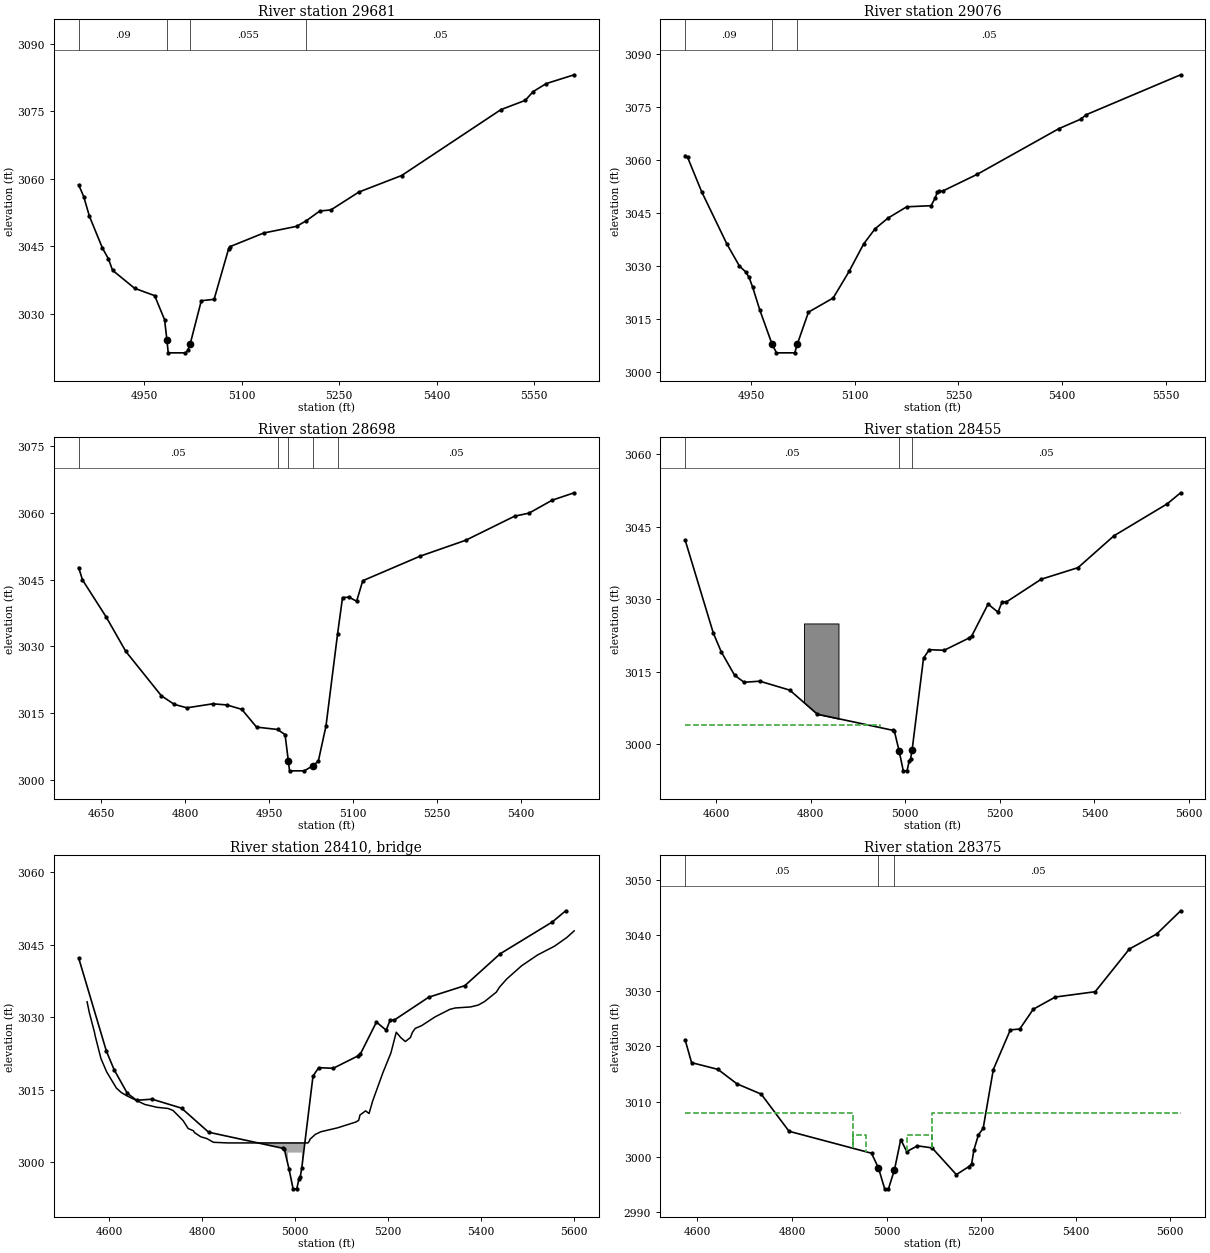
Type RM Length L Ch R = 1 ,29681   ,605,605,605
BEGIN DESCRIPTION:
Little_Rock_Crk_87
END DESCRIPTION:
XS GIS Cut Line= 2
      1072391.13       853698.95      1072352.07       854460.67
#Sta/Elev= 30
  4848.9 3058.68  4856.7 3056.08  4865.5 3051.69  4885.5 3044.65  4894.8 3042.24
  4901.1 3039.71  4935.1 3035.71  4965.9 3034.08  4981.2 3028.73 4984.86 3024.14
  4986.8 3021.39  5013.2 3021.39  5016.9 3021.92  5020.7 3023.42  5037.7 3032.95
  5057.4 3033.27  5079.8  3044.5  5082.3 3044.98  5133.8 3047.98  5184.4 3049.46
  5199.4 3050.71  5220.1 3052.86  5237.2  3053.1  5280.1 3057.06  5346.1 3060.74
  5498.9 3075.36  5536.3 3077.41  5548.4 3079.35  5568.5 3081.13  5611.6 3083.09
#Mann= 4 ,-1 , 0
  4848.9     .09       0 4984.86     .05       0  5020.7    .055       0
  5199.4     .05       0
Bank Sta=4984.86,5020.7
Exp/Cntr=0.3,0.1

Type RM Length L Ch R = 1 ,29076   ,378,378,378
BEGIN DESCRIPTION:
Little_Rock_Crk_86
END DESCRIPTION:
XS GIS Cut Line= 2
      1071787.83       853729.34      1071807.37       854445.48
#Sta/Elev= 30
  4854.7 3061.21  4858.3 3060.71  4878.6 3051.01  4915.2 3036.21  4933.3    3030
  4942.1  3028.4  4947.2 3026.83  4952.5 3023.98  4962.6 3017.68  4980.1 3008.14
  4986.8 3005.52  5013.2 3005.52 5017.15 3008.09  5033.1 3017.01  5068.8    3021
  5091.8 3028.49  5112.8 3036.23  5129.3 3040.52  5147.9 3043.53  5175.1 3046.74
  5210.4 3047.05  5216.3 3049.24  5219.4 3050.85  5221.2 3051.08    5227 3051.17
    5277  3055.9  5395.3 3068.81  5426.7 3071.47  5434.8 3072.74  5571.2    3084
#Mann= 3 , 0 , 0
  4854.7     .09       0  4980.1     .05       0 5017.15     .05       0
Bank Sta=4980.1,5017.15
Exp/Cntr=0.3,0.1

Type RM Length L Ch R = 1 ,28698   ,243,243,243
BEGIN DESCRIPTION:
little_rock_crk_a5
END DESCRIPTION:
XS GIS Cut Line= 3
      1071603.01       853654.74      1071419.58       853866.93
      1071466.34       854471.15
#Sta/Elev= 30
  4609.5 3047.72  4616.4 3044.93  4658.7 3036.62  4693.9 3028.86  4757.5  3018.9
  4780.7 3016.96  4803.3 3016.19  4849.4 3017.09  4874.6 3016.84  4901.3 3015.85
  4927.8 3011.86  4965.4 3011.32  4978.8 3010.17 4984.61 3004.28  4986.8 3002.03
  5013.2 3002.03  5028.4 3003.16  5038.3 3004.21    5052 3012.09  5072.7 3032.77
  5081.6 3040.97  5093.3 3041.05  5106.8 3040.14  5117.8 3044.75  5220.3 3050.26
    5302 3053.84  5389.4 3059.25  5415.3 3059.94  5456.7 3062.85    5496 3064.51
#Mann= 5 ,-1 , 0
  4609.5     .05       0  4965.4     .09       0 4984.61     .05       0
  5028.4     .09       0  5072.7     .05       0
Bank Sta=4984.61,5028.4
Exp/Cntr=0.5,0.3

Type RM Length L Ch R = 1 ,28455   ,80,80,80
BEGIN DESCRIPTION:
Little_Rock_Crk_85
END DESCRIPTION:
XS GIS Cut Line= 6
      1071495.71       853621.91       1071263.5       853860.63
      1071185.38       853977.82      1071128.95       854097.17
      1071165.85       854251.25      1071259.16       854518.18
#Sta/Elev= 30
  4534.7 3042.29  4594.4    3023  4611.2 3019.12  4639.3 3014.29  4659.3 3012.83
  4692.8 3013.05    4756  3011.2  4814.3 3006.22  4975.3 3002.86  4977.1 3002.74
  4987.2 2998.62    4996  2994.5    5004  2994.5  5008.5 2996.53  5011.4 2996.99
  5014.6 2998.74  5038.8 3017.83    5051 3019.57  5082.4 3019.45    5135 3021.98
  5140.6 3022.38  5175.3 3029.01  5196.2 3027.33  5204.9 3029.45  5213.7 3029.43
  5287.6 3034.15  5365.5 3036.55  5441.3 3043.13  5553.8 3049.74  5582.4 3052.04
#Mann= 3 ,-1 , 0
  4534.7     .05       0  4987.2     .05       0  5014.6     .05       0
#XS Ineff= 2 , 0
       0    4946    3004    5054       0 3006.24
Permanent Ineff=
       F       F
#Block Obstruct= 1 ,-1
    4786    4859    3025
Bank Sta=4987.2,5014.6
Exp/Cntr=0.5,0.3

Type RM Length L Ch R = 3 ,28410   ,,,
BEGIN DESCRIPTION:
Little_Rock_Crk_84
Structure ID: Roan Mountain Road side street 3
Approximate Survey Structure
END DESCRIPTION:
Bridge Culvert--1,0,-1,-1, 0
Deck Dist Width WeirC Skew NumUp NumDn MinLoCord MaxHiCord MaxSubmerge Is_Ogee
39,12,3,0, 60, 60, , , , 0, 1,1,,
  4552.9  4557.5  4568.6  4570.4  4582.7    4595    4616  4626.6  4637.6  4676.8
  4703.3    4727  4737.9  4759.6  4770.3  4781.3  4784.1  4797.1  4810.8  4824.7
    4856    4985    4985    5015    5015  5028.1  5031.7  5032.2  5043.7  5055.6
  5091.5  5130.8  5137.1  5139.9    5152  5159.4  5167.2  5189.1  5206.4  5217.9
  5227.7  5237.5  5248.4  5252.7  5258.7  5272.3  5301.3  5333.3    5345  5377.6
  5394.3  5407.8  5433.1  5440.1  5455.6  5487.3  5521.6  5558.2  5584.4  5600.6
 3033.21 3031.04 3026.97 3026.11 3021.46  3018.7 3015.34 3014.42 3013.79 3011.97
 3011.37 3011.13 3010.71  3008.6 3006.98 3006.54 3006.13 3005.29 3004.89 3004.13
    3004    3004    3004    3004    3004    3004 3004.51 3004.75 3005.76 3006.31
 3007.12 3008.32 3008.68 3009.78 3010.63 3010.09 3012.69 3018.51 3022.62 3026.91
 3025.79 3024.98 3025.82 3026.89  3027.7 3028.26 3030.08 3031.65 3031.93 3032.14
 3032.53 3033.25  3035.2 3036.25 3037.93 3040.64 3042.88 3044.71 3046.48 3047.88
  2974.5  2974.5  2974.5  2974.5  2974.5  2974.5  2974.5  2974.5  2974.5  2974.5
  2974.5  2974.5  2974.5  2974.5  2974.5  2974.5  2974.5  2974.5  2974.5  2974.5
  2974.5  2974.5    3002    3002  2974.5  2974.5  2974.5  2974.5  2974.5  2974.5
  2974.5  2974.5  2974.5  2974.5  2974.5  2974.5  2974.5  2974.5  2974.5  2974.5
  2974.5  2974.5  2974.5  2974.5  2974.5  2974.5  2974.5  2974.5  2974.5  2974.5
  2974.5  2974.5  2974.5  2974.5  2974.5  2974.5  2974.5  2974.5  2974.5  2974.5
  4552.9  4557.5  4568.6  4570.4  4582.7    4595    4616  4626.6  4637.6  4676.8
  4703.3    4727  4737.9  4759.6  4770.3  4781.3  4784.1  4797.1  4810.8  4824.7
    4856    4985    4985    5015    5015  5028.1  5031.7  5032.2  5043.7  5055.6
  5091.5  5130.8  5137.1  5139.9    5152  5159.4  5167.2  5189.1  5206.4  5217.9
  5227.7  5237.5  5248.4  5252.7  5258.7  5272.3  5301.3  5333.3    5345  5377.6
  5394.3  5407.8  5433.1  5440.1  5455.6  5487.3  5521.6  5558.2  5584.4  5600.6
 3033.21 3031.04 3026.97 3026.11 3021.46  3018.7 3015.34 3014.42 3013.79 3011.97
 3011.37 3011.13 3010.71  3008.6 3006.98 3006.54 3006.13 3005.29 3004.89 3004.13
    3004    3004    3004    3004    3004    3004 3004.51 3004.75 3005.76 3006.31
 3007.12 3008.32 3008.68 3009.78 3010.63 3010.09 3012.69 3018.51 3022.62 3026.91
 3025.79 3024.98 3025.82 3026.89  3027.7 3028.26 3030.08 3031.65 3031.93 3032.14
 3032.53 3033.25  3035.2 3036.25 3037.93 3040.64 3042.88 3044.71 3046.48 3047.88
  2974.5  2974.5  2974.5  2974.5  2974.5  2974.5  2974.5  2974.5  2974.5  2974.5
  2974.5  2974.5  2974.5  2974.5  2974.5  2974.5  2974.5  2974.5  2974.5  2974.5
  2974.5  2974.5    3002    3002  2974.5  2974.5  2974.5  2974.5  2974.5  2974.5
  2974.5  2974.5  2974.5  2974.5  2974.5  2974.5  2974.5  2974.5  2974.5  2974.5
  2974.5  2974.5  2974.5  2974.5  2974.5  2974.5  2974.5  2974.5  2974.5  2974.5
  2974.5  2974.5  2974.5  2974.5  2974.5  2974.5  2974.5  2974.5  2974.5  2974.5
BR Coef= 1 , 1 , 0 ,1.25, 0 ,,,0.8,0,2,0,
WSPro=,,,, 1 ,,,, 0 ,,,, 0 ,,,,-1 ,-1 ,-1 , 0 , 0 , 0 , 0 , 0
BC Design=,, 0 ,, 0 ,,,,,,
BC HTab HWMax=3052.04

Type RM Length L Ch R = 1 ,28375   ,661,661,661
BEGIN DESCRIPTION:
Little_Rock_Crk_83
END DESCRIPTION:
XS GIS Cut Line= 6
      1071401.55       853621.91      1071169.34       853860.63
      1071091.22       853977.82       1071034.8       854097.17
      1071071.69       854251.25        1071165.       854518.18
#Sta/Elev= 30
    4574 3021.16  4587.7 3017.03  4643.5 3015.81  4683.7  3013.2  4734.9 3011.35
  4793.8 3004.64  4968.2 3000.68  4982.9 2998.01    4996 2994.25    5004 2994.25
  5016.7 2997.69    5030 3003.15  5042.6 3000.98  5065.4 3002.01  5096.3 3001.64
  5147.5 2996.82  5173.6 2998.24  5179.9 2998.77  5184.6 3001.24  5194.3 3004.01
  5204.2 3005.15  5225.7 3015.78  5261.7 3022.94  5281.6  3023.1  5310.2 3026.67
  5356.7 3028.87  5441.1 3029.83  5513.4 3037.54  5571.1 3040.24  5621.8 3044.44
#Mann= 3 , 0 , 0
    4574     .05       0  4982.9     .05       0  5016.7     .05       0
#XS Ineff= 4 ,-1
    4574    4930    3008    4930    4956    3004    5044    5096    3004
    5096  5621.8    3008
Permanent Ineff=
       F       F       F       F
Bank Sta=4982.9,5016.7
Exp/Cntr=0.5,0.3

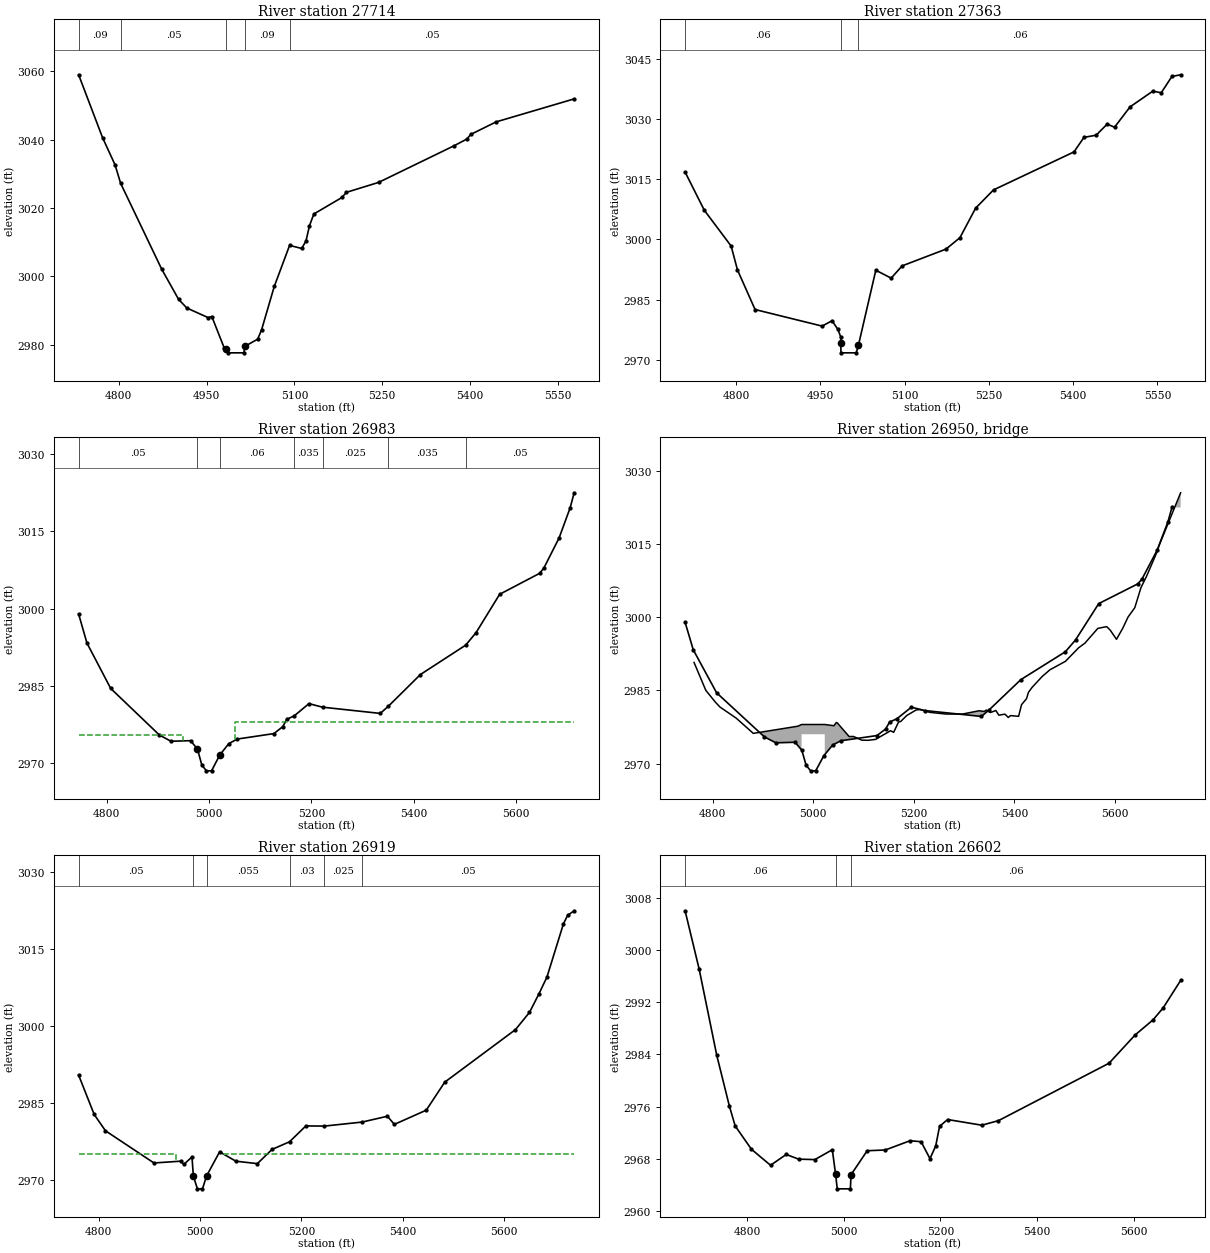
Type RM Length L Ch R = 1 ,27714   ,351,351,351
BEGIN DESCRIPTION:
Little_Rock_Crk_82
END DESCRIPTION:
XS GIS Cut Line= 2
      1070585.58       854164.45      1071217.09       854728.68
#Sta/Elev= 30
  4731.3 3059.02  4772.1 3040.65  4793.6 3032.62  4803.1 3027.23  4873.3 3002.09
  4902.1 2993.28  4916.2 2990.73  4952.5 2987.93  4958.9 2988.23  4979.9 2979.13
  4983.7 2978.85  4986.4 2977.61  5013.6 2977.61  5015.7 2979.55  5037.2  2981.6
  5043.9 2984.34  5065.6 2997.04  5091.8 3009.07  5112.4 3008.17  5119.8 3010.35
  5125.8 3014.84  5133.3 3018.27  5181.2 3023.09  5188.7 3024.59  5243.9 3027.51
  5373.5 3038.29  5394.9 3040.22  5401.3 3041.55  5444.8 3045.23  5578.1 3051.96
#Mann= 5 ,-1 , 0
  4731.3     .09       0  4803.1     .05       0  4983.7     .05       0
  5015.7     .09       0  5091.8     .05       0
Bank Sta=4983.7,5015.7
Exp/Cntr=0.3,0.1

Type RM Length L Ch R = 1 ,27363   ,380,380,380
BEGIN DESCRIPTION:
Little_Rock_Crk_81
END DESCRIPTION:
XS GIS Cut Line= 2
      1070420.65        854552.9      1071217.09       854932.68
#Sta/Elev= 30
  4708.9 3016.77  4743.1 3007.25  4790.9 2998.33  4802.1  2992.4  4833.5 2982.51
    4953 2978.38  4970.6 2979.73    4981 2977.55    4986  2975.7 4986.19  2974.2
  4986.4 2971.72  5013.6 2971.72  5017.6 2973.64  5048.5 2992.31  5075.8 2990.33
  5095.4 2993.39  5173.5 2997.57  5198.4 3000.43  5226.2 3007.77  5258.1 3012.32
  5401.4 3021.79  5419.2 3025.42  5440.8 3025.95  5460.5 3028.72  5473.6 3027.94
  5501.2 3033.01  5541.6 3036.92  5556.8 3036.54  5575.8  3040.6  5591.3 3041.01
#Mann= 3 , 0 , 0
  4708.9     .06       0 4986.19     .05       0  5017.6     .06       0
Bank Sta=4986.19,5017.6
Exp/Cntr=0.5,0.3

Type RM Length L Ch R = 1 ,26983   ,64,64,64
BEGIN DESCRIPTION:
Little_Rock_Crk_80
END DESCRIPTION:
XS GIS Cut Line= 2
      1070278.64       854676.95      1070736.11       855529.38
#Sta/Elev= 30
  4745.5 2998.95  4761.7 2993.32  4808.1  2984.5  4903.1 2975.46  4925.8 2974.24
    4964 2974.36  4977.5 2972.72    4986 2969.64    4995  2968.5    5005  2968.5
  5021.2  2971.6  5038.7 2973.78  5055.1 2974.67  5126.7 2975.73  5144.1 2977.08
  5151.9 2978.51  5166.4 2979.17  5195.2 2981.55  5221.7 2980.86  5334.4 2979.65
  5350.2 2981.04  5412.8  2987.2  5501.1  2992.9  5521.4 2995.33  5567.5 3002.78
  5645.6 3006.85  5653.8 3007.87  5683.6 3013.73  5705.1 3019.56    5713 3022.49
#Mann= 7 ,-1 , 0
  4745.5     .05       0  4977.5     .05       0  5021.2     .06       0
  5166.4    .035       0  5221.7    .025       0  5350.2    .035       0
  5501.1     .05       0
#XS Ineff= 2 , 0
       0    4950 2975.45    5050       0 2978.03
Permanent Ineff=
       F       F
Bank Sta=4977.5,5021.2
Exp/Cntr=0.5,0.3

Type RM Length L Ch R = 3 ,26950   ,,,
BEGIN DESCRIPTION:
Little_Rock_Crk_79
Structure ID: Roan Mountain Road side street 1
Approximate Survey Structure
END DESCRIPTION:
Bridge Culvert--1,0,-1,-1, 0
Deck Dist Width WeirC Skew NumUp NumDn MinLoCord MaxHiCord MaxSubmerge Is_Ogee
27,12,3,0, 60, 60, , , , 0, 1,1,,
  4763.3  4786.6  4805.5  4814.8  4847.2    4881  4969.6    4977    4977    5023
    5023  5041.4    5046  5047.9  5071.4  5080.3  5096.6  5109.4  5124.1  5153.8
    5160  5169.8  5173.8    5186  5204.3  5212.2  5231.9    5264  5296.7  5330.1
  5340.1  5344.1  5352.5  5363.1    5369  5381.2  5387.8  5392.1  5408.3  5414.1
    5424  5427.8    5435    5455  5470.6  5501.4  5527.6  5540.1  5565.7  5583.3
  5590.3  5602.8  5615.1  5625.8  5639.2  5651.5  5662.6  5683.1  5687.7  5730.3
 2990.72 2985.01  2982.6 2981.58 2979.29 2976.18 2977.65    2978    2978    2978
    2978 2977.75 2978.41 2978.34 2975.54 2975.54 2974.79 2974.76 2974.95 2976.72
  2976.4 2978.53  2978.6 2979.84 2980.96 2981.07 2980.49 2980.14 2980.14 2980.82
 2980.67 2980.96 2980.46 2980.87 2979.91 2980.12 2979.44 2979.82 2979.68 2982.06
 2983.28 2984.58  2985.6 2987.83 2989.22 2990.95 2993.73 2994.68  2997.7 2998.06
 2997.35 2995.46  2997.7 3000.02 3001.95 3006.07 3008.39 3013.31 3014.75  3025.5
  2948.5  2948.5  2948.5  2948.5  2948.5  2948.5  2948.5  2948.5    2976    2976
  2948.5  2948.5  2948.5  2948.5  2948.5  2948.5  2948.5  2948.5  2948.5  2948.5
  2948.5  2948.5  2948.5  2948.5  2948.5  2948.5  2948.5  2948.5  2948.5  2948.5
  2948.5  2948.5  2948.5  2948.5  2948.5  2948.5  2948.5  2948.5  2948.5  2948.5
  2948.5  2948.5  2948.5  2948.5  2948.5  2948.5  2948.5  2948.5  2948.5  2948.5
  2948.5  2948.5  2948.5  2948.5  2948.5  2948.5  2948.5  2948.5  2948.5  2948.5
  4763.3  4786.6  4805.5  4814.8  4847.2    4881  4969.6    4977    4977    5023
    5023  5041.4    5046  5047.9  5071.4  5080.3  5096.6  5109.4  5124.1  5153.8
    5160  5169.8  5173.8    5186  5204.3  5212.2  5231.9    5264  5296.7  5330.1
  5340.1  5344.1  5352.5  5363.1    5369  5381.2  5387.8  5392.1  5408.3  5414.1
    5424  5427.8    5435    5455  5470.6  5501.4  5527.6  5540.1  5565.7  5583.3
  5590.3  5602.8  5615.1  5625.8  5639.2  5651.5  5662.6  5683.1  5687.7  5730.3
 2990.72 2985.01  2982.6 2981.58 2979.29 2976.18 2977.65    2978    2978    2978
    2978 2977.75 2978.41 2978.34 2975.54 2975.54 2974.79 2974.76 2974.95 2976.72
  2976.4 2978.53  2978.6 2979.84 2980.96 2981.07 2980.49 2980.14 2980.14 2980.82
 2980.67 2980.96 2980.46 2980.87 2979.91 2980.12 2979.44 2979.82 2979.68 2982.06
 2983.28 2984.58  2985.6 2987.83 2989.22 2990.95 2993.73 2994.68  2997.7 2998.06
 2997.35 2995.46  2997.7 3000.02 3001.95 3006.07 3008.39 3013.31 3014.75  3025.5
  2948.5  2948.5  2948.5  2948.5  2948.5  2948.5  2948.5  2948.5    2976    2976
  2948.5  2948.5  2948.5  2948.5  2948.5  2948.5  2948.5  2948.5  2948.5  2948.5
  2948.5  2948.5  2948.5  2948.5  2948.5  2948.5  2948.5  2948.5  2948.5  2948.5
  2948.5  2948.5  2948.5  2948.5  2948.5  2948.5  2948.5  2948.5  2948.5  2948.5
  2948.5  2948.5  2948.5  2948.5  2948.5  2948.5  2948.5  2948.5  2948.5  2948.5
  2948.5  2948.5  2948.5  2948.5  2948.5  2948.5  2948.5  2948.5  2948.5  2948.5
BR Coef= 1 , 1 , 0 ,1.25, 0 ,,,0.8,0,2,0,
WSPro=,,,, 1 ,,,, 0 ,,,, 0 ,,,,-1 ,-1 ,-1 , 0 , 0 , 0 , 0 , 0
BC Design=,, 0 ,, 0 ,,,,,,
BC HTab HWMax=3022.49

Type RM Length L Ch R = 1 ,26919   ,317,317,317
BEGIN DESCRIPTION:
Little_Rock_Crk_78
END DESCRIPTION:
XS GIS Cut Line= 2
      1070225.69       854709.93      1070686.63       855571.91
#Sta/Elev= 30
  4760.7 2990.41  4791.4 2982.74  4813.7 2979.56  4909.3 2973.29  4961.7 2973.64
  4968.2 2973.02  4984.3 2974.46    4987 2970.75    4995 2968.25    5005 2968.25
    5013 2970.75  5038.8 2975.46  5070.8 2973.64  5113.2 2973.16  5142.2 2975.93
  5176.7 2977.42  5208.9 2980.51  5245.5 2980.48  5319.7 2981.26  5369.8  2982.4
  5383.5 2980.81  5446.4 2983.58  5482.9 2989.04  5622.4 2999.28    5650 3002.63
  5668.4 3006.19  5684.5 3009.52    5717 3019.89  5725.3 3021.55  5738.2 3022.44
#Mann= 6 ,-1 , 0
  4760.7     .05       0    4987     .05       0    5013    .055       0
  5176.7     .03       0  5245.5    .025       0  5319.7     .05       0
#XS Ineff= 2 , 0
       0    4952    2975    5048       0    2975
Permanent Ineff=
       F       F
Bank Sta=4987,5013
Exp/Cntr=0.5,0.3

Type RM Length L Ch R = 1 ,26602   ,365,365,365
BEGIN DESCRIPTION:
little_rock_crk_a6
END DESCRIPTION:
XS GIS Cut Line= 4
      1070031.33       854690.53      1070024.14       854974.66
      1070049.31       855060.97      1070081.68       855711.94
#Sta/Elev= 30
  4671.4 3005.99  4700.6 2997.02    4737 2983.83    4763 2976.09  4775.1 2973.02
  4808.8 2969.45  4848.3    2967  4880.8 2968.66  4906.4 2967.94    4940 2967.87
  4976.2 2969.38 4982.92 2965.65  4986.4 2963.39  5013.6 2963.39  5014.9 2965.55
  5048.4 2969.23  5085.8 2969.34  5137.1 2970.76    5160 2970.61  5178.4 2968.01
  5190.3 2969.98  5198.2 2972.96  5214.8 2974.01  5285.7 2973.14  5320.2 2973.84
    5549 2982.63  5602.9 2986.95  5640.3 2989.29  5661.3 2991.13  5697.3 2995.32
#Mann= 3 , 0 , 0
  4671.4     .06       0 4982.92     .05       0  5014.9     .06       0
Bank Sta=4982.92,5014.9
Exp/Cntr=0.3,0.1