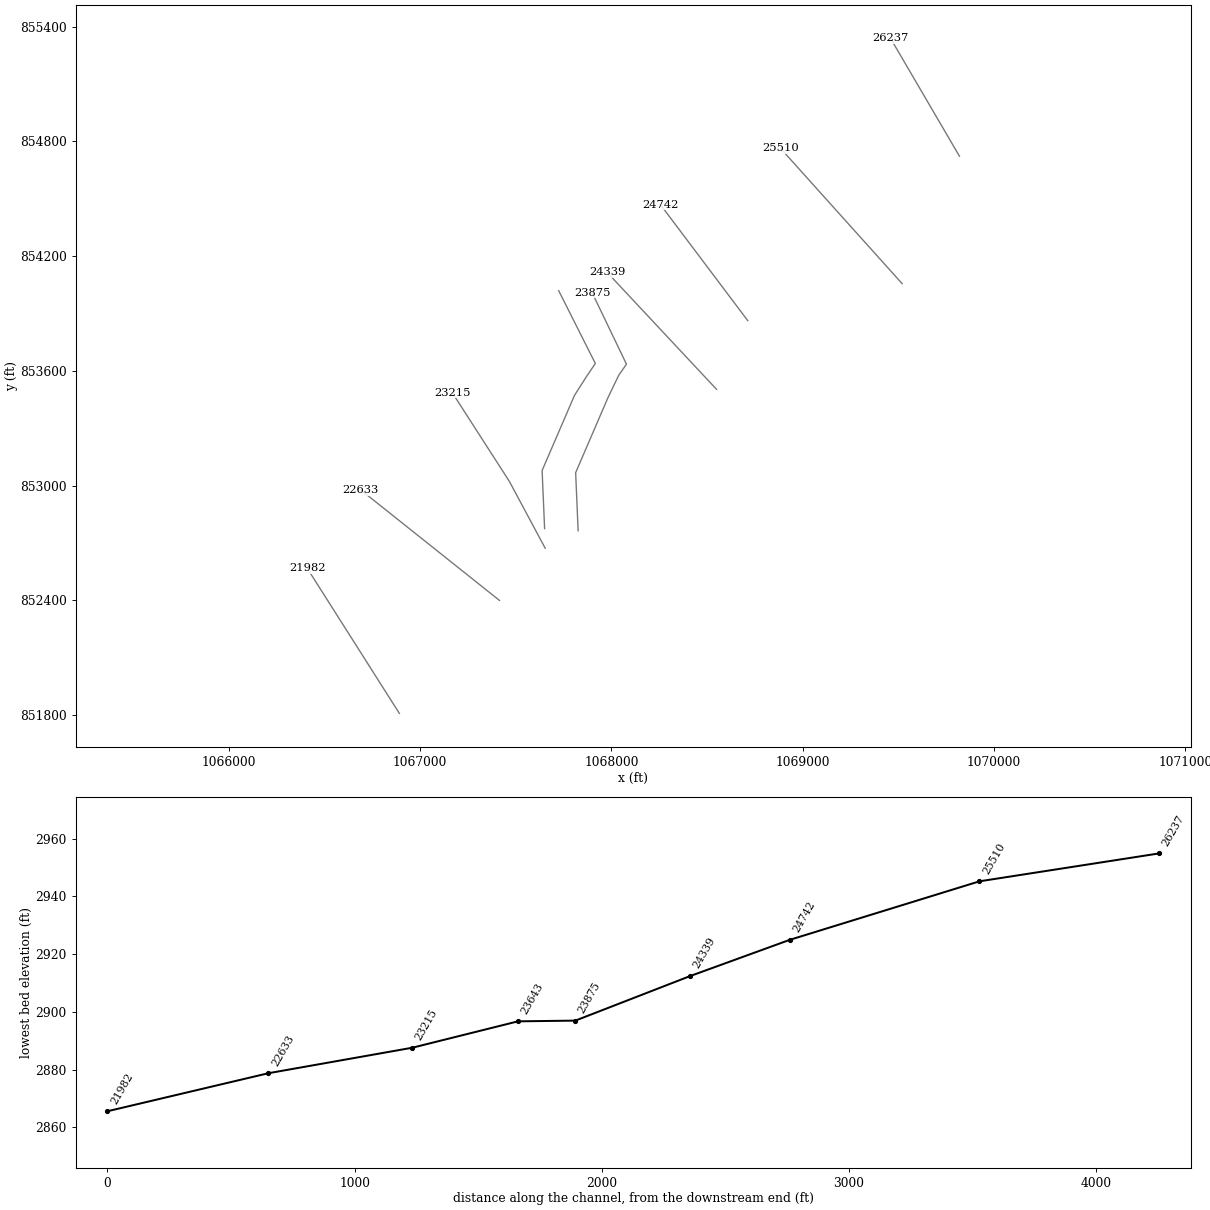
HEC-RAS study lds_little_rock_crk.prj: Little Rock Creek Limited Detail Study

--- lds_little_rock_crk.g01 (geometry) --- (continued)

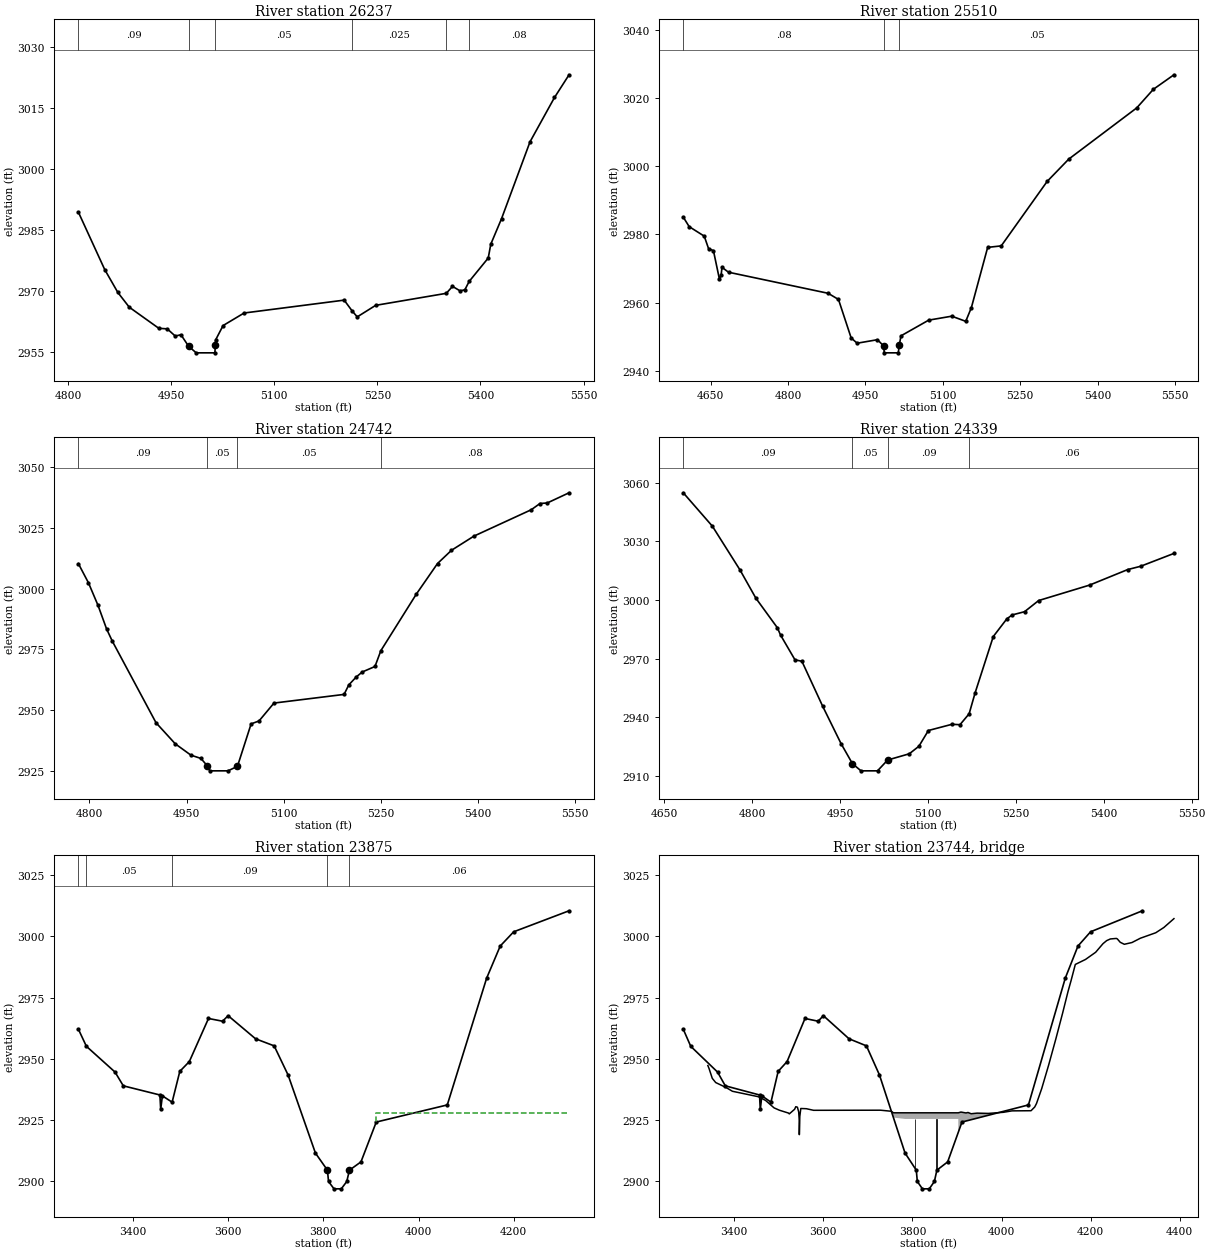
Type RM Length L Ch R = 1 ,26237   ,727,727,727
BEGIN DESCRIPTION:
Little_Rock_Crk_77
END DESCRIPTION:
XS GIS Cut Line= 2
      1069819.52       854722.17      1069459.27       855338.49
#Sta/Elev= 30
    4815 2989.39  4853.3 2975.31  4872.4 2969.69    4889 2966.08    4932  2960.9
  4944.3 2960.76  4955.9    2959  4964.2 2959.32  4975.3 2956.51  4986.4 2954.88
  5013.6 2954.88 5014.22 2956.71  5014.6 2958.03  5025.5 2961.57  5056.1 2964.65
  5201.7 2967.81  5213.2 2965.18  5220.7  2963.7  5247.5 2966.53  5350.3 2969.48
  5359.3 2971.19  5370.3 2970.08  5377.3 2970.35  5383.5 2972.39  5411.3 2978.14
    5415 2981.53  5430.6 2987.77  5472.1 3006.65  5507.7 3017.52  5528.9 3023.09
#Mann= 6 ,-1 , 0
    4815     .09       0  4975.3     .05       0 5014.22     .05       0
  5213.2    .025       0  5350.3     .05       0  5383.5     .08       0
#XS Ineff= 2 , 0
       0                  5201.7       0 2967.81
Permanent Ineff=
       F       F
Bank Sta=4975.3,5014.22
Exp/Cntr=0.3,0.1

Type RM Length L Ch R = 1 ,25510   ,768,768,768
BEGIN DESCRIPTION:
Little_Rock_Crk_76
END DESCRIPTION:
XS GIS Cut Line= 2
      1069520.04       854055.94      1068884.19       854763.41
#Sta/Elev= 30
  4596.8  2985.1  4608.3  2982.3  4637.5 2979.51  4645.9 2975.82  4655.3 2975.25
  4666.9 2966.89  4670.2 2968.06  4671.9 2970.35  4684.5 2968.91  4877.6 2962.72
  4897.7 2960.91  4922.3 2949.59  4933.9 2948.05  4973.3 2949.08 4985.49  2947.2
  4986.4 2945.22  5013.6 2945.22 5015.53 2947.41  5018.8 2950.21  5072.6 2954.83
  5117.3 2955.99  5144.4 2954.48  5155.3 2958.49  5186.9 2976.21  5213.2 2976.65
  5302.2 2995.59  5344.1 3002.15  5475.9  3017.2  5508.1 3022.66    5548 3026.93
#Mann= 3 , 0 , 0
  4596.8     .08       0 4985.49     .05       0 5015.53     .05       0
Bank Sta=4985.49,5015.53
Exp/Cntr=0.3,0.1

Type RM Length L Ch R = 1 ,24742   ,403,403,403
BEGIN DESCRIPTION:
Little_Rock_Crk_75
END DESCRIPTION:
XS GIS Cut Line= 2
      1068712.75        853862.8      1068257.02       854468.27
#Sta/Elev= 30
    4783 3010.31  4798.6 3002.39  4813.3 2993.14  4826.5 2983.45  4835.3 2978.43
  4902.9 2944.77  4932.6 2936.09  4956.8 2931.41  4972.3 2930.06 4982.07 2927.01
  4985.9 2924.95  5014.1 2924.95  5028.7 2926.81  5049.8  2944.3    5062  2945.5
  5085.1 2952.87  5193.4 2956.44  5200.6 2960.33  5212.2 2963.63  5221.4 2965.67
  5241.1 2967.94  5250.2 2974.46    5305 2997.77  5337.7 3010.36  5359.3 3015.82
    5394 3021.66  5482.4 3032.51    5496 3035.09  5507.2 3035.31  5540.9 3039.51
#Mann= 4 ,-1 , 0
    4783     .09       0 4982.07     .05       0  5028.7     .05       0
  5250.2     .08       0
Bank Sta=4982.07,5028.7
Exp/Cntr=0.3,0.1

Type RM Length L Ch R = 1 ,24339   ,464,464,464
BEGIN DESCRIPTION:
little_rock_crk_a7
END DESCRIPTION:
XS GIS Cut Line= 2
      1068549.57       853503.69      1067977.72       854115.09
#Sta/Elev= 30
  4682.7 3054.97  4732.4 3037.83  4779.5  3015.4  4806.6 3000.92  4843.3 2985.74
  4848.6 2982.06  4873.3 2969.32  4885.1 2968.59  4920.6 2945.49  4951.8 2926.42
  4971.3  2916.1  4985.9 2912.41  5014.1 2912.41  5031.4 2917.96  5068.3 2921.15
  5084.7 2925.01  5100.9 2933.09  5141.1 2936.27  5154.8 2936.07  5170.4 2941.66
  5180.5  2952.3  5211.6 2981.27  5234.7 2990.33  5243.8 2992.34  5264.9 2993.99
    5289 2999.72  5375.9 3007.64    5441 3015.61    5463 3017.29  5519.8 3023.88
#Mann= 4 ,-1 , 0
  4682.7     .09       0  4971.3     .05       0  5031.4     .09       0
  5170.4     .06       0
Bank Sta=4971.3,5031.4
Exp/Cntr=0.5,0.3

Type RM Length L Ch R = 1 ,23875   ,232,232,232
BEGIN DESCRIPTION:
Little_Rock_Crk_74
END DESCRIPTION:
XS GIS Cut Line= 6
      1067826.14       852764.21      1067813.12       853068.03
      1067982.39       853460.82      1068038.81       853578.01
      1068078.81       853635.08      1067899.92        854007.7
#Sta/Elev= 30
3285.871 2962.083302.647 2955.123362.858  2944.63380.171    29393457.004 2935.27
 3458.69 2929.383462.215 2934.913482.668 2932.343498.831  2944.93518.825 2948.89
3559.042 2966.463588.612 2965.343600.256  2967.63657.862 2958.18 3696.93 2955.29
3726.118 2943.43 3783.57 2911.583808.773 2904.61 3811.07    29003822.562    2897
3837.883    28973849.373    29003854.965 2904.613879.172 2907.993911.269 2924.23
4060.418 2931.214143.074 2982.914171.571    29964199.839  3001.84316.123 3010.37
#Mann= 5 ,-1 , 0
3285.871     .09       03302.647     .05       03482.668     .09       0
3808.773     .05       03854.965     .06       0
#XS Ineff= 2 , 0
       03749.021    29283911.422       0    2928
Permanent Ineff=
       F       F
Bank Sta=3808.773,3854.965
Skew Angle= 40
Exp/Cntr=0.5,0.3

Type RM Length L Ch R = 3 ,23744   ,,,
BEGIN DESCRIPTION:
Little_Rock_Crk_73
Structure ID: Roan Mountain Road bridge
Approximate Survey Structure
END DESCRIPTION:
Bridge Culvert--1,0,-1,-1, 0
Deck Dist Width WeirC Skew NumUp NumDn MinLoCord MaxHiCord MaxSubmerge Is_Ogee
101,60,3,40, 60, 60, , , , 0, 1,1,,
3341.1033343.8613350.9853358.6453382.0863396.1813453.8653470.4873489.6383501.512
3522.1953523.7283535.6783538.3593542.0353544.8713546.1733546.3253547.398 3549.62
3562.1833578.1943728.5683752.6983757.4483757.4483902.9963902.9963909.0473920.232
3924.829  3931.83945.1293970.4084004.2684023.419 4066.244074.5144078.5754090.217
4105.6154121.931 4136.87 4149.284155.9444165.5964188.5014211.2524227.7224235.919
4244.1924257.6754259.8964266.4084275.5234292.6844311.6044346.0764364.2324386.907
 2947.27 2945.99 2942.05 2940.34  2938.3 2936.78 2934.58 2933.06 2930.01 2929.06
 2927.88 2927.55 2929.43 2930.49 2930.29 2928.36 2924.91 2919.09 2926.52 2929.76
 2929.67 2929.02 2929.06 2928.63    2928    2928    2928    2928 2928.31 2927.94
 2928.13 2927.62 2927.87 2927.75 2928.21 2928.79 2928.85 2930.37 2931.82 2937.89
 2947.37 2958.14 2968.48 2977.49 2981.82 2988.49 2990.53 2993.46 2996.96  2998.2
 2998.88  2999.1 2998.89 2997.52 2996.71 2997.42 2999.18 3001.41 3003.55 3007.16
    2877    2877    2877    2877    2877    2877    2877    2877    2877    2877
    2877    2877    2877    2877    2877    2877    2877    2877    2877    2877
    2877    2877    2877    2877    2877  2925.5  2925.5    2877    2877    2877
    2877    2877    2877    2877    2877    2877    2877    2877    2877    2877
    2877    2877    2877    2877    2877    2877    2877    2877    2877    2877
    2877    2877    2877    2877    2877    2877    2877    2877    2877    2877
3341.1033343.8613350.9853358.6453382.0863396.1813453.8653470.4873489.6383501.512
3522.1953523.7283535.6783538.3593542.0353544.8713546.1733546.3253547.398 3549.62
3562.1833578.1943728.5683752.6983757.4483757.4483902.9963902.9963909.0473920.232
3924.829  3931.83945.1293970.4084004.2684023.419 4066.244074.5144078.5754090.217
4105.6154121.931 4136.87 4149.284155.9444165.5964188.5014211.2524227.7224235.919
4244.1924257.6754259.8964266.4084275.5234292.6844311.6044346.0764364.2324386.907
 2947.27 2945.99 2942.05 2940.34  2938.3 2936.78 2934.58 2933.06 2930.01 2929.06
 2927.88 2927.55 2929.43 2930.49 2930.29 2928.36 2924.91 2919.09 2926.52 2929.76
 2929.67 2929.02 2929.06 2928.63    2928    2928    2928    2928 2928.31 2927.94
 2928.13 2927.62 2927.87 2927.75 2928.21 2928.79 2928.85 2930.37 2931.82 2937.89
 2947.37 2958.14 2968.48 2977.49 2981.82 2988.49 2990.53 2993.46 2996.96  2998.2
 2998.88  2999.1 2998.89 2997.52 2996.71 2997.42 2999.18 3001.41 3003.55 3007.16
    2877    2877    2877    2877    2877    2877    2877    2877    2877    2877
    2877    2877    2877    2877    2877    2877    2877    2877    2877    2877
    2877    2877    2877    2877    2877  2925.5  2925.5    2877    2877    2877
    2877    2877    2877    2877    2877    2877    2877    2877    2877    2877
    2877    2877    2877    2877    2877    2877    2877    2877    2877    2877
    2877    2877    2877    2877    2877    2877    2877    2877    2877    2877
Pier Skew, UpSta & Num, DnSta & Num=  ,3805.938, 2 ,3805.938, 2 , 0 , 0 , 0 ,,
       2       2
    2896  2925.5
       2       2
    2896  2925.5
Pier Skew, UpSta & Num, DnSta & Num=  ,3854.429, 2 ,3854.429, 2 , 0 , 0 , 0 ,,
       2       2
    2896  2925.5
       2       2
    2896  2925.5
BR Coef= 1 , 1 , 0 ,1.25, 0 ,,,0.8,0,2,0,
WSPro=,,,, 1 ,,,, 0 ,,,, 0 ,,,,-1 ,-1 ,-1 , 0 , 0 , 0 , 0 , 0
BC Design=,, 0 ,, 0 ,,,,,,
BC HTab HWMax=3010.37

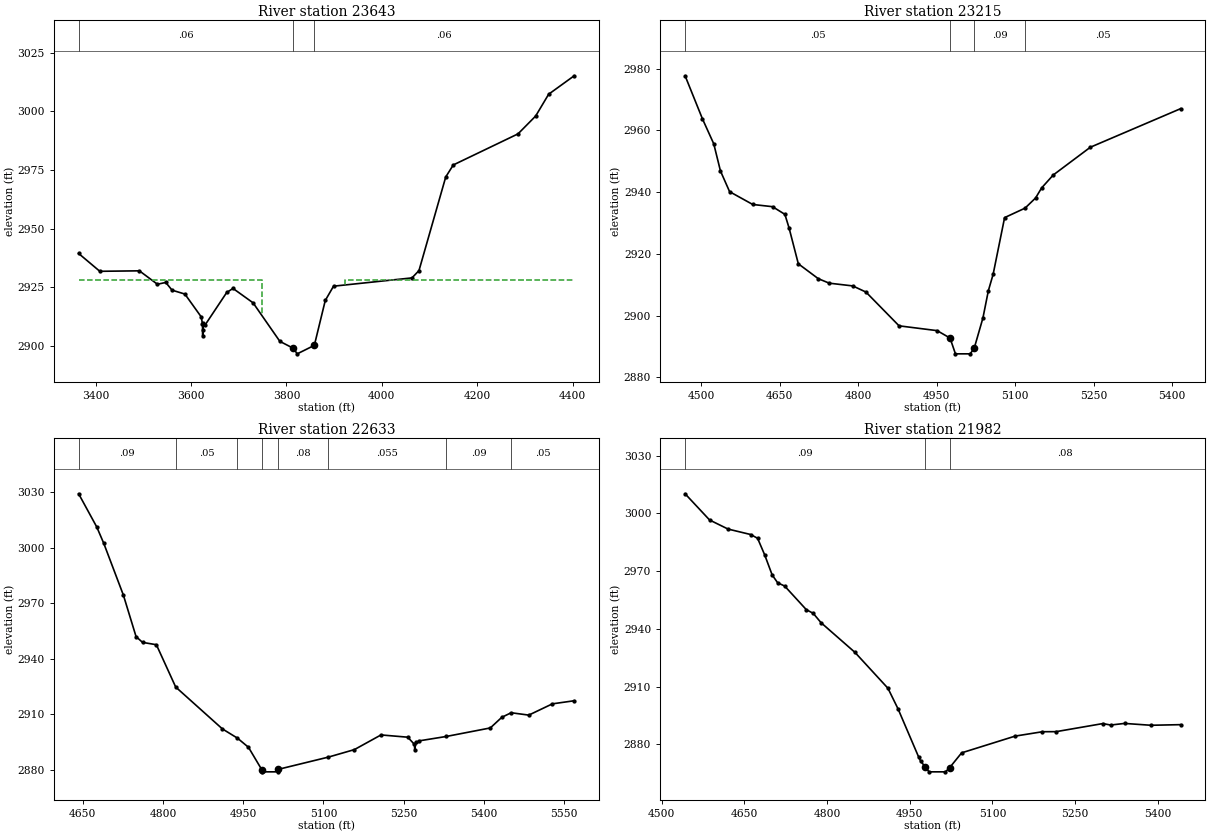
Type RM Length L Ch R = 1 ,23643   ,428,428,428
BEGIN DESCRIPTION:
Little_Rock_Crk_72
END DESCRIPTION:
XS GIS Cut Line= 6
      1067650.86       852775.56      1067637.84       853079.38
      1067807.11       853472.17      1067872.94       853575.28
      1067916.08       853638.86      1067724.64       854019.05
#Sta/Elev= 30
3364.084 2939.483408.515 2931.893491.477 2932.093529.396 2926.373546.862 2927.15
3559.962 2923.863586.926  2922.23621.321 2912.443623.773 2909.46 3624.31 2904.43
3624.463 2907.063625.228 2909.883629.289 2909.043674.638 2922.873687.815  2924.6
3729.947 2918.463786.097 2902.063814.059 2899.143822.562 2896.753858.412 2900.37
3881.317 2919.47 3898.63 2925.55  4063.1 2929.084077.807 2932.184133.959 2972.05
 4149.74 2977.164285.558  2990.44322.559    29984349.754 3007.27  4403.3 3015.13
#Mann= 3 , 0 , 0
3364.084     .06       03814.059     .05       03858.412     .06       0
#XS Ineff= 2 , 0
       03748.095    2928  3921.7       0    2928
Permanent Ineff=
       F       F
Bank Sta=3814.059,3858.412
Skew Angle= 40
Exp/Cntr=0.5,0.3

Type RM Length L Ch R = 1 ,23215   ,582,582,582
BEGIN DESCRIPTION:
little_rock_crk_a8
END DESCRIPTION:
XS GIS Cut Line= 3
      1067654.04       852672.89      1067467.02       853021.75
      1067168.51        853485.7
#Sta/Elev= 30
    4469 2977.67  4502.2 2963.71  4523.8 2955.63  4536.6 2946.84  4554.1 2940.13
  4598.3 2935.99  4636.2 2935.27  4659.8 2932.79  4667.8 2928.38  4685.5 2916.77
  4723.6 2911.96  4744.5  2910.5  4789.5 2909.61  4814.8 2907.62  4878.1 2896.68
    4951 2895.12  4975.6 2892.72  4985.9 2887.61  5014.1 2887.61  5021.8 2889.42
  5038.5 2899.25  5048.8 2908.02    5058 2913.39  5079.9 2931.73    5119  2934.8
  5139.1 2938.08  5150.7 2941.35  5172.9 2945.53  5243.8 2954.52  5416.5 2967.02
#Mann= 4 ,-1 , 0
    4469     .05       0  4975.6     .05       0  5021.8     .09       0
    5119     .05       0
Bank Sta=4975.6,5021.8
Exp/Cntr=0.3,0.1

Type RM Length L Ch R = 1 ,22633   ,651,651,651
BEGIN DESCRIPTION:
Little_Rock_Crk_71
END DESCRIPTION:
XS GIS Cut Line= 2
        1067415.       852400.13      1066690.18       852977.38
#Sta/Elev= 30
  4642.2 3029.03  4676.1 3011.09  4689.2 3002.25  4725.9 2974.26  4749.6 2951.85
  4761.7 2948.74  4787.6 2947.47  4823.7 2924.61    4911 2901.99  4939.2 2896.99
  4959.8 2892.05  4984.5 2880.02  4985.9 2878.79  5014.1 2878.79  5014.4 2880.06
  5109.3 2886.76  5157.8  2890.8  5207.6 2898.73  5257.6 2897.51  5270.2 2893.59
  5270.6 2890.77    5273 2894.65  5279.3 2895.55  5329.8 2897.91    5412 2902.51
  5433.5 2908.26    5451 2910.72  5483.9 2909.44  5528.1 2915.53  5568.8  2917.2
#Mann= 8 ,-1 , 0
  4642.2     .09       0  4823.7     .05       0  4939.2     .08       0
  4984.5     .05       0  5014.4     .08       0  5109.3    .055       0
  5329.8     .09       0    5451     .05       0
Bank Sta=4984.5,5014.4
Exp/Cntr=0.3,0.1

Type RM Length L Ch R = 1 ,21982   ,768,768,768
BEGIN DESCRIPTION:
little_rock_crk_a9
END DESCRIPTION:
XS GIS Cut Line= 2
      1066891.58       851809.73      1066409.65       852568.59
#Sta/Elev= 30
  4542.5 3010.25  4586.9 2996.62  4620.4  2991.9  4661.6 2989.05    4674  2987.1
  4686.8 2978.53  4700.4 2968.08  4710.4 2963.95  4723.1 2962.27  4762.4 2949.98
  4774.9 2948.08  4789.1 2943.21  4850.6 2927.78  4910.5  2909.1  4928.9 2898.33
  4966.3 2873.28  4970.2 2871.03 4977.99 2868.29  4985.1 2865.63  5014.9 2865.63
 5022.18 2867.72  5044.2 2875.51  5141.2 2884.21  5190.8 2886.49  5215.6 2886.53
  5300.3 2890.73  5314.6 2889.97  5339.8 2890.81  5387.5 2889.85  5441.5 2890.17
#Mann= 3 ,-1 , 0
  4542.5     .09       0 4977.99     .05       0 5022.18     .08       0
Bank Sta=4977.99,5022.18
Exp/Cntr=0.3,0.1