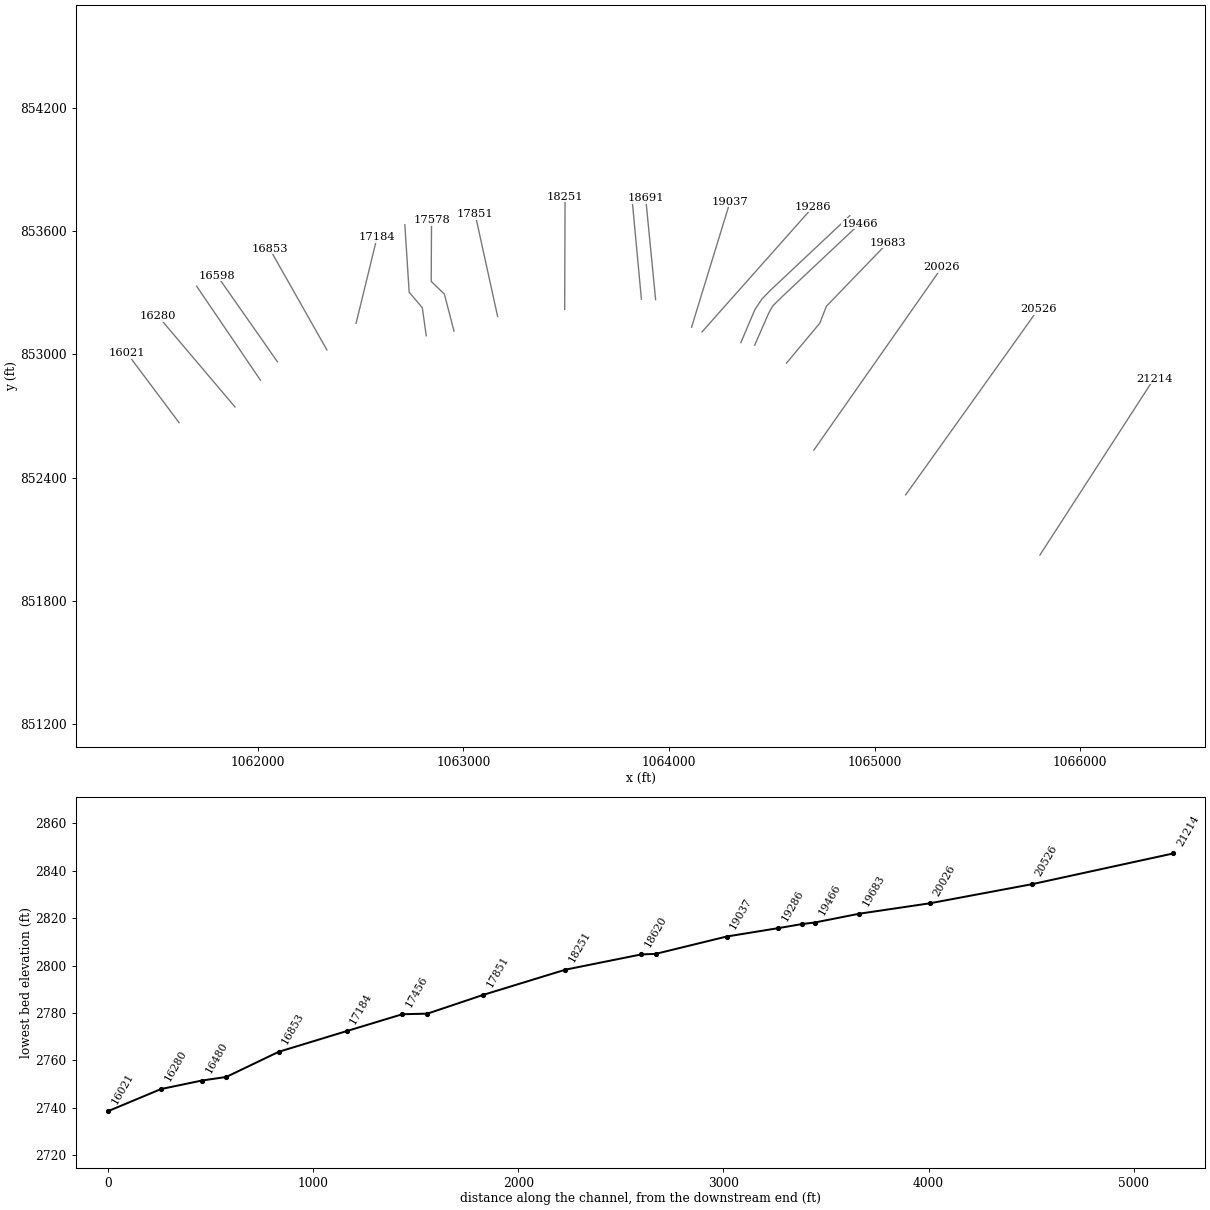
HEC-RAS study lds_little_rock_crk.prj: Little Rock Creek Limited Detail Study

--- lds_little_rock_crk.g01 (geometry) --- (continued)

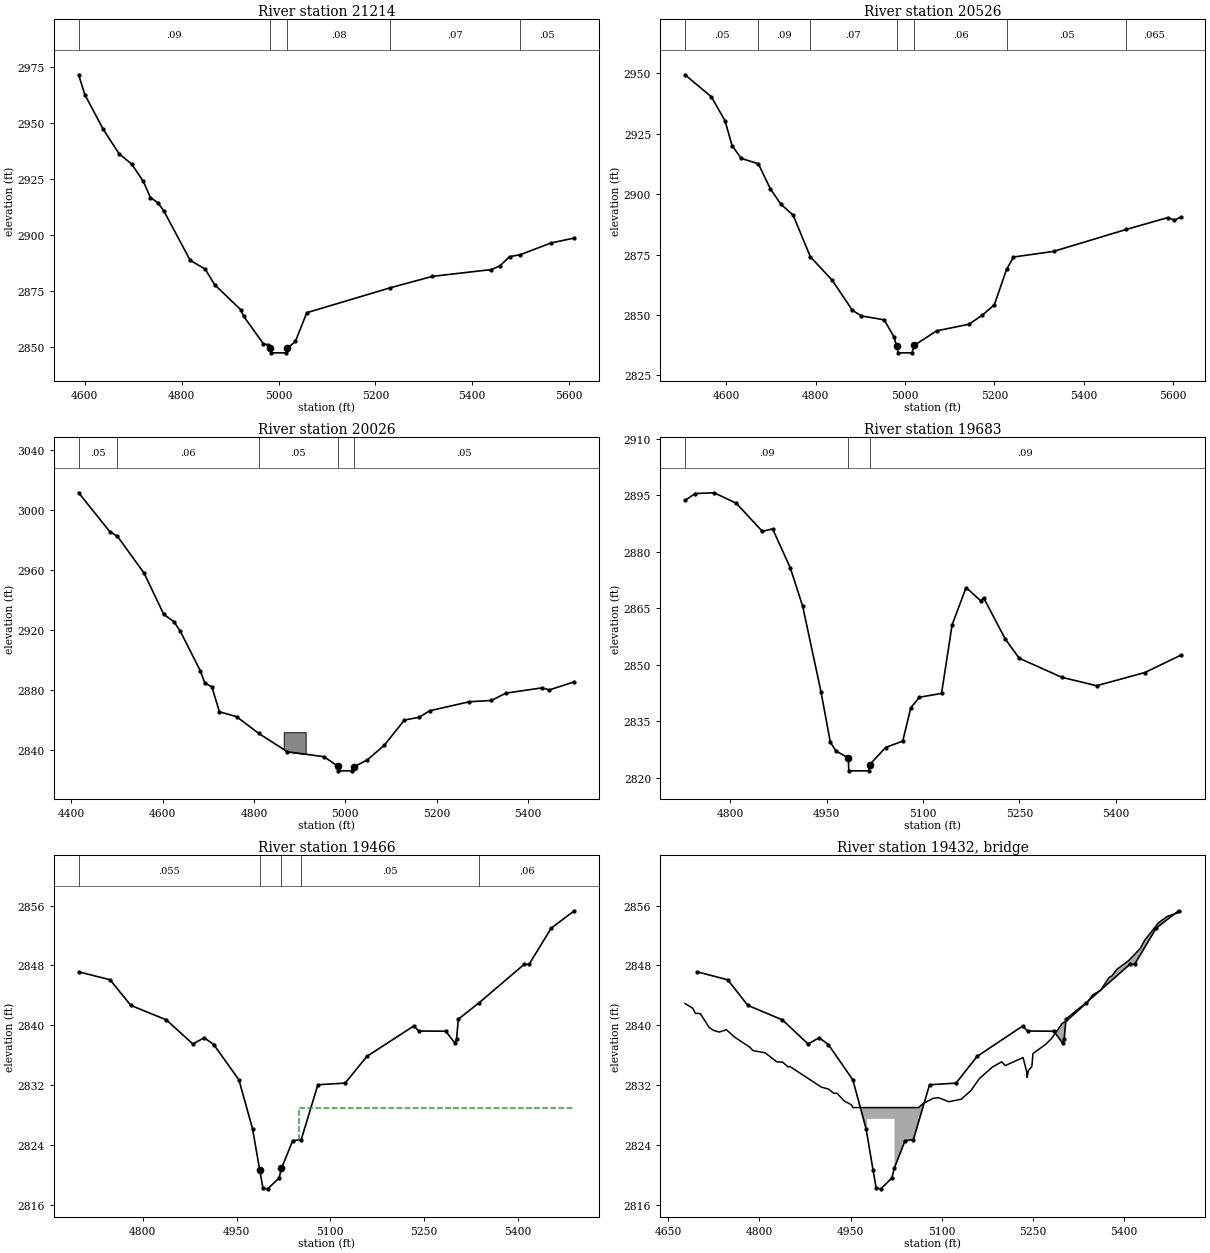
Type RM Length L Ch R = 1 ,21214   ,688,688,688
BEGIN DESCRIPTION:
Little_Rock_Crk_70
END DESCRIPTION:
XS GIS Cut Line= 2
      1065804.76       852022.52      1066360.32        852881.9
#Sta/Elev= 30
  4587.3 2971.39    4600 2962.57    4638 2947.08  4670.7 2936.17  4697.2 2931.44
  4720.9 2923.79  4735.6 2916.57  4751.4 2914.22  4763.4 2910.54  4817.7 2888.56
  4848.5 2884.68  4868.1  2877.7    4922 2866.53  4927.9 2863.67  4968.7 2851.33
    4979 2850.82 4981.66 2849.28  4985.1 2847.28  5014.9 2847.28  5017.9 2849.22
  5034.9 2852.37  5058.4  2865.2    5231 2876.33  5317.8 2881.42  5439.6 2884.45
  5457.1  2886.1  5477.1  2890.2  5499.2 2891.09  5562.7 2896.32  5610.6 2898.52
#Mann= 5 ,-1 , 0
  4587.3     .09       0 4981.66     .05       0  5017.9     .08       0
    5231     .07       0  5499.2     .05       0
Bank Sta=4981.66,5017.9
Exp/Cntr=0.3,0.1

Type RM Length L Ch R = 1 ,20526   ,500,500,500
BEGIN DESCRIPTION:
Little_Rock_Crk_69
END DESCRIPTION:
XS GIS Cut Line= 2
      1065151.55       852315.49      1065796.08       853218.27
#Sta/Elev= 30
  4507.5 2949.36  4566.4 2940.26  4596.9 2930.37  4612.8 2920.08  4633.2 2914.78
  4671.6 2912.53  4698.3 2902.23  4721.7 2895.88  4749.5 2891.28  4787.8 2874.11
  4836.8 2864.36  4882.2  2851.9  4902.4 2849.58  4953.2 2847.99  4975.4 2840.84
 4980.87 2837.06  4984.5 2834.32  5015.5 2834.32  5020.5  2837.4  5070.5 2843.41
  5142.8 2846.14    5173 2849.91  5199.7 2854.19  5227.2 2868.87  5242.6 2873.96
  5332.4  2876.3  5495.3 2885.39  5588.1 2890.28  5602.8 2889.19  5616.7 2890.45
#Mann= 7 ,-1 , 0
  4507.5     .05       0  4671.6     .09       0  4787.8     .07       0
 4980.87     .05       0  5020.5     .06       0  5227.2     .05       0
  5495.3    .065       0
Bank Sta=4980.87,5020.5
Exp/Cntr=0.3,0.1

Type RM Length L Ch R = 1 ,20026   ,343,343,343
BEGIN DESCRIPTION:
Little_Rock_Crk_68
END DESCRIPTION:
XS GIS Cut Line= 2
      1064704.53       852533.08      1065327.32       853422.45
#Sta/Elev= 30
  4415.7 3011.77  4484.2 2985.74  4500.8 2982.72  4559.2 2958.09  4602.2 2930.64
  4624.2 2925.84  4638.1 2919.55  4682.1 2893.11  4692.2 2884.75  4707.6 2882.26
  4724.1 2865.66  4761.8 2862.38  4809.9 2851.25  4873.1 2838.95  4953.3 2835.66
  4983.4 2829.28  4984.5 2826.23  5015.5 2826.23  5019.3 2828.92    5048 2833.53
  5085.2 2843.25  5129.4 2860.13  5161.9 2861.96  5184.4 2866.28  5271.9 2872.35
  5319.9 2873.18  5351.8 2878.08  5431.3 2881.61  5446.6  2880.2  5501.4 2885.61
#Mann= 5 ,-1 , 0
  4415.7     .05       0  4500.8     .06       0  4809.9     .05       0
  4983.4     .05       0  5019.3     .05       0
#Block Obstruct= 1 ,-1
    4865    4913    2852
Bank Sta=4983.4,5019.3
Exp/Cntr=0.3,0.1

Type RM Length L Ch R = 1 ,19683   ,217,217,217
BEGIN DESCRIPTION:
little_rock_crk_a10
END DESCRIPTION:
XS GIS Cut Line= 4
      1064571.83       852957.02      1064733.67       853151.23
      1064766.04       853233.95      1065064.55       853543.25
#Sta/Elev= 30
  4729.6 2893.67  4745.3 2895.51  4774.9 2895.71  4809.4 2892.93    4850 2885.44
  4865.9 2886.14  4893.4 2875.79  4912.7  2865.6  4941.2 2842.87  4955.8 2829.44
  4964.5 2827.15  4983.8 2825.26  4984.5 2821.85  5015.5 2821.85  5017.1 2823.49
  5041.7 2828.04  5068.5 2829.76    5081 2838.58  5094.4  2841.4  5128.9 2842.41
  5145.3 2860.59  5167.1 2870.54  5189.8 2867.03  5194.4 2867.81  5227.9 2856.93
  5249.7 2851.77  5316.1  2846.7  5370.3 2844.46  5445.2 2847.95  5501.1 2852.55
#Mann= 3 , 0 , 0
  4729.6     .09       0  4983.8     .05       0  5017.1     .09       0
Bank Sta=4983.8,5017.1
Exp/Cntr=0.5,0.3

Type RM Length L Ch R = 1 ,19466   ,61,61,61
BEGIN DESCRIPTION:
Little_Rock_Crk_67
END DESCRIPTION:
XS GIS Cut Line= 5
        1064417.       853044.12      1064484.51       853198.95
      1064505.47        853236.2      1064554.36       853283.92
      1064928.03       853635.48
#Sta/Elev= 30
  4697.4 2847.14  4747.7 2846.08  4780.8 2842.66  4837.8 2840.72  4880.1  2837.5
  4898.4 2838.33  4913.6 2837.42  4953.9  2832.7  4975.7 2826.15  4987.1 2820.68
  4992.3 2818.24    5000 2818.14  5018.2 2819.59  5021.9 2820.86  5039.9 2824.57
  5053.6 2824.72  5080.2 2832.05  5123.9 2832.27  5158.6 2835.84  5233.4 2839.89
  5241.9 2839.23  5284.8 2839.21  5299.8 2837.58  5302.1 2838.21    5305 2840.82
  5338.7 2843.04  5410.1 2848.13  5418.1 2848.14  5453.6 2852.98  5490.4  2855.3
#Mann= 5 ,-1 , 0
  4697.4    .055       0  4987.1     .05       0  5021.9     .06       0
  5053.6     .05       0  5338.7     .06       0
#XS Ineff= 2 , 0
       0  4949.5 2829.44  5050.5       0    2829
Permanent Ineff=
       F       F
Bank Sta=4987.1,5021.9
Exp/Cntr=0.5,0.3

Type RM Length L Ch R = 3 ,19432   ,,,
BEGIN DESCRIPTION:
Little_Rock_Crk_66
Structure ID: Fork Mountain Road side street 2
Approximate Survey Structure
END DESCRIPTION:
Bridge Culvert--1,0,-1,-1, 0
Deck Dist Width WeirC Skew NumUp NumDn MinLoCord MaxHiCord MaxSubmerge Is_Ogee
28,12,3,0, 60, 60, , , , 0, 0.5,0.5,,
  4677.4  4690.2  4694.4  4702.6  4717.1  4724.3  4733.8  4745.5  4758.6  4783.9
  4789.5  4809.4  4828.8  4837.8  4847.5  4849.9  4901.9  4913.7  4922.4  4927.7
  4939.5  4951.4  4954.1  4977.5  4977.5  5022.5  5022.5  5061.8  5069.3  5085.7
  5094.9    5112  5132.4  5148.2  5162.3    5184  5199.3  5204.8  5234.3  5240.3
    5241  5243.1  5248.8  5250.6  5271.7    5281  5298.7  5307.1  5340.3    5349
  5361.9  5375.7  5380.9  5389.3  5408.1  5427.1  5434.8  5457.2  5471.6  5493.9
 2842.91 2842.27  2841.6 2841.56 2839.71 2839.32 2839.09 2839.41 2838.44 2837.08
 2836.61 2836.32  2835.1 2835.09 2834.42  2834.5 2831.74 2831.47  2830.9 2830.92
  2829.9 2829.37    2829    2829    2829    2829    2829    2829 2829.52 2830.22
 2830.33 2829.78 2830.12 2831.25 2832.87 2834.43 2835.12 2834.61 2835.68  2833.8
 2833.03 2833.95 2834.49 2836.22 2837.46 2838.21 2840.25 2840.66 2843.06 2844.07
 2844.65 2846.37 2846.62 2847.51 2848.63 2850.24 2851.37 2853.68 2854.54 2855.15
    2798    2798    2798    2798    2798    2798    2798    2798    2798    2798
    2798    2798    2798    2798    2798    2798    2798    2798    2798    2798
    2798    2798    2798    2798  2827.5  2827.5    2798    2798    2798    2798
    2798    2798    2798    2798    2798    2798    2798    2798    2798    2798
    2798    2798    2798    2798    2798    2798    2798    2798    2798    2798
    2798    2798    2798    2798    2798    2798    2798    2798    2798    2798
  4677.4  4690.2  4694.4  4702.6  4717.1  4724.3  4733.8  4745.5  4758.6  4783.9
  4789.5  4809.4  4828.8  4837.8  4847.5  4849.9  4901.9  4913.7  4922.4  4927.7
  4939.5  4951.4  4954.1  4977.5  4977.5  5022.5  5022.5  5061.8  5069.3  5085.7
  5094.9    5112  5132.4  5148.2  5162.3    5184  5199.3  5204.8  5234.3  5240.3
    5241  5243.1  5248.8  5250.6  5271.7    5281  5298.7  5307.1  5340.3    5349
  5361.9  5375.7  5380.9  5389.3  5408.1  5427.1  5434.8  5457.2  5471.6  5493.9
 2842.91 2842.27  2841.6 2841.56 2839.71 2839.32 2839.09 2839.41 2838.44 2837.08
 2836.61 2836.32  2835.1 2835.09 2834.42  2834.5 2831.74 2831.47  2830.9 2830.92
  2829.9 2829.37    2829    2829    2829    2829    2829    2829 2829.52 2830.22
 2830.33 2829.78 2830.12 2831.25 2832.87 2834.43 2835.12 2834.61 2835.68  2833.8
 2833.03 2833.95 2834.49 2836.22 2837.46 2838.21 2840.25 2840.66 2843.06 2844.07
 2844.65 2846.37 2846.62 2847.51 2848.63 2850.24 2851.37 2853.68 2854.54 2855.15
    2798    2798    2798    2798    2798    2798    2798    2798    2798    2798
    2798    2798    2798    2798    2798    2798    2798    2798    2798    2798
    2798    2798    2798    2798  2827.5  2827.5    2798    2798    2798    2798
    2798    2798    2798    2798    2798    2798    2798    2798    2798    2798
    2798    2798    2798    2798    2798    2798    2798    2798    2798    2798
    2798    2798    2798    2798    2798    2798    2798    2798    2798    2798
BR Coef= 1 , 1 , 0 ,1.25, 0 ,,,0.8,0,2,0,
WSPro=,,,, 1 ,,,, 0 ,,,, 0 ,,,,-1 ,-1 ,-1 , 0 , 0 , 0 , 0 , 0
BC Design=,, 0 ,, 0 ,,,,,,
BC HTab HWMax=2855.3

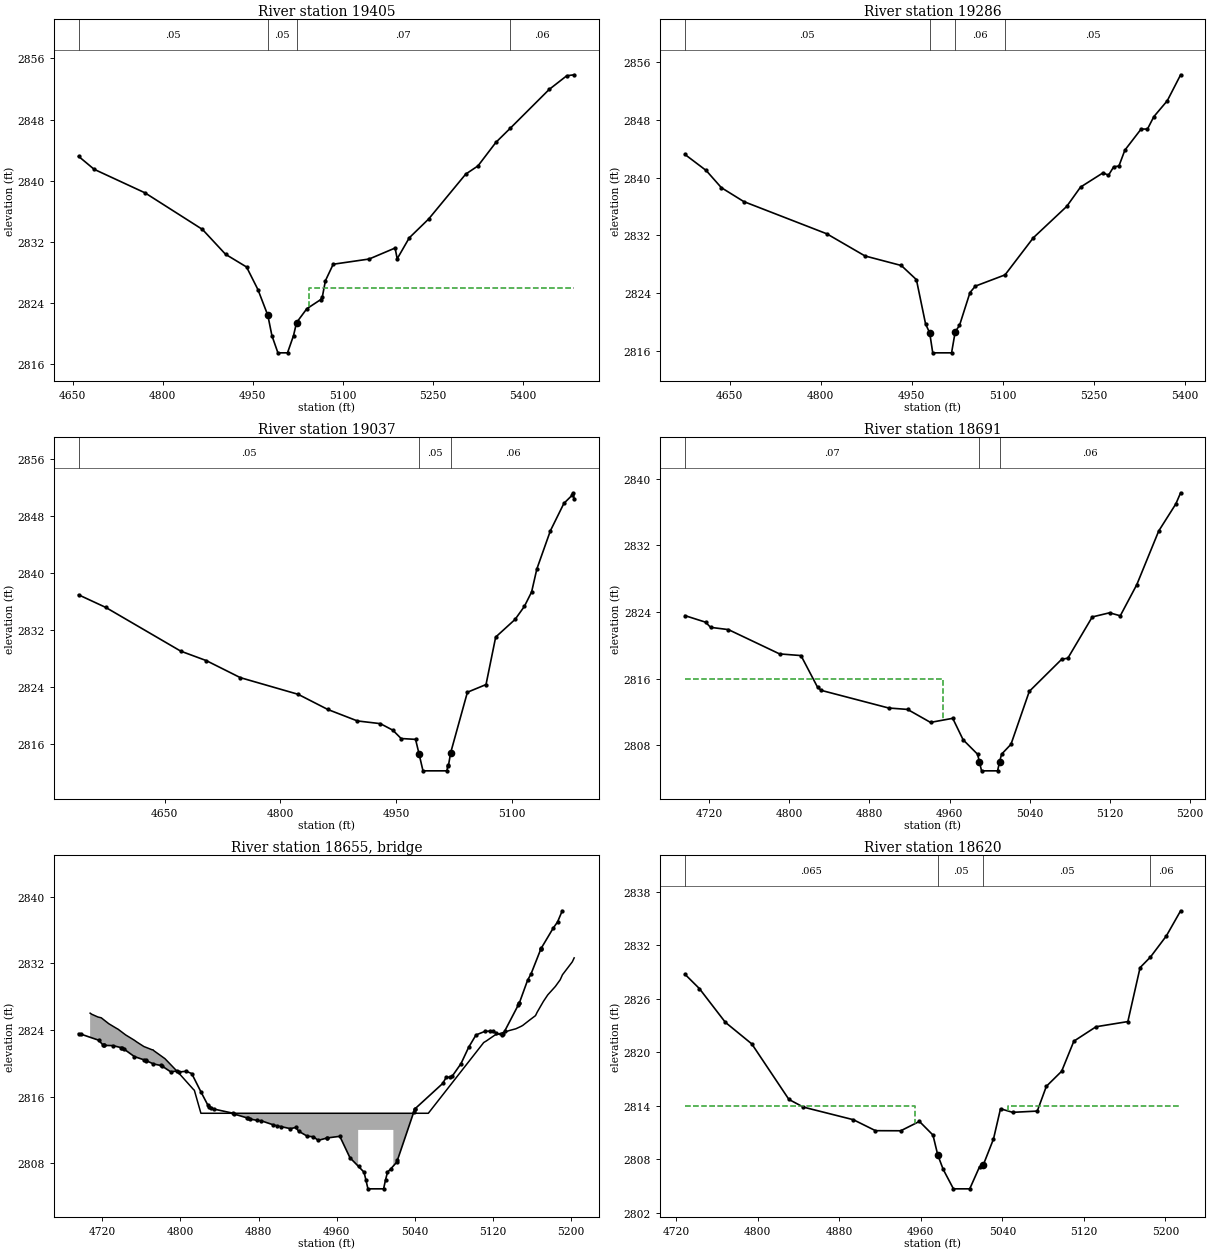
Type RM Length L Ch R = 1 ,19405   ,119,119,119
BEGIN DESCRIPTION:
Little_Rock_Crk_65
END DESCRIPTION:
XS GIS Cut Line= 5
      1064349.63       853056.38      1064418.16       853217.92
      1064453.08       853269.96      1064494.85       853312.56
      1064879.94        853674.8
#Sta/Elev= 30
  4659.5 2843.21  4685.5 2841.51  4770.3 2838.43  4866.2 2833.64  4904.7 2830.39
  4939.7 2828.73  4958.7 2825.77  4975.2  2822.4    4982 2819.75    4992  2817.5
    5008  2817.5    5018 2819.75  5023.1 2821.46  5040.2 2823.27  5063.1 2824.45
  5066.1 2824.83  5071.2 2826.93  5084.2 2829.09  5144.1 2829.77  5187.4 2831.21
  5190.9  2829.8    5211 2832.54  5243.4 2835.01  5305.2 2840.88  5325.6 2841.95
  5355.5 2845.03  5379.5 2846.88  5444.3 2851.95  5473.6 2853.74    5486 2853.87
#Mann= 4 ,-1 , 0
  4659.5     .05       0  4975.2     .05       0  5023.1     .07       0
  5379.5     .06       0
#XS Ineff= 2 , 0
       0  4956.5    2826  5043.5       0    2826
Permanent Ineff=
       F       F
Bank Sta=4975.2,5023.1
Exp/Cntr=0.5,0.3

Type RM Length L Ch R = 1 ,19286   ,249,249,249
BEGIN DESCRIPTION:
Little_Rock_Crk_64
END DESCRIPTION:
XS GIS Cut Line= 2
      1064160.35       853108.59      1064702.08       853718.86
#Sta/Elev= 30
  4576.6 2843.21  4611.5 2840.99  4636.5 2838.61  4673.5 2836.68  4810.1 2832.22
    4873 2829.15  4932.7 2827.83  4957.6 2825.87  4972.7 2819.73  4979.5 2818.49
  4984.5 2815.73  5015.5 2815.73  5021.5 2818.66  5028.5 2819.52  5045.8 2824.08
  5054.6 2824.97  5103.5 2826.53  5150.2 2831.68    5205 2836.01  5227.8 2838.69
  5264.9 2840.67  5273.8 2840.33  5282.4  2841.5    5291 2841.61  5300.8 2843.81
  5327.5 2846.73    5338 2846.73  5348.5 2848.45  5370.6 2850.65  5392.6 2854.25
#Mann= 4 ,-1 , 0
  4576.6     .05       0  4979.5     .05       0  5021.5     .06       0
  5103.5     .05       0
Bank Sta=4979.5,5021.5
Exp/Cntr=0.3,0.1

Type RM Length L Ch R = 1 ,19037   ,346,346,346
BEGIN DESCRIPTION:
Little_Rock_Crk_63
END DESCRIPTION:
XS GIS Cut Line= 3
      1064109.77       853131.44      1064297.42       853743.33
      1064295.78       853743.33
#Sta/Elev= 30
  4538.6 2836.96  4573.8 2835.19    4671 2829.04  4703.9 2827.72  4748.1 2825.32
  4822.9 2822.98  4861.3 2820.85  4899.6 2819.24  4929.3 2818.86  4945.5 2817.94
  4956.2 2816.77  4974.9 2816.65 4979.42 2814.61  4984.5 2812.23  5015.5 2812.23
  5016.5 2812.92  5017.5    2813 5020.33 2814.77    5042 2823.27  5066.1 2824.35
  5078.6 2831.02  5103.7  2833.5  5115.7 2835.32  5125.1 2837.36  5131.9 2840.59
  5149.4 2845.95  5166.9  2849.8  5177.4 2850.93  5178.6 2851.29  5180.2 2850.46
#Mann= 3 , 0 , 0
  4538.6     .05       0 4979.42     .05       0 5020.33     .06       0
Bank Sta=4979.42,5020.33
Exp/Cntr=0.5,0.3

Type RM Length L Ch R = 1 ,18691   ,71,71,71
BEGIN DESCRIPTION:
Little_Rock_Crk_62
END DESCRIPTION:
XS GIS Cut Line= 2
      1063934.96       853265.72      1063886.66       853758.55
#Sta/Elev= 30
  4695.7 2823.57  4716.3 2822.78  4721.3 2822.16  4739.1 2821.89  4790.2 2818.97
  4811.6 2818.77  4828.1 2814.98  4831.8 2814.59  4899.2 2812.47  4918.1  2812.3
    4941 2810.74  4963.2 2811.23  4973.6 2808.65    4988 2806.92 4989.84 2806.02
    4992 2804.92    5008 2804.92 5010.07 2806.03    5012 2806.92  5021.4 2808.11
  5039.7 2814.47  5072.2 2818.34  5078.2 2818.45  5102.6 2823.41  5119.9 2823.91
  5130.6 2823.55  5147.1 2827.29    5169 2833.74  5186.1 2836.99  5190.9 2838.33
#Mann= 3 , 0 , 0
  4695.7     .07       0 4989.84     .05       0 5010.07     .06       0
#XS Ineff= 2 , 0
       0    4953    2816    5047       0    2814
Permanent Ineff=
       F       F
Bank Sta=4989.84,5010.07
Exp/Cntr=0.5,0.3

Type RM Length L Ch R = 3 ,18655   ,,,
BEGIN DESCRIPTION:
Little_Rock_Crk_61
Structure ID: Fork Mountain Road side street 1
Approximate Survey Structure
END DESCRIPTION:
Bridge Culvert--1,0,-1,-1, 0
Deck Dist Width WeirC Skew NumUp NumDn MinLoCord MaxHiCord MaxSubmerge Is_Ogee
29,14,3,0, 55, 55, , , , 0, 0.5,0.5,,
  4707.6  4709.2  4715.5    4719  4721.8  4726.7  4732.8  4734.8  4736.2    4744
  4751.7  4752.8  4755.3  4762.6    4771    4772  4772.8  4784.2  4796.6  4796.7
  4796.9  4811.7  4812.9  4814.3    4821    4982    4982    5018    5018  5035.2
  5036.7  5043.2  5049.5  5053.8  5110.5  5113.2  5121.9  5130.5  5133.6  5136.7
  5143.4  5148.7  5150.4  5157.5  5163.5  5165.2  5171.6  5176.1  5183.8  5188.8
  5191.1  5201.1  5201.4  5201.5  5203.1
 2826.03  2825.9 2825.57 2825.47 2825.21 2824.76 2824.33 2824.19  2824.1 2823.41
 2822.86 2822.78 2822.57 2822.02 2821.63 2821.62 2821.52 2820.56 2819.05 2819.03
 2819.02 2817.08 2816.92 2816.76    2814    2814    2814    2814    2814    2814
    2814    2814    2814    2814  2822.5 2822.69 2823.39 2823.71 2823.81 2823.94
 2824.15 2824.44 2824.55  2825.2 2825.73 2826.14 2827.44 2828.23 2829.23 2830.04
 2830.64 2832.18 2832.24 2832.27 2832.67
 2784.92 2784.92 2784.92 2784.92 2784.92 2784.92 2784.92 2784.92 2784.92 2784.92
 2784.92 2784.92 2784.92 2784.92 2784.92 2784.92 2784.92 2784.92 2784.92 2784.92
 2784.92 2784.92 2784.92 2784.92 2784.92 2784.92    2812    2812 2784.92 2784.92
 2784.92 2784.92 2784.92 2784.92 2784.92 2784.92 2784.92 2784.92 2784.92 2784.92
 2784.92 2784.92 2784.92 2784.92 2784.92 2784.92 2784.92 2784.92 2784.92 2784.92
 2784.92 2784.92 2784.92 2784.92 2784.92
  4707.6  4709.2  4715.5    4719  4721.8  4726.7  4732.8  4734.8  4736.2    4744
  4751.7  4752.8  4755.3  4762.6    4771    4772  4772.8  4784.2  4796.6  4796.7
  4796.9  4811.7  4812.9  4814.3    4821    4982    4982    5018    5018  5035.2
  5036.7  5043.2  5049.5  5053.8  5110.5  5113.2  5121.9  5130.5  5133.6  5136.7
  5143.4  5148.7  5150.4  5157.5  5163.5  5165.2  5171.6  5176.1  5183.8  5188.8
  5191.1  5201.1  5201.4  5201.5  5203.1
 2826.03  2825.9 2825.57 2825.47 2825.21 2824.76 2824.33 2824.19  2824.1 2823.41
 2822.86 2822.78 2822.57 2822.02 2821.63 2821.62 2821.52 2820.56 2819.05 2819.03
 2819.02 2817.08 2816.92 2816.76    2814    2814    2814    2814    2814    2814
    2814    2814    2814    2814  2822.5 2822.69 2823.39 2823.71 2823.81 2823.94
 2824.15 2824.44 2824.55  2825.2 2825.73 2826.14 2827.44 2828.23 2829.23 2830.04
 2830.64 2832.18 2832.24 2832.27 2832.67
 2784.92 2784.92 2784.92 2784.92 2784.92 2784.92 2784.92 2784.92 2784.92 2784.92
 2784.92 2784.92 2784.92 2784.92 2784.92 2784.92 2784.92 2784.92 2784.92 2784.92
 2784.92 2784.92 2784.92 2784.92 2784.92 2784.92    2812    2812 2784.92 2784.92
 2784.92 2784.92 2784.92 2784.92 2784.92 2784.92 2784.92 2784.92 2784.92 2784.92
 2784.92 2784.92 2784.92 2784.92 2784.92 2784.92 2784.92 2784.92 2784.92 2784.92
 2784.92 2784.92 2784.92 2784.92 2784.92
BR Coef= 1 , 1 , 0 ,1.25, 0 ,,,0.8,0,2,0,
WSPro=,,,, 1 ,,,, 0 ,,,, 0 ,,,,-1 ,-1 ,-1 , 0 , 0 , 0 , 0 , 0
BR U #Sta/Elev= 85
  4695.7 2823.57  4698.4  2823.5  4716.3 2822.78  4720.7 2822.21  4721.3 2822.16
  4722.2 2822.15  4730.9 2822.13  4739.1 2821.89  4740.5  2821.8  4742.5 2821.69
  4752.9 2820.81  4763.2  2820.4  4764.3 2820.37  4765.2 2820.31  4772.4 2819.93
  4779.9 2819.74  4781.5 2819.65  4790.2 2818.97  4796.1 2819.08    4799 2818.96
  4805.9 2819.05  4811.6 2818.77  4820.9  2816.6  4828.1 2814.98  4829.2 2814.79
  4831.8 2814.59  4834.1 2814.51  4853.7 2814.01  4854.9 2813.91  4868.4 2813.44
  4869.7 2813.38  4871.1 2813.31  4878.4 2813.15  4882.9 2813.09  4895.1 2812.61
  4899.2 2812.47  4903.2 2812.39  4912.7 2812.15  4918.1  2812.3    4921 2811.85
  4929.9 2811.24  4936.2 2811.18    4941 2810.74  4949.8 2811.02    4950 2811.03
  4963.2 2811.23  4973.6 2808.65 4982.34 2807.61    4988 2806.92 4989.84 2806.02
    4992 2804.92    5008 2804.92 5010.07 2806.03    5012 2806.92  5015.4 2807.33
  5021.4 2808.11  5022.2 2808.37  5038.9 2814.15  5039.7 2814.47  5040.2 2814.54
  5068.5 2817.58  5072.2 2818.34  5076.2 2818.32  5078.2 2818.45  5087.2 2819.95
  5095.1 2821.93  5102.6 2823.41  5111.5 2823.83  5117.1 2823.88  5119.9 2823.91
  5123.5 2823.61    5129 2823.37  5130.6 2823.55  5132.1  2823.9  5145.9 2827.01
  5146.9 2827.26  5147.1 2827.29  5155.4 2829.98    5159 2830.76  5168.9 2833.71
    5169 2833.74  5169.6 2833.87  5181.5 2836.22  5186.1 2836.99  5190.9 2838.33
BR U #Mann= 3
  4695.7     .07 4989.84    .045 5010.07     .06
BC Design=,, 0 ,, 0 ,,,,,,
BC HTab HWMax=2838.33

Type RM Length L Ch R = 1 ,18620   ,369,369,369
BEGIN DESCRIPTION:
Little_Rock_Crk_60
END DESCRIPTION:
XS GIS Cut Line= 2
      1063865.78       853267.89      1063820.64       853752.26
#Sta/Elev= 30
  4728.5 2828.76  4742.6 2827.16  4768.1 2823.37  4794.1 2820.94  4830.5 2814.71
  4844.6 2813.85  4893.8 2812.43  4915.5  2811.2  4940.3 2811.19  4958.6 2812.24
  4971.9 2810.71  4976.6 2808.48 4981.92 2806.86    4992 2804.67    5008 2804.67
 5017.59 2807.14  5021.4 2807.39  5031.3 2810.26  5038.2 2813.66  5050.1 2813.26
  5074.3  2813.4  5083.2 2816.18  5098.2 2817.87  5110.2 2821.25    5132 2822.87
  5163.2 2823.45  5175.2 2829.51  5185.4  2830.7    5201 2833.07    5215 2835.89
#Mann= 4 ,-1 , 0
  4728.5    .065       0  4976.6     .05       0  5021.4     .05       0
  5185.4     .06       0
#XS Ineff= 2 , 0
       0    4954    2814    5046       0    2814
Permanent Ineff=
       F       F
Bank Sta=4976.6,5021.4
Exp/Cntr=0.5,0.3

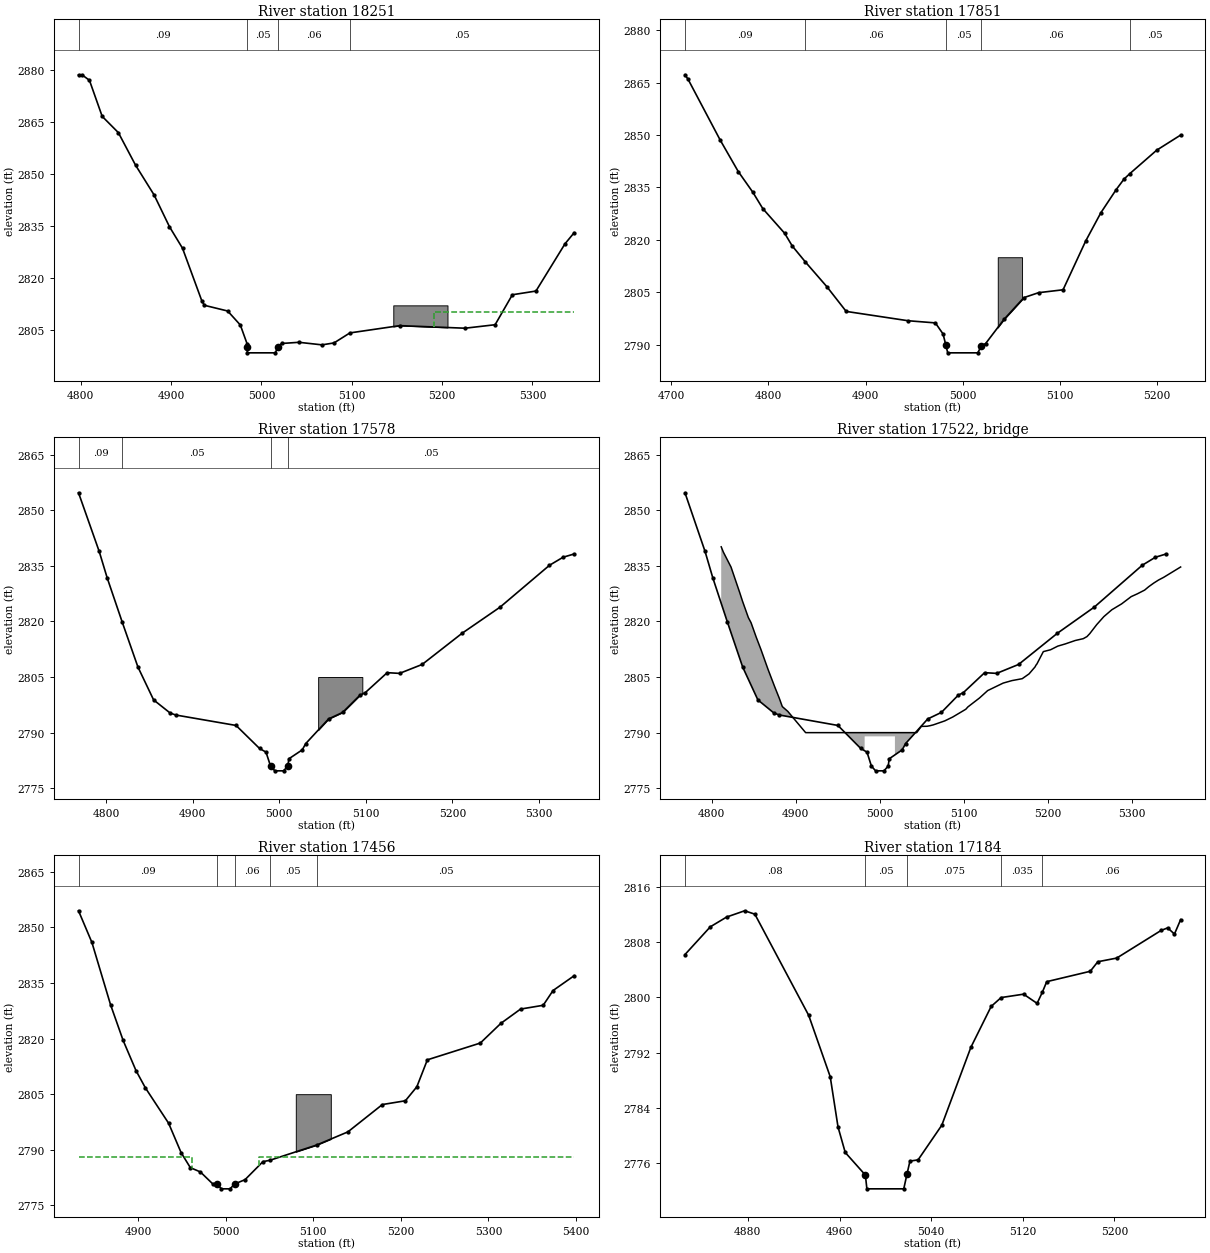
Type RM Length L Ch R = 1 ,18251   ,400,400,400
BEGIN DESCRIPTION:
Little_Rock_Crk_59
END DESCRIPTION:
XS GIS Cut Line= 2
      1063492.53       853218.65      1063494.26       853767.26
#Sta/Elev= 30
  4797.6 2878.72  4801.4 2878.76  4809.7 2877.16  4823.8 2866.72  4841.7 2862.01
  4860.8 2852.56  4881.3 2843.95  4898.3 2834.75  4912.7 2828.54  4934.1 2813.29
    4937 2812.01  4962.7 2810.36  4976.7 2806.31  4984.1 2800.93 4984.23 2799.91
  4984.5 2798.25  5015.5 2798.25 5018.15 2799.98  5022.4 2800.96  5041.6  2801.3
  5067.1 2800.56  5080.4 2801.12    5098 2804.02  5153.2 2806.13  5225.4 2805.38
  5258.7 2806.39  5277.8 2815.07  5303.9 2816.14  5336.1 2829.84  5346.2 2833.04
#Mann= 4 ,-1 , 0
  4797.6     .09       0 4984.23     .05       0 5018.15     .06       0
    5098     .05       0
#XS Ineff= 2 , 0
       0                    5191       0    2810
Permanent Ineff=
       F       F
#Block Obstruct= 1 ,-1
    5146    5206    2812
Bank Sta=4984.23,5018.15
Exp/Cntr=0.3,0.1

Type RM Length L Ch R = 1 ,17851   ,273,273,273
BEGIN DESCRIPTION:
Little_Rock_Crk_58
END DESCRIPTION:
XS GIS Cut Line= 2
      1063166.14       853183.92      1063056.76       853682.19
#Sta/Elev= 30
  4714.1 2867.23  4717.3 2865.93  4750.2 2848.61  4768.9 2839.54  4783.9 2833.62
  4794.2 2828.91  4816.7 2821.85  4824.5 2818.22  4838.1 2813.62  4860.2 2806.54
    4880 2799.49  4943.7 2796.82  4971.8  2796.2  4979.7 2793.03 4982.61 2789.81
  4984.5 2787.63  5015.5 2787.63  5019.1 2789.68  5023.5 2790.29  5042.4  2797.2
  5062.9 2803.44    5078 2804.85  5103.2 2805.68  5126.5 2819.65  5142.1 2827.73
  5157.9 2834.37  5165.9 2837.36  5171.8  2838.9  5199.6 2845.65  5224.2 2849.97
#Mann= 5 ,-1 , 0
  4714.1     .09       0  4838.1     .06       0 4982.61     .05       0
  5019.1     .06       0  5171.8     .05       0
#Block Obstruct= 2 ,-1
    5036    5061    2815
Bank Sta=4982.61,5019.1
Exp/Cntr=0.5,0.3

Type RM Length L Ch R = 1 ,17578   ,122,122,122
BEGIN DESCRIPTION:
Little_Rock_Crk_57
END DESCRIPTION:
XS GIS Cut Line= 4
      1062953.94       853112.28      1062907.09       853292.87
      1062842.96       853354.76      1062844.56       853651.34
#Sta/Elev= 30
  4768.3 2854.68  4792.2 2838.85  4801.4 2831.74  4818.8 2819.78  4836.9  2807.7
    4855 2798.83  4874.2 2795.27  4880.7 2794.75  4950.2 2791.94  4977.3 2785.74
  4984.8 2784.74    4990    2781    4995  2779.7    5005  2779.7    5010    2781
  5011.2 2782.95  5026.6 2785.35  5030.7 2787.06    5057 2793.69  5073.3 2795.46
  5093.3  2800.1  5099.5 2800.81  5124.7 2806.17    5139 2805.98  5165.1 2808.39
  5211.2  2816.8  5255.1 2823.85  5312.1 2835.13  5327.8  2837.3  5340.6 2838.18
#Mann= 4 ,-1 , 0
  4768.3     .09       0  4818.8     .05       0    4990     .05       0
    5010     .05       0
#XS Ineff= 2 , 0
       0    4952    2790    5048       0    2790
Permanent Ineff=
       F       F
#Block Obstruct= 1 ,-1
    5045    5096    2805
Bank Sta=4990,5010
Exp/Cntr=0.5,0.3

Type RM Length L Ch R = 3 ,17522   ,,,
BEGIN DESCRIPTION:
Little_Rock_Crk_56
Structure ID: Northside Drive
Approximate Survey Structure
END DESCRIPTION:
Bridge Culvert--1,0,-1,-1, 0
Deck Dist Width WeirC Skew NumUp NumDn MinLoCord MaxHiCord MaxSubmerge Is_Ogee
49,14,3,0, 58, 58, , , , 0, 0.5,0.5,,
  4811.4  4813.9  4823.1  4833.5  4836.7  4843.7  4846.9    4853  4858.7  4867.1
  4875.2  4880.6  4883.7  4884.2  4890.6  4911.8    4982    4982    5018    5018
  5043.9  5049.3  5056.2  5059.7  5063.7  5077.3  5086.8  5102.3  5104.8  5118.6
  5128.3  5146.7  5157.1  5169.4  5177.5  5184.7  5185.7  5186.8  5194.5  5203.1
  5211.7  5220.4  5232.5    5242  5246.4  5249.8    5258  5266.5    5276  5287.6
    5299  5306.2    5315  5319.8  5325.8  5331.5  5337.7  5357.8
 2840.11  2838.7 2834.63  2827.7 2825.47 2821.01 2819.64 2815.76 2812.39 2807.05
 2802.26  2799.2 2797.24    2797 2795.73    2790    2790    2790    2790    2790
    2790 2791.69 2791.72 2791.87  2792.1 2793.17 2794.22 2796.31 2796.94 2799.35
 2801.34 2803.36 2804.03 2804.55 2805.84 2807.74 2808.19 2808.49 2811.85 2812.35
 2813.33 2813.91 2814.85 2815.34  2815.9 2816.72 2819.13 2821.29 2823.14 2824.72
 2826.68 2827.42 2828.44 2829.35 2830.33 2831.15 2831.89 2834.67
  2759.7  2759.7  2759.7  2759.7  2759.7  2759.7  2759.7  2759.7  2759.7  2759.7
  2759.7  2759.7  2759.7  2759.7  2759.7  2759.7  2759.7    2789    2789  2759.7
  2759.7  2759.7  2759.7  2759.7  2759.7  2759.7  2759.7  2759.7  2759.7  2759.7
  2759.7  2759.7  2759.7  2759.7  2759.7  2759.7  2759.7  2759.7  2759.7  2759.7
  2759.7  2759.7  2759.7  2759.7  2759.7  2759.7  2759.7  2759.7  2759.7  2759.7
  2759.7  2759.7  2759.7  2759.7  2759.7  2759.7  2759.7  2759.7
  4811.4  4813.9  4823.1  4833.5  4836.7  4843.7  4846.9    4853  4858.7  4867.1
  4875.2  4880.6  4883.7  4884.2  4890.6  4911.8    4982    4982    5018    5018
  5043.9  5049.3  5056.2  5059.7  5063.7  5077.3  5086.8  5102.3  5104.8  5118.6
  5128.3  5146.7  5157.1  5169.4  5177.5  5184.7  5185.7  5186.8  5194.5  5203.1
  5211.7  5220.4  5232.5    5242  5246.4  5249.8    5258  5266.5    5276  5287.6
    5299  5306.2    5315  5319.8  5325.8  5331.5  5337.7  5357.8
 2840.11  2838.7 2834.63  2827.7 2825.47 2821.01 2819.64 2815.76 2812.39 2807.05
 2802.26  2799.2 2797.24    2797 2795.73    2790    2790    2790    2790    2790
    2790 2791.69 2791.72 2791.87  2792.1 2793.17 2794.22 2796.31 2796.94 2799.35
 2801.34 2803.36 2804.03 2804.55 2805.84 2807.74 2808.19 2808.49 2811.85 2812.35
 2813.33 2813.91 2814.85 2815.34  2815.9 2816.72 2819.13 2821.29 2823.14 2824.72
 2826.68 2827.42 2828.44 2829.35 2830.33 2831.15 2831.89 2834.67
  2759.7  2759.7  2759.7  2759.7  2759.7  2759.7  2759.7  2759.7  2759.7  2759.7
  2759.7  2759.7  2759.7  2759.7  2759.7  2759.7  2759.7    2789    2789  2759.7
  2759.7  2759.7  2759.7  2759.7  2759.7  2759.7  2759.7  2759.7  2759.7  2759.7
  2759.7  2759.7  2759.7  2759.7  2759.7  2759.7  2759.7  2759.7  2759.7  2759.7
  2759.7  2759.7  2759.7  2759.7  2759.7  2759.7  2759.7  2759.7  2759.7  2759.7
  2759.7  2759.7  2759.7  2759.7  2759.7  2759.7  2759.7  2759.7
BR Coef= 1 , 1 , 0 ,1.25, 0 ,,,0.8,0,2,0,
WSPro=,,,, 1 ,,,, 0 ,,,, 0 ,,,,-1 ,-1 ,-1 , 0 , 0 , 0 , 0 , 0
BC Design=,, 0 ,, 0 ,,,,,,
BC HTab HWMax=2854.68

Type RM Length L Ch R = 1 ,17456   ,272,272,272
BEGIN DESCRIPTION:
Little_Rock_Crk_55
END DESCRIPTION:
XS GIS Cut Line= 4
      1062818.87       853089.89      1062799.58       853226.83
      1062735.77        853301.8      1062714.68       853630.58
#Sta/Elev= 30
  4831.8  2854.5  4847.1 2845.96  4868.4 2829.14  4882.8 2819.49  4897.5 2811.35
  4908.2  2806.7  4934.7 2797.17    4949 2789.22  4959.5 2785.18    4971 2784.01
    4985 2780.82    4990 2780.75    4995 2779.45    5005 2779.45    5010 2780.75
    5022 2781.92  5042.5  2786.8  5050.2 2787.14  5103.8 2791.27  5139.5 2794.82
  5178.9  2802.2  5205.2 2803.22  5218.3    2807  5230.3 2814.27  5290.8  2818.8
  5314.3 2824.12  5336.8 2827.97  5362.6 2828.99  5373.9 2832.98    5398 2836.97
#Mann= 5 ,-1 , 0
  4831.8     .09       0    4990     .05       0    5010     .06       0
  5050.2     .05       0  5103.8     .05       0
#XS Ineff= 2 , 0
       0    4962    2788    5038       0    2788
Permanent Ineff=
       F       F
#Block Obstruct= 1 ,-1
    5080    5120    2805
Bank Sta=4990,5010
Exp/Cntr=0.5,0.3

Type RM Length L Ch R = 1 ,17184   ,331,331,331
BEGIN DESCRIPTION:
Little_Rock_Crk_54
END DESCRIPTION:
XS GIS Cut Line= 2
      1062477.38       853150.28      1062579.77       853570.61
#Sta/Elev= 30
  4825.1  2806.2  4847.2 2810.21  4861.4 2811.62  4877.2 2812.53  4886.1 2812.04
  4933.1 2797.41  4951.9 2788.53  4958.7 2781.27    4965 2777.58 4982.59 2774.31
  4983.9 2772.32  5016.1 2772.32 5018.85 2774.41  5021.5 2776.33  5028.6 2776.51
  5049.3 2781.52  5074.7 2792.79  5092.4  2798.7  5101.1 2799.98  5120.7 2800.47
  5132.5 2799.14  5137.2  2800.8  5140.9 2802.28  5178.9 2803.78  5185.5 2805.16
    5202 2805.69  5240.7 2809.68  5246.5 2810.06  5252.4 2809.16  5257.8 2811.25
#Mann= 5 ,-1 , 0
  4825.1     .08       0 4982.59     .05       0 5018.85    .075       0
  5101.1    .035       0  5137.2     .06       0
Bank Sta=4982.59,5018.85
Exp/Cntr=0.3,0.1

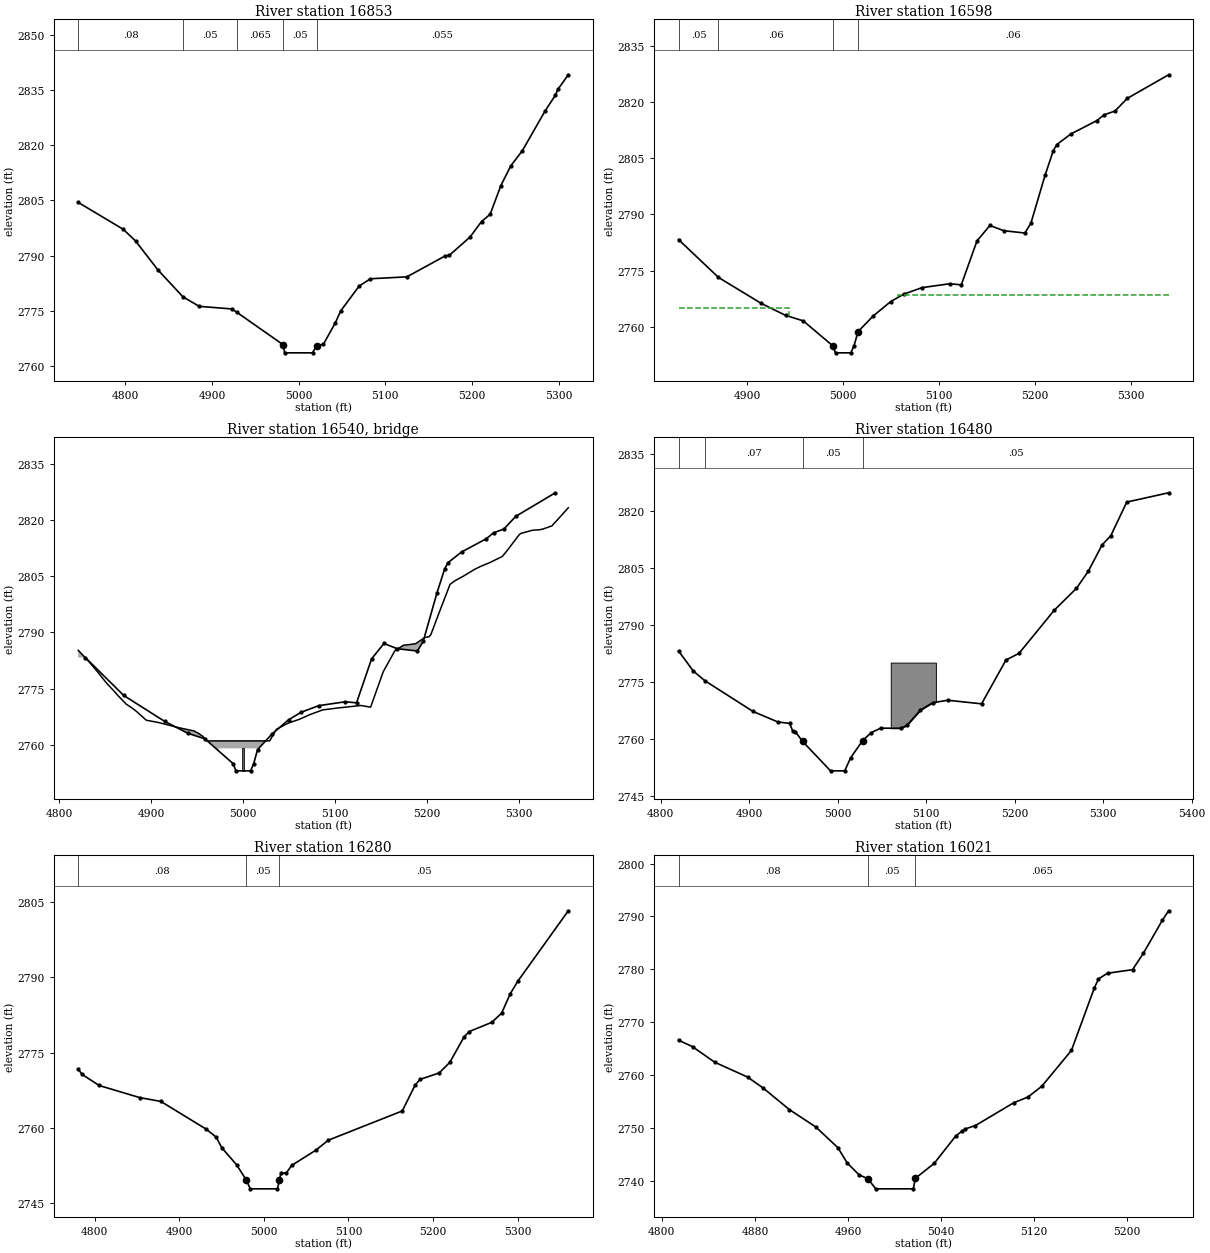
Type RM Length L Ch R = 1 ,16853   ,255,255,255
BEGIN DESCRIPTION:
Little_Rock_Crk_53
END DESCRIPTION:
XS GIS Cut Line= 2
      1062335.47       853020.94      1062057.04       853513.13
#Sta/Elev= 30
  4745.7 2804.42  4797.6 2797.13  4811.9 2793.94  4837.5 2786.14  4866.6 2778.78
  4885.3 2776.21  4922.8 2775.51  4928.8 2774.58  4982.2 2765.78  4983.9 2763.59
  5016.1 2763.59  5020.8 2765.55  5028.6 2765.92  5042.3  2771.7  5048.5 2774.94
  5069.9 2781.73  5082.9  2783.7    5125 2784.22    5169 2789.89  5174.1  2790.1
  5197.8 2795.02  5211.1 2799.24    5221  2801.2  5233.4    2809  5244.8 2814.33
  5258.2 2818.47  5284.6 2829.32  5296.3 2833.52  5299.2 2835.12  5311.2 2839.07
#Mann= 5 ,-1 , 0
  4745.7     .08       0  4866.6     .05       0  4928.8    .065       0
  4982.2     .05       0  5020.8    .055       0
Bank Sta=4982.2,5020.8
Exp/Cntr=0.5,0.3

Type RM Length L Ch R = 1 ,16598   ,118,118,118
BEGIN DESCRIPTION:
Little_Rock_Crk_52
END DESCRIPTION:
XS GIS Cut Line= 2
      1062094.76       852963.46      1061801.96         853382.
#Sta/Elev= 30
  4828.4 2783.26    4870 2773.15  4914.7 2766.19  4939.9 2763.02  4958.3 2761.55
 4989.01 2754.91    4992    2753    5008    2753 5011.28 2754.88  5015.5 2758.67
  5031.3 2762.86  5049.5 2766.69  5063.1 2768.68  5082.1 2770.42    5111 2771.46
  5123.1 2771.17  5139.5 2782.93  5152.9 2787.03  5167.4 2785.63  5189.3 2785.02
  5195.6  2787.6  5210.4 2800.44    5219 2807.03  5222.6 2808.64  5237.3 2811.48
  5264.3 2815.04  5272.1 2816.61  5283.3 2817.61  5296.1 2820.99  5339.2  2827.3
#Mann= 4 ,-1 , 0
  4828.4     .05       0    4870     .06       0 4989.01     .05       0
  5015.5     .06       0
#XS Ineff= 2 , 0
       0    4943    2765    5057       0 2768.54
Permanent Ineff=
       F       F
Bank Sta=4989.01,5015.5
Exp/Cntr=0.5,0.3

Type RM Length L Ch R = 3 ,16540   ,,,
BEGIN DESCRIPTION:
Little_Rock_Crk_51
Structure ID: Rock Creek Drive
Approximate Survey Structure
END DESCRIPTION:
Bridge Culvert--1,0,-1,-1, 0
Deck Dist Width WeirC Skew NumUp NumDn MinLoCord MaxHiCord MaxSubmerge Is_Ogee
50,14,3,0, 60, 60, , , , 0, 1,1,,
  4820.6  4830.9  4835.7  4841.1  4851.2  4861.8  4863.3  4872.9  4878.6  4883.9
  4893.9  4894.9  4907.2  4930.5  4946.9  4948.4  4950.7    4956  4960.7    4973
    4973    5027    5027  5028.7  5034.8  5035.9  5036.6  5048.3  5060.7  5072.9
  5086.3  5103.5  5127.8  5138.4  5152.2    5165  5174.4  5178.1  5187.4  5197.3
  5201.8  5203.8  5214.7  5224.8  5230.5  5238.6  5251.8  5258.3  5268.3  5281.7
  5286.7  5299.9  5301.6  5314.4  5322.4    5326  5335.7  5337.7  5340.1  5353.3
 2785.22 2782.53 2781.18 2779.61  2776.5  2773.7 2773.23  2770.8 2769.87 2768.88
 2766.67 2766.51 2765.95  2764.5 2763.63 2763.36 2763.12 2762.22    2761    2761
    2761    2761    2761    2761 2763.61 2764.04 2764.17  2765.7 2766.75 2768.07
 2769.28 2769.82 2770.46 2770.02 2779.51 2785.18 2786.59 2786.65 2786.98 2788.63
 2788.81 2789.34 2796.43 2802.85 2803.85 2804.93 2806.89 2807.66 2808.68 2810.31
 2811.82 2816.08 2816.44 2817.29 2817.43 2817.63 2818.48 2819.11 2819.69  2823.3
  2732.7  2732.7  2732.7  2732.7  2732.7  2732.7  2732.7  2732.7  2732.7  2732.7
  2732.7  2732.7  2732.7  2732.7  2732.7  2732.7  2732.7  2732.7  2732.7  2732.7
    2759    2759  2732.7  2732.7  2732.7  2732.7  2732.7  2732.7  2732.7  2732.7
  2732.7  2732.7  2732.7  2732.7  2732.7  2732.7  2732.7  2732.7  2732.7  2732.7
  2732.7  2732.7  2732.7  2732.7  2732.7  2732.7  2732.7  2732.7  2732.7  2732.7
  2732.7  2732.7  2732.7  2732.7  2732.7  2732.7  2732.7  2732.7  2732.7  2732.7
  4820.6  4830.9  4835.7  4841.1  4851.2  4861.8  4863.3  4872.9  4878.6  4883.9
  4893.9  4894.9  4907.2  4930.5  4946.9  4948.4  4950.7    4956  4960.7    4973
    4973    5027    5027  5028.7  5034.8  5035.9  5036.6  5048.3  5060.7  5072.9
  5086.3  5103.5  5127.8  5138.4  5152.2    5165  5174.4  5178.1  5187.4  5197.3
  5201.8  5203.8  5214.7  5224.8  5230.5  5238.6  5251.8  5258.3  5268.3  5281.7
  5286.7  5299.9  5301.6  5314.4  5322.4    5326  5335.7  5337.7  5340.1  5353.3
 2785.22 2782.53 2781.18 2779.61  2776.5  2773.7 2773.23  2770.8 2769.87 2768.88
 2766.67 2766.51 2765.95  2764.5 2763.63 2763.36 2763.12 2762.22    2761    2761
    2761    2761    2761    2761 2763.61 2764.04 2764.17  2765.7 2766.75 2768.07
 2769.28 2769.82 2770.46 2770.02 2779.51 2785.18 2786.59 2786.65 2786.98 2788.63
 2788.81 2789.34 2796.43 2802.85 2803.85 2804.93 2806.89 2807.66 2808.68 2810.31
 2811.82 2816.08 2816.44 2817.29 2817.43 2817.63 2818.48 2819.11 2819.69  2823.3
  2732.7  2732.7  2732.7  2732.7  2732.7  2732.7  2732.7  2732.7  2732.7  2732.7
  2732.7  2732.7  2732.7  2732.7  2732.7  2732.7  2732.7  2732.7  2732.7  2732.7
    2759    2759  2732.7  2732.7  2732.7  2732.7  2732.7  2732.7  2732.7  2732.7
  2732.7  2732.7  2732.7  2732.7  2732.7  2732.7  2732.7  2732.7  2732.7  2732.7
  2732.7  2732.7  2732.7  2732.7  2732.7  2732.7  2732.7  2732.7  2732.7  2732.7
  2732.7  2732.7  2732.7  2732.7  2732.7  2732.7  2732.7  2732.7  2732.7  2732.7
Pier Skew, UpSta & Num, DnSta & Num=  ,5000, 2 ,5000, 2 , 0 , 0 , 0 ,0,0
       2       2
  2752.7  2759.5
       2       2
 2752.45  2759.5
BR Coef= 1 , 1 , 0 ,1.25, 0 ,,,0.8,0,2,0,
WSPro=,,,, 1 ,,,, 0 ,,,, 0 ,,,,-1 ,-1 ,-1 , 0 , 0 , 0 , 0 , 0
BC Design=,, 0 ,, 0 ,,,,,,
BC HTab HWMax=2827.3

Type RM Length L Ch R = 1 ,16480   ,200,200,200
BEGIN DESCRIPTION:
Little_Rock_Crk_50
END DESCRIPTION:
XS GIS Cut Line= 2
      1062012.13       852873.65      1061701.37       853331.71
#Sta/Elev= 30
  4820.3 2783.05    4837 2777.78  4849.9 2775.25 4904.33 2767.15 4932.54 2764.36
 4945.74    2764  4949.2 2762.03  4952.2 2761.81  4960.4 2759.25    4992  2751.5
    5008  2751.5  5014.7 2754.94  5028.2 2759.45  5037.9 2761.55  5048.6 2762.74
  5071.6 2762.71  5078.2 2763.46  5093.4 2767.47  5107.3 2769.43  5124.3 2770.09
  5162.6 2769.15  5190.2 2780.69  5204.9 2782.44  5244.7 2793.79  5269.8 2799.57
  5283.2 2804.07  5298.8 2811.02  5308.5 2813.37  5326.6 2822.27  5373.9 2824.72
#Mann= 4 ,-1 , 0
  4820.3     .05       0  4849.9     .07       0  4960.4     .05       0
  5028.2     .05       0
#XS Ineff= 2 , 0
       0    4953    2761    5047       0    2761
Permanent Ineff=
       F       F
#Block Obstruct= 1 ,-1
    5060    5111    2780
Bank Sta=4960.4,5028.2
Exp/Cntr=0.5,0.3

Type RM Length L Ch R = 1 ,16280   ,259,259,259
BEGIN DESCRIPTION:
Little_Rock_Crk_49
END DESCRIPTION:
XS GIS Cut Line= 2
      1061888.32       852743.38      1061514.23       853185.49
#Sta/Elev= 30
  4780.6 2771.74    4785 2770.71  4805.3 2768.48  4853.5 2766.06  4878.2 2765.31
  4931.6 2759.81  4943.6 2758.21  4950.1 2756.12  4967.9 2752.66 4979.47 2749.58
  4983.9  2747.9  5016.1  2747.9 5018.33 2749.62  5020.2 2751.12  5026.4 2751.02
  5032.8 2752.56  5061.2 2755.57  5076.2 2757.59  5163.6 2763.41  5178.7 2768.55
  5184.5 2769.68  5207.3 2770.99  5219.7 2773.07  5236.5 2778.12  5242.6 2779.21
  5269.3 2781.05    5281 2782.88  5291.1 2786.72  5300.1 2789.24  5359.8 2803.27
#Mann= 3 , 0 , 0
  4780.6     .08       0 4979.47     .05       0 5018.33     .05       0
Bank Sta=4979.47,5018.33
Exp/Cntr=0.3,0.1

Type RM Length L Ch R = 1 ,16021   ,459,459,459
BEGIN DESCRIPTION:
Little_Rock_Crk_48
END DESCRIPTION:
XS GIS Cut Line= 2
      1061616.25       852666.86      1061364.02       853004.12
#Sta/Elev= 30
  4814.4 2766.63  4826.4  2765.4  4845.5 2762.46  4873.8 2759.65  4887.2 2757.57
  4909.7  2753.5  4932.4 2750.22  4951.3 2746.32  4959.3 2743.43  4969.6 2741.16
  4976.9 2740.48  4983.9 2738.54  5016.1 2738.54  5017.9 2740.53  5034.1 2743.36
  5052.7 2748.56  5057.7 2749.39  5060.8 2749.86  5069.5  2750.5  5102.6 2754.83
  5114.6 2755.88  5126.5 2757.92    5152  2764.7  5171.6 2776.46  5175.2  2778.2
    5183 2779.28  5204.5 2779.95  5213.8 2783.05  5230.2 2789.32  5235.5 2791.08
#Mann= 3 ,-1 , 0
  4814.4     .08       0  4976.9     .05       0  5017.9    .065       0
Bank Sta=4976.9,5017.9
Exp/Cntr=0.3,0.1