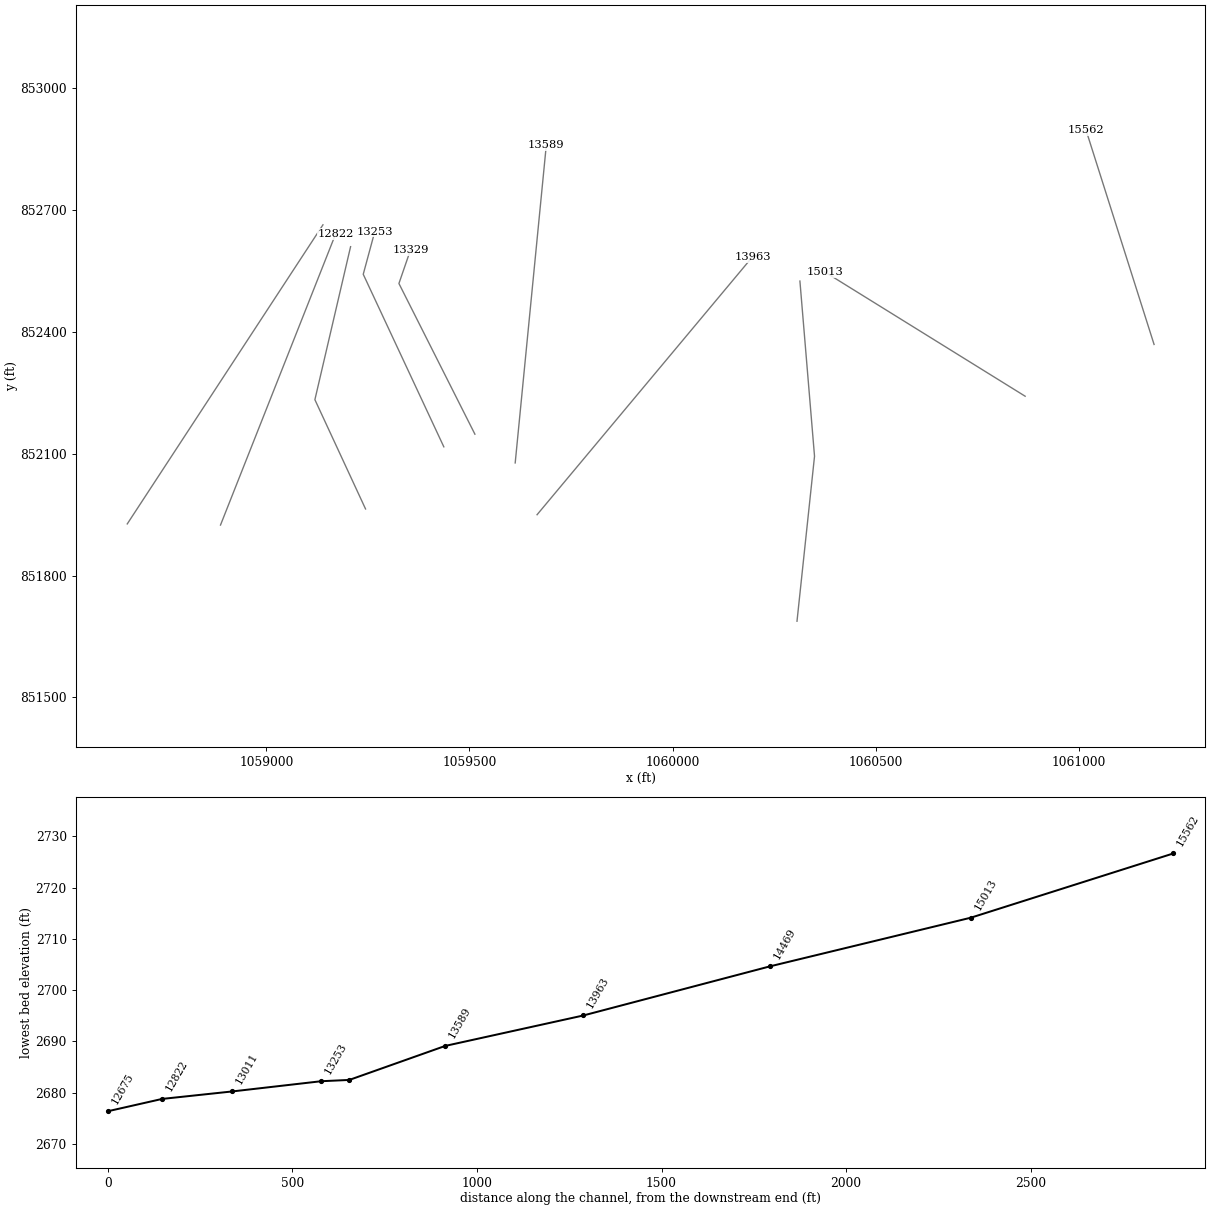
HEC-RAS study lds_little_rock_crk.prj: Little Rock Creek Limited Detail Study

--- lds_little_rock_crk.g01 (geometry) --- (continued)

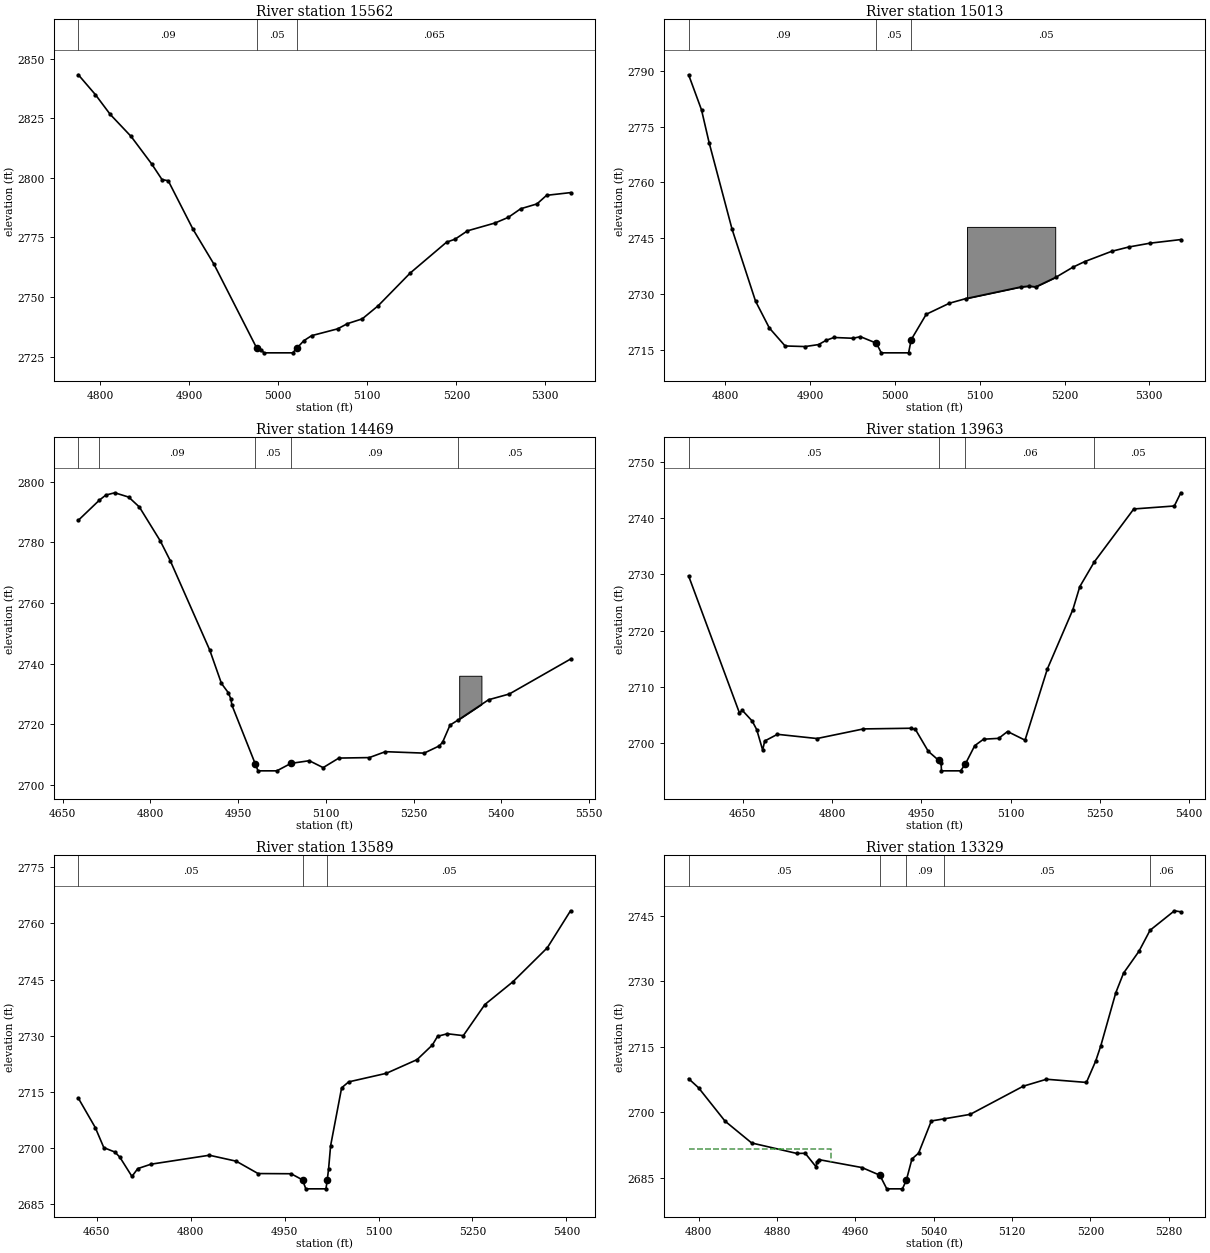
Type RM Length L Ch R = 1 ,15562   ,549,549,549
BEGIN DESCRIPTION:
Little_Rock_Crk_47
END DESCRIPTION:
XS GIS Cut Line= 2
      1061185.48       852369.29      1061018.27       852896.42
#Sta/Elev= 30
  4775.3 2843.18  4794.5 2834.85  4811.1 2826.59  4834.6 2817.33  4857.8 2805.76
  4869.3 2799.27  4876.3 2798.77  4904.2 2778.39  4927.6 2763.85  4975.7 2728.66
  4980.3 2728.04  4983.9 2726.65  5016.1 2726.65 5020.53 2728.49  5028.7 2731.75
  5037.4 2733.85  5066.6  2736.7  5077.7 2738.89  5094.3 2740.89  5112.2 2746.39
  5148.1 2760.07  5189.1 2773.05  5198.5 2774.26  5212.5 2777.78  5243.6 2781.08
  5258.4 2783.43  5272.3 2787.03  5290.6 2789.06  5301.4 2792.66  5328.3  2793.8
#Mann= 3 , 0 , 0
  4775.3     .09       0  4975.7     .05       0 5020.53    .065       0
Bank Sta=4975.7,5020.53
Exp/Cntr=0.3,0.1

Type RM Length L Ch R = 1 ,15013   ,544,544,544
BEGIN DESCRIPTION:
Little_Rock_Crk_46
END DESCRIPTION:
XS GIS Cut Line= 2
      1060868.06       852241.76      1060374.94       852547.83
#Sta/Elev= 30
  4756.7 2788.92  4771.9 2779.48  4780.9 2770.64  4807.9  2747.4  4835.6 2728.03
  4851.9  2720.8  4870.5 2715.97  4894.1 2715.81  4909.9 2716.34  4918.9 2717.49
  4928.1 2718.25  4950.6 2718.04  4959.3 2718.47  4978.1 2716.72  4983.9 2714.12
  5016.1 2714.12  5019.2 2717.67  5036.9 2724.49  5064.3 2727.47  5083.3 2728.69
  5148.6 2731.85    5158 2732.06  5166.1 2731.87  5189.7 2734.44  5209.8 2737.15
  5223.6 2738.65  5255.7 2741.44  5275.7 2742.59  5300.8 2743.62  5337.1 2744.59
#Mann= 3 ,-1 , 0
  4756.7     .09       0  4978.1     .05       0  5019.2     .05       0
#Block Obstruct= 1 ,-1
    5085    5189    2748
Bank Sta=4978.1,5019.2
Exp/Cntr=0.3,0.1

Type RM Length L Ch R = 1 ,14469   ,506,506,506
BEGIN DESCRIPTION:
little_rock_crk_a11
END DESCRIPTION:
XS GIS Cut Line= 3
      1060306.37       851687.45      1060349.53       852093.85
      1060313.56       852525.43
#Sta/Elev= 30
  4676.6 2787.28  4712.6 2793.92  4723.7  2795.6  4738.9 2796.35  4762.7 2794.93
    4781 2791.65  4816.7 2780.49  4833.7 2773.99  4901.4 2744.44  4921.4 2733.45
  4933.1 2730.41  4937.6 2728.29  4939.1 2726.39 4979.11 2706.98  4983.9 2704.64
  5016.1 2704.64  5040.2  2707.1  5071.6 2707.98  5095.3  2705.7  5122.2 2708.85
  5174.2 2709.01  5201.7 2710.96    5268 2710.48  5294.2 2712.89  5299.7 2714.13
  5312.3 2719.72  5326.5 2721.45  5378.3 2728.09  5413.8 2729.99  5518.4  2741.5
#Mann= 5 ,-1 , 0
  4676.6     .05       0  4712.6     .09       0 4979.11     .05       0
  5040.2     .09       0  5326.5     .05       0
#Block Obstruct= 1 ,-1
    5328    5366    2736
Bank Sta=4979.11,5040.2
Exp/Cntr=0.3,0.1

Type RM Length L Ch R = 1 ,13963   ,374,374,374
BEGIN DESCRIPTION:
Little_Rock_Crk_45
END DESCRIPTION:
XS GIS Cut Line= 2
      1059666.43       851949.85      1060196.39       852584.68
#Sta/Elev= 30
  4559.1 2729.74  4644.5 2705.36  4649.3 2705.83  4665.9 2703.92  4673.5  2702.4
  4683.5 2698.75  4686.9 2700.37  4708.3 2701.56  4774.8 2700.81  4852.8 2702.52
  4932.9 2702.64  4940.2 2702.42  4961.7 2698.54  4979.5  2696.9  4983.2 2696.54
  4983.9 2695.06  5016.1 2695.06  5024.1 2696.29  5039.8 2699.54  5054.6 2700.69
    5080 2700.84  5094.9 2702.06  5124.3 2700.52  5161.8 2713.19  5204.6 2723.73
  5216.3 2727.84  5240.6 2732.23    5307 2741.66  5375.1 2742.19    5386 2744.54
#Mann= 4 ,-1 , 0
  4559.1     .05       0  4979.5     .05       0  5024.1     .06       0
  5240.6     .05       0
Bank Sta=4979.5,5024.1
Exp/Cntr=0.3,0.1

Type RM Length L Ch R = 1 ,13589   ,260,260,260
BEGIN DESCRIPTION:
Little_Rock_Crk_44
END DESCRIPTION:
XS GIS Cut Line= 2
      1059612.58       852077.38       1059689.1       852859.58
#Sta/Elev= 30
  4620.7 2713.33  4647.7  2705.5  4661.4 2700.13  4679.2 2698.94    4687 2697.57
  4706.3 2692.44  4715.6 2694.53  4736.7 2695.71  4829.9  2698.1  4872.8 2696.51
  4907.7 2693.21  4960.4 2693.16  4978.7 2691.52  4983.9 2689.13  5016.1 2689.13
 5018.06 2691.38  5020.3 2694.49  5023.5 2700.62  5041.1 2716.09  5052.3 2717.68
  5112.5 2719.97  5161.6 2723.63    5186 2727.53  5194.3 2729.85  5209.9 2730.53
  5235.4 2730.03  5269.8 2738.33  5314.6 2744.41  5369.5 2753.48  5406.6 2763.36
#Mann= 3 , 0 , 0
  4620.7     .05       0  4978.7     .05       0 5018.06     .05       0
Bank Sta=4978.7,5018.06
Exp/Cntr=0.5,0.3

Type RM Length L Ch R = 1 ,13329   ,76,76,76
BEGIN DESCRIPTION:
Little_Rock_Crk_43
END DESCRIPTION:
XS GIS Cut Line= 3
      1059513.39       852148.23      1059326.34       852519.49
      1059354.68       852601.68
#Sta/Elev= 30
  4789.6 2707.72  4799.7 2705.65  4826.8    2698    4854    2693    4900 2690.61
  4908.7 2690.64  4919.9  2687.5  4920.5 2688.65  4922.4  2689.2  4966.7 2687.37
  4984.9 2685.62    4992  2682.5    5008  2682.5    5012  2684.5  5017.7 2689.34
  5024.5 2690.68  5037.5 2698.04  5050.7 2698.53  5077.2 2699.55  5131.4    2706
  5155.1 2707.59  5195.9 2706.86  5205.4 2711.77  5210.6 2715.26  5225.9  2727.4
  5233.8 2731.88  5249.6  2736.9  5260.9  2741.7  5285.8 2746.16  5292.3 2745.92
#Mann= 5 ,-1 , 0
  4789.6     .05       0  4984.9     .05       0    5012     .09       0
  5050.7     .05       0  5260.9     .06       0
#XS Ineff= 2 , 0
       0  4935.5 2691.72  5064.5       0 2696.28
Permanent Ineff=
       F       F
Bank Sta=4984.9,5012
Exp/Cntr=0.5,0.3

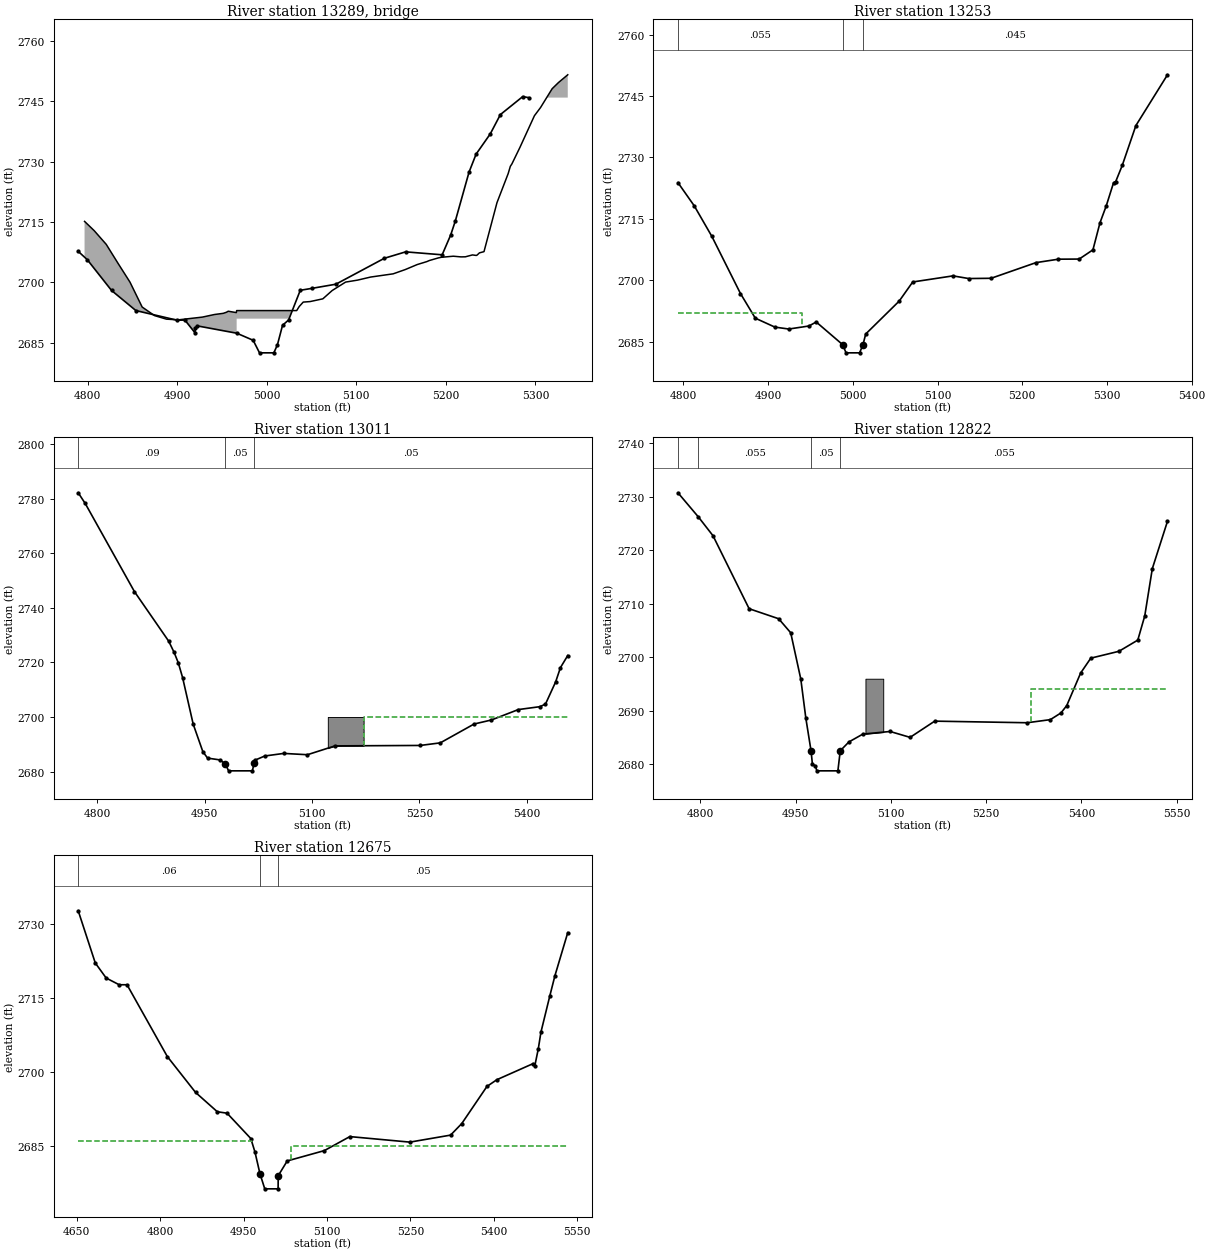
Type RM Length L Ch R = 3 ,13289   ,,,
BEGIN DESCRIPTION:
Little_Rock_Crk_42
Structure ID: Fork Mountain Road bridge
Approximate Survey Structure
END DESCRIPTION:
Bridge Culvert--1,0,-1,-1, 0
Deck Dist Width WeirC Skew NumUp NumDn MinLoCord MaxHiCord MaxSubmerge Is_Ogee
31,18,3,0, 52, 52, , , , 0, 1,1,,
  4796.7  4807.4  4820.9  4834.2  4847.4    4861  4874.7  4888.1  4901.5  4928.2
  4941.6  4951.6    4955  4957.1  4966.1  4966.5  4966.5  5033.5  5033.5  5036.3
  5040.8  5048.5  5062.7  5073.1  5088.1  5101.5    5116  5141.2  5154.7  5168.1
  5178.8  5181.5  5191.5  5194.9  5208.3  5216.9  5221.8  5229.7    5234    5235
  5237.5  5242.6  5257.1  5269.6    5272  5273.8  5282.7  5298.9  5305.7  5318.7
  5325.8  5336.1
 2715.16 2712.87 2709.45 2704.69 2700.07 2693.88 2691.76 2690.87  2690.7 2691.38
 2692.02 2692.32 2692.58 2692.84  2692.5    2693    2693    2693    2693    2694
 2695.11 2695.24 2695.92 2697.98 2700.08 2700.57 2701.33 2702.13 2703.19 2704.44
 2705.17 2705.43 2706.08 2706.24 2706.51 2706.34 2706.36 2706.83  2706.7 2706.81
 2707.34 2707.64 2719.82 2727.04 2728.84 2729.46 2733.54 2741.42 2743.44 2748.13
 2749.67 2751.59
  2662.5  2662.5  2662.5  2662.5  2662.5  2662.5  2662.5  2662.5  2662.5  2662.5
  2662.5  2662.5  2662.5  2662.5  2662.5  2662.5    2691    2691  2662.5  2662.5
  2662.5  2662.5  2662.5  2662.5  2662.5  2662.5  2662.5  2662.5  2662.5  2662.5
  2662.5  2662.5  2662.5  2662.5  2662.5  2662.5  2662.5  2662.5  2662.5  2662.5
  2662.5  2662.5  2662.5  2662.5  2662.5  2662.5  2662.5  2662.5  2662.5  2662.5
  2662.5  2662.5
  4796.7  4807.4  4820.9  4834.2  4847.4    4861  4874.7  4888.1  4901.5  4928.2
  4941.6  4951.6    4955  4957.1  4966.1  4966.5  4966.5  5033.5  5033.5  5036.3
  5040.8  5048.5  5062.7  5073.1  5088.1  5101.5    5116  5141.2  5154.7  5168.1
  5178.8  5181.5  5191.5  5194.9  5208.3  5216.9  5221.8  5229.7    5234    5235
  5237.5  5242.6  5257.1  5269.6    5272  5273.8  5282.7  5298.9  5305.7  5318.7
  5325.8  5336.1
 2715.16 2712.87 2709.45 2704.69 2700.07 2693.88 2691.76 2690.87  2690.7 2691.38
 2692.02 2692.32 2692.58 2692.84  2692.5    2693    2693    2693    2693    2694
 2695.11 2695.24 2695.92 2697.98 2700.08 2700.57 2701.33 2702.13 2703.19 2704.44
 2705.17 2705.43 2706.08 2706.24 2706.51 2706.34 2706.36 2706.83  2706.7 2706.81
 2707.34 2707.64 2719.82 2727.04 2728.84 2729.46 2733.54 2741.42 2743.44 2748.13
 2749.67 2751.59
  2662.5  2662.5  2662.5  2662.5  2662.5  2662.5  2662.5  2662.5  2662.5  2662.5
  2662.5  2662.5  2662.5  2662.5  2662.5  2662.5    2691    2691  2662.5  2662.5
  2662.5  2662.5  2662.5  2662.5  2662.5  2662.5  2662.5  2662.5  2662.5  2662.5
  2662.5  2662.5  2662.5  2662.5  2662.5  2662.5  2662.5  2662.5  2662.5  2662.5
  2662.5  2662.5  2662.5  2662.5  2662.5  2662.5  2662.5  2662.5  2662.5  2662.5
  2662.5  2662.5
BR Coef= 1 , 1 , 0 ,1.25, 0 ,,,0.8,0,2,0,
WSPro=,,,, 1 ,,,, 0 ,,,, 0 ,,,,-1 ,-1 ,-1 , 0 , 0 , 0 , 0 , 0
BC Design=,, 0 ,, 0 ,,,,,,
BC HTab HWMax=2746.16

Type RM Length L Ch R = 1 ,13253   ,242,242,242
BEGIN DESCRIPTION:
Little_Rock_Crk_41
END DESCRIPTION:
XS GIS Cut Line= 3
      1059436.87       852117.06      1059238.48       852542.17
      1059266.83       852647.03
#Sta/Elev= 30
  4793.6 2723.85  4812.8 2718.19  4833.6 2710.72  4867.4 2696.74  4884.9 2690.72
    4908 2688.54  4924.4 2688.07  4948.2 2688.81  4956.8 2689.79    4988 2684.25
    4992 2682.25    5008 2682.25    5012 2684.25  5015.2 2686.85  5054.7 2694.89
  5070.7 2699.57  5118.2 2701.06  5136.8 2700.41  5163.2 2700.47  5216.2  2704.3
  5242.7 2705.14  5267.2 2705.17  5283.4 2707.43  5291.7 2714.03  5299.1 2718.16
  5307.7 2723.81  5310.3 2724.12    5318 2728.06  5334.1  2737.8  5371.4 2750.21
#Mann= 3 ,-1 , 0
  4793.6    .055       0    4988     .05       0    5012    .045       0
#XS Ineff= 2 , 0
       0  4939.5 2691.92  5060.5       0 2695.85
Permanent Ineff=
       F       F
Bank Sta=4988,5012
Exp/Cntr=0.5,0.3

Type RM Length L Ch R = 1 ,13011   ,189,189,189
BEGIN DESCRIPTION:
Little_Rock_Crk_40
END DESCRIPTION:
XS GIS Cut Line= 3
      1059244.15       851964.02      1059119.45       852233.25
      1059207.31       852610.18
#Sta/Elev= 30
  4773.4 2782.22  4783.2  2778.3  4851.9 2745.99  4899.8 2727.79  4907.4 2723.65
  4913.2 2719.85  4919.2 2714.44    4934 2697.37  4947.5 2687.27  4954.1 2684.92
  4971.3 2684.26 4978.96 2682.79  4983.4 2680.25  5016.6 2680.25 5019.12 2683.01
    5020 2684.13  5033.9 2685.69  5060.5 2686.64  5093.5 2686.16    5132  2689.4
  5251.1 2689.56  5279.1 2690.51  5326.3 2697.42  5350.6 2698.91  5388.1 2702.72
  5418.2 2703.78    5426 2704.73  5440.2 2712.87  5446.9 2718.11  5457.1 2722.54
#Mann= 3 , 0 , 0
  4773.4     .09       0 4978.96     .05       0 5019.12     .05       0
#XS Ineff= 2 , 0
       0                    5172       0    2700
Permanent Ineff=
       F       F
#Block Obstruct= 1 ,-1
    5122    5172    2700
Bank Sta=4978.96,5019.12
Exp/Cntr=0.3,0.1

Type RM Length L Ch R = 1 ,12822   ,147,147,147
BEGIN DESCRIPTION:
Little_Rock_Crk_39
END DESCRIPTION:
XS GIS Cut Line= 2
      1058887.06       851924.34      1059170.47       852641.36
#Sta/Elev= 30
  4764.7 2730.72    4797 2726.19  4819.9  2722.7  4876.8 2709.07  4923.3  2707.2
  4942.3 2704.58  4958.2 2695.92  4966.1 2688.64  4974.3 2682.55  4976.5 2680.02
  4981.2 2679.73  4983.4  2678.8  5016.6  2678.8  5020.3 2682.55    5034  2684.2
  5055.9 2685.66  5098.8 2686.15  5130.3 2685.05  5169.1 2688.08  5314.6 2687.78
  5351.2 2688.36  5367.9 2689.61    5377 2690.98  5398.9 2697.06  5414.9 2699.84
  5459.2 2701.12  5488.9 2703.21  5499.9 2707.74  5511.8 2716.56  5535.7 2725.41
#Mann= 4 ,-1 , 0
  4764.7     .08       0    4797    .055       0  4974.3     .05       0
  5020.3    .055       0
#XS Ineff= 2 , 0
       0                    5320       0    2694
Permanent Ineff=
       F       F
#Block Obstruct= 1 ,-1
    5060    5088    2696
Bank Sta=4974.3,5020.3
Exp/Cntr=0.5,0.3

Type RM Length L Ch R = 1 ,12675   ,58,58,58
BEGIN DESCRIPTION:
Little_Rock_Crk_38
END DESCRIPTION:
XS GIS Cut Line= 2
       1058657.5       851927.18      1059139.29       852664.03
#Sta/Elev= 30
  4652.5 2732.71  4683.2 2722.14  4702.8 2719.09  4726.2 2717.73  4740.3 2717.73
  4812.7  2703.2  4863.6 2695.92  4902.7 2692.01  4920.2 2691.72  4962.9 2686.59
  4970.4 2683.85  4979.3 2679.49    4988  2676.4    5012  2676.4  5012.2 2679.06
  5028.4 2682.05  5095.1 2684.14    5141 2686.98    5249 2685.86  5322.2 2687.28
  5342.3 2689.62  5387.6 2697.14  5405.4  2698.5  5470.8 2701.77  5473.7 2701.33
  5479.9 2704.74  5484.7 2708.14  5500.6 2715.45  5509.8 2719.55  5532.9 2728.28
#Mann= 3 , 0 , 0
  4652.5     .06       0  4979.3    .045       0  5012.2     .05       0
#XS Ineff= 2 , 0
       0    4965    2686    5035       0    2685
Permanent Ineff=
       F       F
Bank Sta=4979.3,5012.2
Exp/Cntr=0.5,0.3