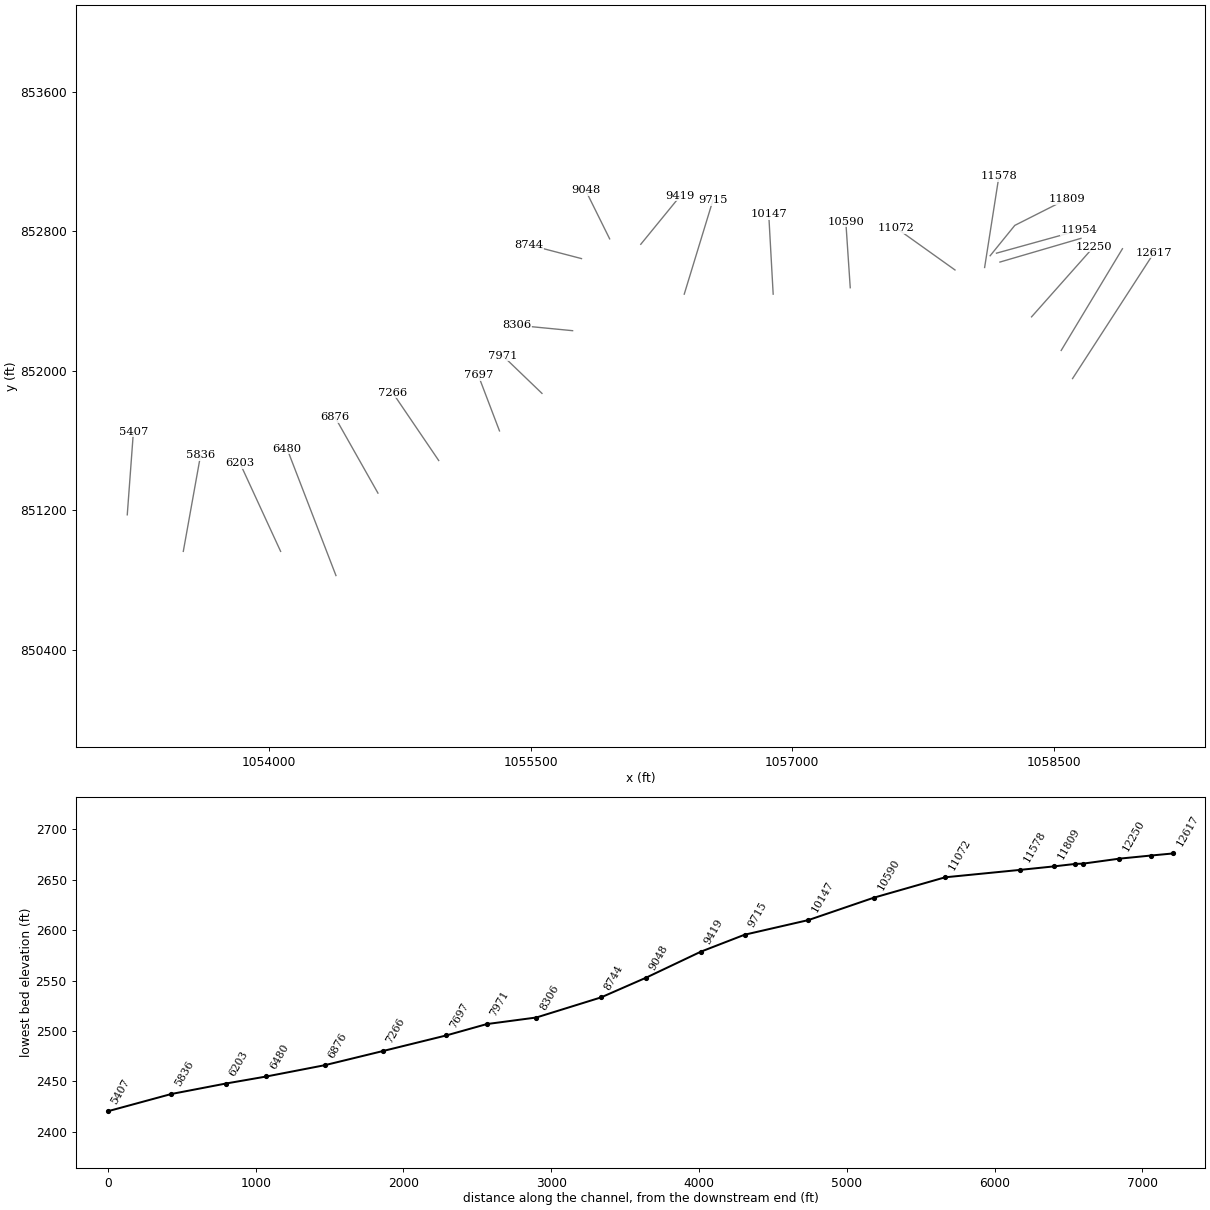
HEC-RAS study lds_little_rock_crk.prj: Little Rock Creek Limited Detail Study

--- lds_little_rock_crk.g01 (geometry) --- (continued)

Type RM Length L Ch R = 3 ,12648   ,,,
BEGIN DESCRIPTION:
Little_Rock_Crk_37
Structure ID: Lee Gouge Road bridge
Approximate Survey Structure
END DESCRIPTION:
Bridge Culvert--1,0,-1,-1, 0
Deck Dist Width WeirC Skew NumUp NumDn MinLoCord MaxHiCord MaxSubmerge Is_Ogee
18,18,3,0, 60, 60, , , , 0, 1,1,,
  4649.9  4658.1  4659.7  4660.9    4684  4688.3  4690.7    4704    4723  4726.5
  4743.4  4778.1  4784.9  4789.1  4791.6  4815.8  4820.5  4844.2  4858.9  4884.4
  4890.4  4908.3  4916.6    4924  4929.3    4934    4985    4985    5015    5015
  5322.4  5335.2  5340.3  5351.1  5360.9  5369.4  5373.2  5376.6  5379.9  5389.3
    5409  5417.5  5422.7  5433.6  5439.1  5442.9  5449.3  5464.8  5469.6  5485.9
  5487.6  5490.5  5492.9  5496.1    5497  5499.8  5501.6  5505.5  5508.9  5520.1
 2731.59 2730.44  2730.5 2730.32 2721.97 2720.84  2720.4 2719.02 2717.91 2718.02
 2716.52    2709 2707.12 2706.22 2705.95  2701.6 2701.39 2697.92 2696.47 2692.29
 2691.72 2690.41 2689.43 2689.01 2688.48    2686    2686    2686    2685    2685
    2688 2690.38 2691.45 2693.38  2694.8 2695.88 2696.56 2696.91 2697.21 2697.78
 2698.15 2698.61 2698.76 2699.66 2700.01 2700.09 2700.54 2701.94 2704.21 2713.88
 2714.53 2714.78 2715.64 2716.52 2716.95 2717.88 2718.88 2720.11 2721.53 2725.73
  2654.4  2654.4  2654.4  2654.4  2654.4  2654.4  2654.4  2654.4  2654.4  2654.4
  2654.4  2654.4  2654.4  2654.4  2654.4  2654.4  2654.4  2654.4  2654.4  2654.4
  2654.4  2654.4  2654.4  2654.4  2654.4  2654.4  2654.4    2685    2684  2654.4
  2654.4  2654.4  2654.4  2654.4  2654.4  2654.4  2654.4  2654.4  2654.4  2654.4
  2654.4  2654.4  2654.4  2654.4  2654.4  2654.4  2654.4  2654.4  2654.4  2654.4
  2654.4  2654.4  2654.4  2654.4  2654.4  2654.4  2654.4  2654.4  2654.4  2654.4
  4649.9  4658.1  4659.7  4660.9    4684  4688.3  4690.7    4704    4723  4726.5
  4743.4  4778.1  4784.9  4789.1  4791.6  4815.8  4820.5  4844.2  4858.9  4884.4
  4890.4  4908.3  4916.6    4924  4929.3    4934    4985    4985    5015    5015
  5322.4  5335.2  5340.3  5351.1  5360.9  5369.4  5373.2  5376.6  5379.9  5389.3
    5409  5417.5  5422.7  5433.6  5439.1  5442.9  5449.3  5464.8  5469.6  5485.9
  5487.6  5490.5  5492.9  5496.1    5497  5499.8  5501.6  5505.5  5508.9  5520.1
 2731.59 2730.44  2730.5 2730.32 2721.97 2720.84  2720.4 2719.02 2717.91 2718.02
 2716.52    2709 2707.12 2706.22 2705.95  2701.6 2701.39 2697.92 2696.47 2692.29
 2691.72 2690.41 2689.43 2689.01 2688.48    2686    2686    2686    2685    2685
    2688 2690.38 2691.45 2693.38  2694.8 2695.88 2696.56 2696.91 2697.21 2697.78
 2698.15 2698.61 2698.76 2699.66 2700.01 2700.09 2700.54 2701.94 2704.21 2713.88
 2714.53 2714.78 2715.64 2716.52 2716.95 2717.88 2718.88 2720.11 2721.53 2725.73
  2654.4  2654.4  2654.4  2654.4  2654.4  2654.4  2654.4  2654.4  2654.4  2654.4
  2654.4  2654.4  2654.4  2654.4  2654.4  2654.4  2654.4  2654.4  2654.4  2654.4
  2654.4  2654.4  2654.4  2654.4  2654.4  2654.4  2654.4    2685    2684  2654.4
  2654.4  2654.4  2654.4  2654.4  2654.4  2654.4  2654.4  2654.4  2654.4  2654.4
  2654.4  2654.4  2654.4  2654.4  2654.4  2654.4  2654.4  2654.4  2654.4  2654.4
  2654.4  2654.4  2654.4  2654.4  2654.4  2654.4  2654.4  2654.4  2654.4  2654.4
BR Coef= 1 , 1 , 0 ,1.25, 0 ,,,0.8,0,2,0,
WSPro=,,,, 1 ,,,, 0 ,,,, 0 ,,,,-1 ,-1 ,-1 , 0 , 0 , 0 , 0 , 0
BC Design=,, 0 ,, 0 ,,,,,,
BC HTab HWMax=2732.71

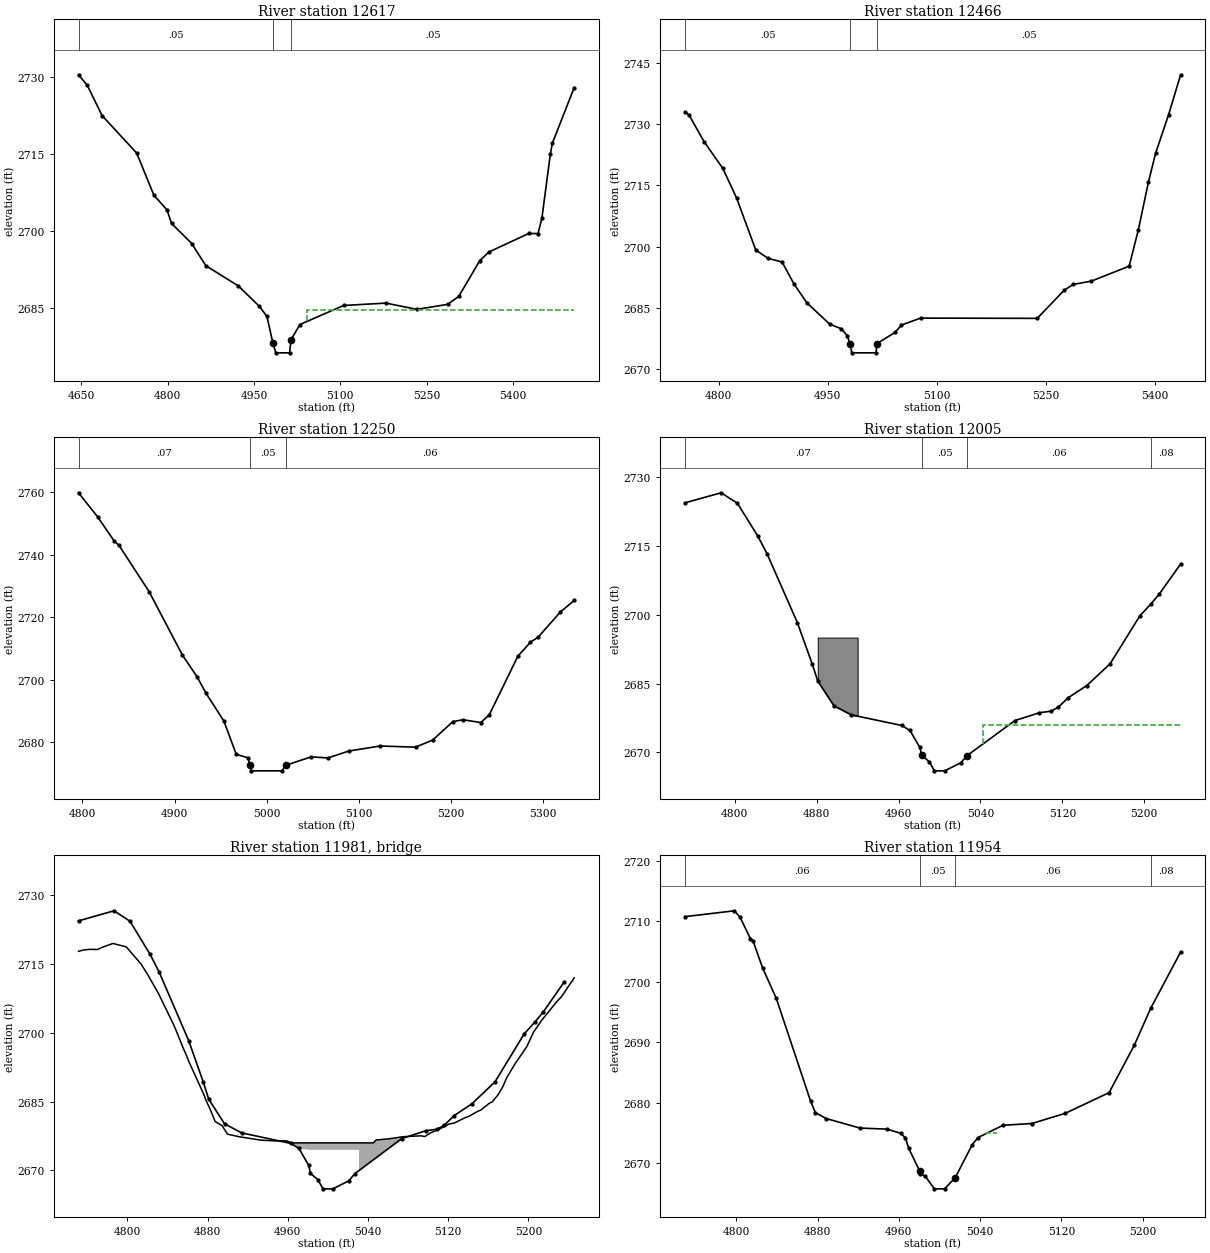
Type RM Length L Ch R = 1 ,12617   ,151,151,151
BEGIN DESCRIPTION:
Little_Rock_Crk_36
END DESCRIPTION:
XS GIS Cut Line= 2
      1058609.33       851955.52      1059076.94        852678.2
#Sta/Elev= 30
  4645.4 2730.45  4660.8 2728.36  4686.4 2722.47  4746.4 2715.17  4776.3 2706.93
    4799 2704.08  4806.9 2701.43    4842  2697.5  4866.5 2693.17  4923.2  2689.2
  4959.7 2685.21  4972.7 2683.25  4982.8 2678.13    4988 2676.15    5012 2676.15
  5014.3 2678.66  5029.9 2681.68  5105.8  2685.4  5179.3 2685.86    5233 2684.64
  5286.6 2685.62  5305.8 2687.18  5342.1 2694.12  5358.2 2695.85  5427.3 2699.46
  5443.5 2699.44  5450.2 2702.46  5464.8 2714.96  5468.4 2717.11  5506.2 2727.94
#Mann= 3 , 0 , 0
  4645.4     .05       0  4982.8    .045       0  5014.3     .05       0
#XS Ineff= 2 , 0
       0    4958  2684.5    5042       0  2684.5
Permanent Ineff=
       F       F
Bank Sta=4982.8,5014.3
Exp/Cntr=0.5,0.3

Type RM Length L Ch R = 1 ,12466   ,216,216,216
BEGIN DESCRIPTION:
Little_Rock_Crk_35
END DESCRIPTION:
XS GIS Cut Line= 2
      1058544.14       852117.06      1058895.57       852700.87
#Sta/Elev= 30
  4753.9 2732.94  4759.5 2732.19  4780.1 2725.71    4806 2719.14    4825 2711.86
  4851.2 2699.21  4868.4 2697.14  4887.4 2696.28  4903.9 2690.86  4921.7 2686.25
  4952.8 2681.09  4968.8 2679.94  4977.2 2678.25  4980.7 2676.17  4983.4 2674.06
  5016.6 2674.06  5017.7 2676.31  5042.7 2679.05  5051.6 2680.86    5078 2682.56
  5238.2 2682.49  5275.5  2689.4  5287.7 2690.78  5312.8 2691.61  5364.6 2695.25
  5377.1 2703.99  5391.1  2715.8    5401 2722.86  5418.9 2732.33  5435.4 2742.05
#Mann= 3 , 0 , 0
  4753.9     .05       0  4980.7     .05       0  5017.7     .05       0
Bank Sta=4980.7,5017.7
Exp/Cntr=0.3,0.1

Type RM Length L Ch R = 1 ,12250   ,245,245,245
BEGIN DESCRIPTION:
Little_Rock_Crk_34
END DESCRIPTION:
XS GIS Cut Line= 2
       1058374.1       852309.77      1058731.19       852712.21
#Sta/Elev= 30
  4795.8  2759.8  4816.8 2752.01  4834.5  2744.4  4839.8 2742.97  4872.4 2728.22
  4908.6 2707.91  4924.7  2700.9  4934.1 2695.78  4953.6 2686.84    4967 2676.21
  4979.7  2675.1 4981.97 2672.74  4983.4 2670.93  5016.6 2670.93 5020.55 2672.68
  5048.2 2675.39  5066.7 2675.06  5089.2 2677.26  5123.1 2678.87  5161.6  2678.5
  5180.2 2680.76  5202.2 2686.68  5213.2 2687.25  5232.5 2686.36  5241.7 2688.85
  5272.7 2707.58  5286.4 2712.05  5294.7 2713.66  5318.8 2721.68  5333.8  2725.4
#Mann= 3 , 0 , 0
  4795.8     .07       0 4981.97     .05       0 5020.55     .06       0
Bank Sta=4981.97,5020.55
Exp/Cntr=0.5,0.3

Type RM Length L Ch R = 1 ,12005   ,51,51,51
BEGIN DESCRIPTION:
Little_Rock_Crk_33
END DESCRIPTION:
XS GIS Cut Line= 2
      1058192.72       852624.35       1058657.5       852760.39
#Sta/Elev= 30
  4751.3 2724.32  4786.6 2726.51  4802.5 2724.24  4822.7    2717  4831.7 2713.15
  4861.2  2698.2  4875.7  2689.2  4881.1  2685.5  4896.9 2680.14  4913.9 2678.18
 4963.14 2675.87 4971.11 2674.78 4980.84  2671.1  4982.6 2669.35    4990    2668
    4995    2666    5005    2666  5020.8 2667.75 5027.02 2669.33 5073.76 2676.95
  5097.6 2678.64  5108.8 2678.98  5115.9 2679.82  5125.8 2681.92  5143.8 2684.54
  5166.7  2689.3  5195.8 2699.74  5206.4 2702.28  5214.9 2704.52  5235.6 2711.01
#Mann= 4 ,-1 , 0
  4751.3     .07       0  4982.6     .05       0 5027.02     .06       0
  5206.4     .08       0
#XS Ineff= 2 , 0
       0  4957.5    2676  5042.5       0    2676
Permanent Ineff=
       F       F
#Block Obstruct= 1 ,-1
    4881    4920    2695
Bank Sta=4982.6,5027.02
Exp/Cntr=0.5,0.3

Type RM Length L Ch R = 3 ,11981   ,,,
BEGIN DESCRIPTION:
Little_Rock_Crk_32
Structure ID: Rockdale road timber bridge 1
Approximate Survey Structure
END DESCRIPTION:
Bridge Culvert--1,0,-1,-1, 0
Deck Dist Width WeirC Skew NumUp NumDn MinLoCord MaxHiCord MaxSubmerge Is_Ogee
11.5,25,3,0, 56, 57, , , , 0, 1,1,,
  4751.2  4756.2  4762.6  4770.1  4775.5  4785.5  4798.8  4813.4  4819.8  4831.1
    4846  4848.2  4855.5  4858.6  4861.4  4876.6  4878.2  4881.8  4887.5  4894.5
  4899.8  4911.2  4933.3  4948.8  4958.6    4964    4969    4969    5031    5031
  5045.2    5048  5060.8  5074.6  5092.8  5096.6  5102.7  5110.1  5120.5  5126.4
  5135.2  5140.9  5149.5  5152.3  5160.9  5163.9  5169.7  5174.4  5178.4  5186.7
  5198.3    5205  5213.3  5228.4  5233.4  5245.6
 2717.69 2717.98 2718.12 2718.08 2718.61  2719.4 2718.66 2714.98 2712.77 2708.46
 2701.75 2700.65 2696.69 2695.15 2693.64 2686.34 2685.33 2683.66 2680.66 2679.74
 2677.89 2677.35 2676.59 2676.42 2676.46    2676    2676    2676    2676    2676
    2676 2676.63 2676.89 2677.34 2677.54 2677.38 2678.22 2678.88 2680.07 2680.35
 2681.32 2681.82 2682.87 2683.11 2684.61 2684.93 2686.48 2688.21 2690.23 2693.23
 2696.93 2700.07 2702.71 2706.77 2707.94 2711.93
    2646    2646    2646    2646    2646    2646    2646    2646    2646    2646
    2646    2646    2646    2646    2646    2646    2646    2646    2646    2646
    2646    2646    2646    2646    2646    2646    2646  2674.5  2674.5    2646
    2646    2646    2646    2646    2646    2646    2646    2646    2646    2646
    2646    2646    2646    2646    2646    2646    2646    2646    2646    2646
    2646    2646    2646    2646    2646    2646
  4751.2  4756.2  4762.6  4770.1  4775.5  4785.5  4798.8  4813.4  4819.8  4831.1
    4846  4848.2  4855.5  4858.6  4861.4  4876.6  4878.2  4881.8  4887.5  4894.5
  4899.8  4911.2  4933.3  4948.8  4958.6    4964  4964.5    4969    4969    5031
    5031  5045.2    5048  5060.8  5074.6  5092.8  5096.6  5102.7  5110.1  5120.5
  5126.4  5135.2  5140.9  5149.5  5152.3  5160.9  5163.9  5169.7  5174.4  5178.4
  5186.7  5198.3    5205  5213.3  5228.4  5233.4  5245.6
 2717.69 2717.98 2718.12 2718.08 2718.61  2719.4 2718.66 2714.98 2712.77 2708.46
 2701.75 2700.65 2696.69 2695.15 2693.64 2686.34 2685.33 2683.66 2680.66 2679.74
 2677.89 2677.35 2676.59 2676.42 2676.46  2676.2    2676    2676    2676    2676
    2676    2676 2676.63 2676.89 2677.34 2677.54 2677.38 2678.22 2678.88 2680.07
 2680.35 2681.32 2681.82 2682.87 2683.11 2684.61 2684.93 2686.48 2688.21 2690.23
 2693.23 2696.93 2700.07 2702.71 2706.77 2707.94 2711.93
    2646    2646    2646    2646    2646    2646    2646    2646    2646    2646
    2646    2646    2646    2646    2646    2646    2646    2646    2646    2646
    2646    2646    2646    2646    2646    2646    2646    2646  2674.5  2674.5
    2646    2646    2646    2646    2646    2646    2646    2646    2646    2646
    2646    2646    2646    2646    2646    2646    2646    2646    2646    2646
    2646    2646    2646    2646    2646    2646    2646
BR Coef= 1 , 0 , 0 ,1.25, 0 ,,,0.8,0,2,0,
WSPro=,,,, 1 ,,,, 0 ,,,, 0 ,,,,-1 ,-1 ,-1 , 0 , 0 , 0 , 0 , 0
BC Design=,, 0 ,, 0 ,,,,,,
BC HTab HWMax=2726.51

Type RM Length L Ch R = 1 ,11954   ,145,145,145
BEGIN DESCRIPTION:
Little_Rock_Crk_31
END DESCRIPTION:
XS GIS Cut Line= 2
      1058172.88       852675.37      1058643.33       852805.73
#Sta/Elev= 30
  4749.4 2710.75  4798.1 2711.72  4803.7 2710.64  4813.9 2707.08  4816.5 2706.71
  4825.8 2702.29  4839.3 2697.25  4873.2  2680.2  4877.8 2678.36  4888.5 2677.37
  4921.7  2675.8  4948.2 2675.62 4961.83 2674.94  4966.4 2674.18  4969.7 2672.46
 4980.52  2668.7  4981.3 2668.22    4986 2667.83    4995 2665.75    5005 2665.75
  5015.4 2667.57 5032.18 2673.01 5037.74 2674.21  5062.6 2676.26    5091 2676.55
  5123.8 2678.23  5167.1 2681.66  5191.8 2689.47    5208 2695.59  5237.5  2704.9
#Mann= 4 ,-1 , 0
  4749.4     .06       0 4980.52     .05       0  5015.4     .06       0
    5208     .08       0
#XS Ineff= 4 ,-1
  4749.4  4929.2    2675  4929.2  4954.5    2675  5045.5    5057    2675
    5057  5237.2    2675
Permanent Ineff=
       F       F       F       F
Bank Sta=4980.52,5015.4
Exp/Cntr=0.5,0.3

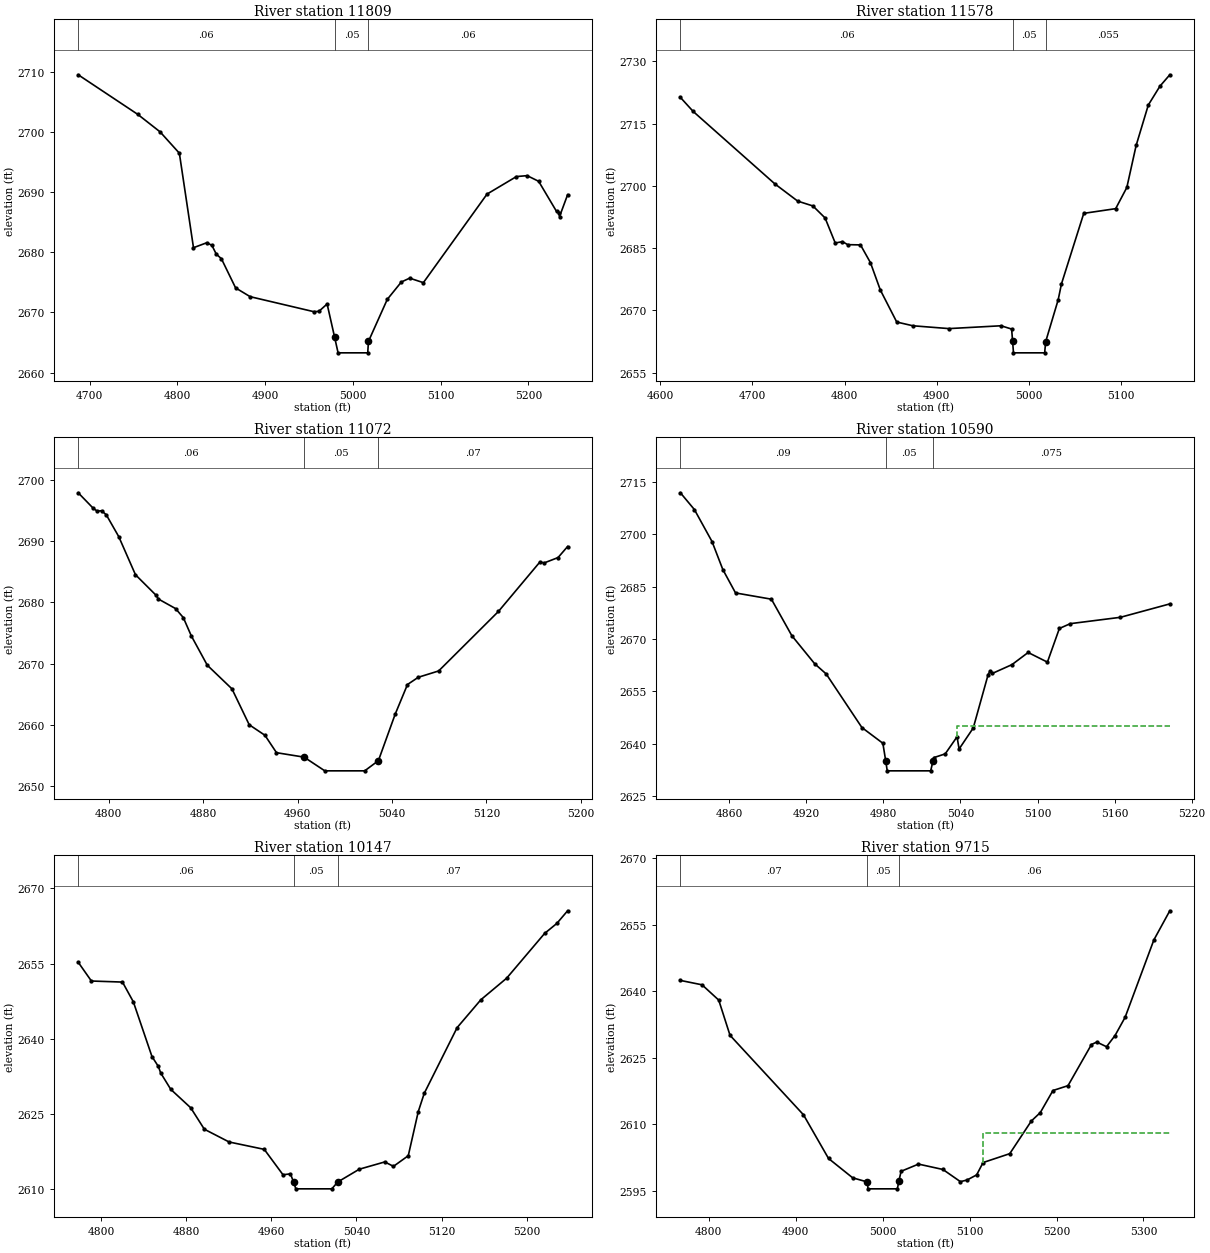
Type RM Length L Ch R = 1 ,11809   ,231,231,231
BEGIN DESCRIPTION:
aa
END DESCRIPTION:
XS GIS Cut Line= 3
      1058136.56       852660.58      1058277.99       852834.82
      1058575.55        852985.3
#Sta/Elev= 30
  4686.9 2709.49  4754.8 2702.91  4780.2 2700.01  4802.2 2696.46  4818.3 2680.76
  4833.6 2681.59  4839.3 2681.14  4844.3 2679.69  4850.1 2678.93  4866.3 2674.08
  4882.9 2672.62  4955.4 2670.13  4961.2 2670.18  4970.6 2671.41 4979.04 2665.95
  4983.1 2663.29  5016.9 2663.29  5017.7 2665.19  5039.2 2672.18  5055.2 2675.06
  5064.7  2675.7  5080.3 2674.95  5152.9 2689.67  5186.4 2692.58  5198.6 2692.73
  5211.7 2691.79  5232.1 2686.78  5234.7  2686.6  5235.5 2685.94  5244.7 2689.56
#Mann= 3 , 0 , 0
  4686.9     .06       0 4979.04     .05       0  5017.7     .06       0
Bank Sta=4979.04,5017.7
Exp/Cntr=0.3,0.1

Type RM Length L Ch R = 1 ,11578   ,506,506,506
BEGIN DESCRIPTION:
Little_Rock_Crk_30
END DESCRIPTION:
XS GIS Cut Line= 2
      1058104.87       852593.18      1058187.05       853117.48
#Sta/Elev= 30
  4621.9 2721.32  4635.8 2717.93  4724.5 2700.46  4749.1 2696.34  4765.6 2695.17
  4778.8 2692.28  4789.8 2686.25  4797.6 2686.57  4803.4 2685.85  4817.2 2685.79
    4828 2681.51  4838.7 2674.93  4856.5 2667.21    4874 2666.31  4913.1 2665.63
  4969.6 2666.31  4981.1 2665.52 4982.11 2662.59  4983.1 2659.79  5016.9 2659.79
    5018 2662.48  5031.6  2672.6  5035.1 2676.38  5059.3 2693.39  5093.9 2694.52
    5106 2699.62  5116.1 2709.75  5129.3 2719.49  5141.9 2724.02  5152.6 2726.77
#Mann= 3 , 0 , 0
  4621.9     .06       0 4982.11     .05       0    5018    .055       0
Bank Sta=4982.11,5018
Exp/Cntr=0.3,0.1

Type RM Length L Ch R = 1 ,11072   ,482,482,482
BEGIN DESCRIPTION:
Little_Rock_Crk_29
END DESCRIPTION:
XS GIS Cut Line= 2
      1057934.82       852579.01      1057597.57        852819.9
#Sta/Elev= 30
  4774.3 2697.95  4787.2 2695.38  4790.4 2694.95  4794.1 2695.01  4798.1 2694.34
  4808.6 2690.79  4822.8 2684.54  4840.2 2681.19  4842.2 2680.57  4856.7 2679.01
  4863.3 2677.53  4870.1 2674.53  4883.6 2669.74  4904.5 2665.87  4919.1    2660
  4932.4 2658.28  4942.2 2655.43  4965.6  2654.7  4983.1 2652.46  5016.9 2652.46
  5028.5 2654.13  5042.7 2661.73  5053.1 2666.58  5062.3 2667.77  5079.5  2668.8
  5130.1 2678.53  5165.3 2686.64  5168.8 2686.47  5180.6 2687.35  5188.7 2689.16
#Mann= 3 ,-1 , 0
  4774.3     .06       0  4965.6     .05       0  5028.5     .07       0
Bank Sta=4965.6,5028.5
Exp/Cntr=0.3,0.1

Type RM Length L Ch R = 1 ,10590   ,443,443,443
BEGIN DESCRIPTION:
Little_Rock_Crk_28
END DESCRIPTION:
XS GIS Cut Line= 2
        1057334.       852476.98       1057308.5       852856.74
#Sta/Elev= 30
  4822.2 2711.91  4833.1  2707.1  4846.8 2697.95  4855.2 2689.93  4865.1 2683.22
    4893 2681.43  4908.9 2670.97  4926.7 2662.92  4935.6 2660.02  4963.4 2644.66
  4979.7 2640.16 4981.98 2634.96  4983.1 2632.26  5016.9 2632.26 5018.65 2635.01
  5019.5 2636.07  5028.2 2637.12  5037.4 2642.01    5039 2638.52    5050 2644.53
  5061.6 2659.85  5063.1 2660.83  5064.9 2660.17  5080.1 2662.68  5092.7 2666.16
  5107.7  2663.4    5117 2673.04  5125.5 2674.42  5164.5 2676.24  5202.9 2680.08
#Mann= 3 , 0 , 0
  4822.2     .09       0 4981.98     .05       0 5018.65    .075       0
#XS Ineff= 2 , 0
       0                  5037.4       0    2645
Permanent Ineff=
       F       F
Bank Sta=4981.98,5018.65
Exp/Cntr=0.3,0.1

Type RM Length L Ch R = 1 ,10147   ,432,432,432
BEGIN DESCRIPTION:
Little_Rock_Crk_27
END DESCRIPTION:
XS GIS Cut Line= 2
      1056891.89       852440.14      1056866.39       852899.26
#Sta/Elev= 30
  4778.6 2655.28    4791 2651.53  4820.2 2651.32  4830.4 2647.38  4847.9 2636.46
  4853.9 2634.48  4856.1 2633.18  4865.6  2629.9  4884.3 2626.23  4897.1 2621.95
  4920.4  2619.4  4953.4 2617.93    4971 2612.86    4978 2613.04 4980.89 2611.43
  4983.1 2610.05  5016.9 2610.05  5022.4 2611.41  5042.7 2613.97  5066.6 2615.42
  5074.8 2614.54  5088.7 2616.66  5098.1 2625.47  5103.7 2629.11  5134.6 2642.23
  5156.9 2647.79  5181.1 2652.09  5216.8 2661.03  5228.3 2663.03  5238.4 2665.55
#Mann= 3 , 0 , 0
  4778.6     .06       0 4980.89     .05       0  5022.4     .07       0
Bank Sta=4980.89,5022.4
Exp/Cntr=0.3,0.1

Type RM Length L Ch R = 1 ,9715    ,296,296,296
BEGIN DESCRIPTION:
Little_Rock_Crk_26
END DESCRIPTION:
XS GIS Cut Line= 2
      1056381.76       852440.14      1056546.14       852978.61
#Sta/Elev= 30
  4767.3 2642.44  4792.2 2641.45  4811.4 2638.01  4824.4 2630.08  4908.9 2612.18
  4937.7 2602.35  4965.5 2597.99 4982.46 2597.05  4983.1 2595.51  5016.9 2595.51
 5018.66 2597.27  5021.2 2599.46  5041.2 2601.08  5069.3 2599.87  5089.4 2597.13
    5097 2597.49  5108.1 2598.65  5115.5 2601.43  5146.2 2603.43    5171 2610.78
  5181.3 2612.67  5195.9 2617.65  5213.2 2618.74  5240.2 2628.01  5246.3 2628.56
  5257.5 2627.51  5267.3 2630.03  5278.9 2634.14    5312 2651.57  5330.3 2658.12
#Mann= 3 , 0 , 0
  4767.3     .07       0 4982.46     .05       0 5018.66     .06       0
#XS Ineff= 2 , 0
       0                    5115       0    2608
Permanent Ineff=
       F       F
Bank Sta=4982.46,5018.66
Exp/Cntr=0.3,0.1

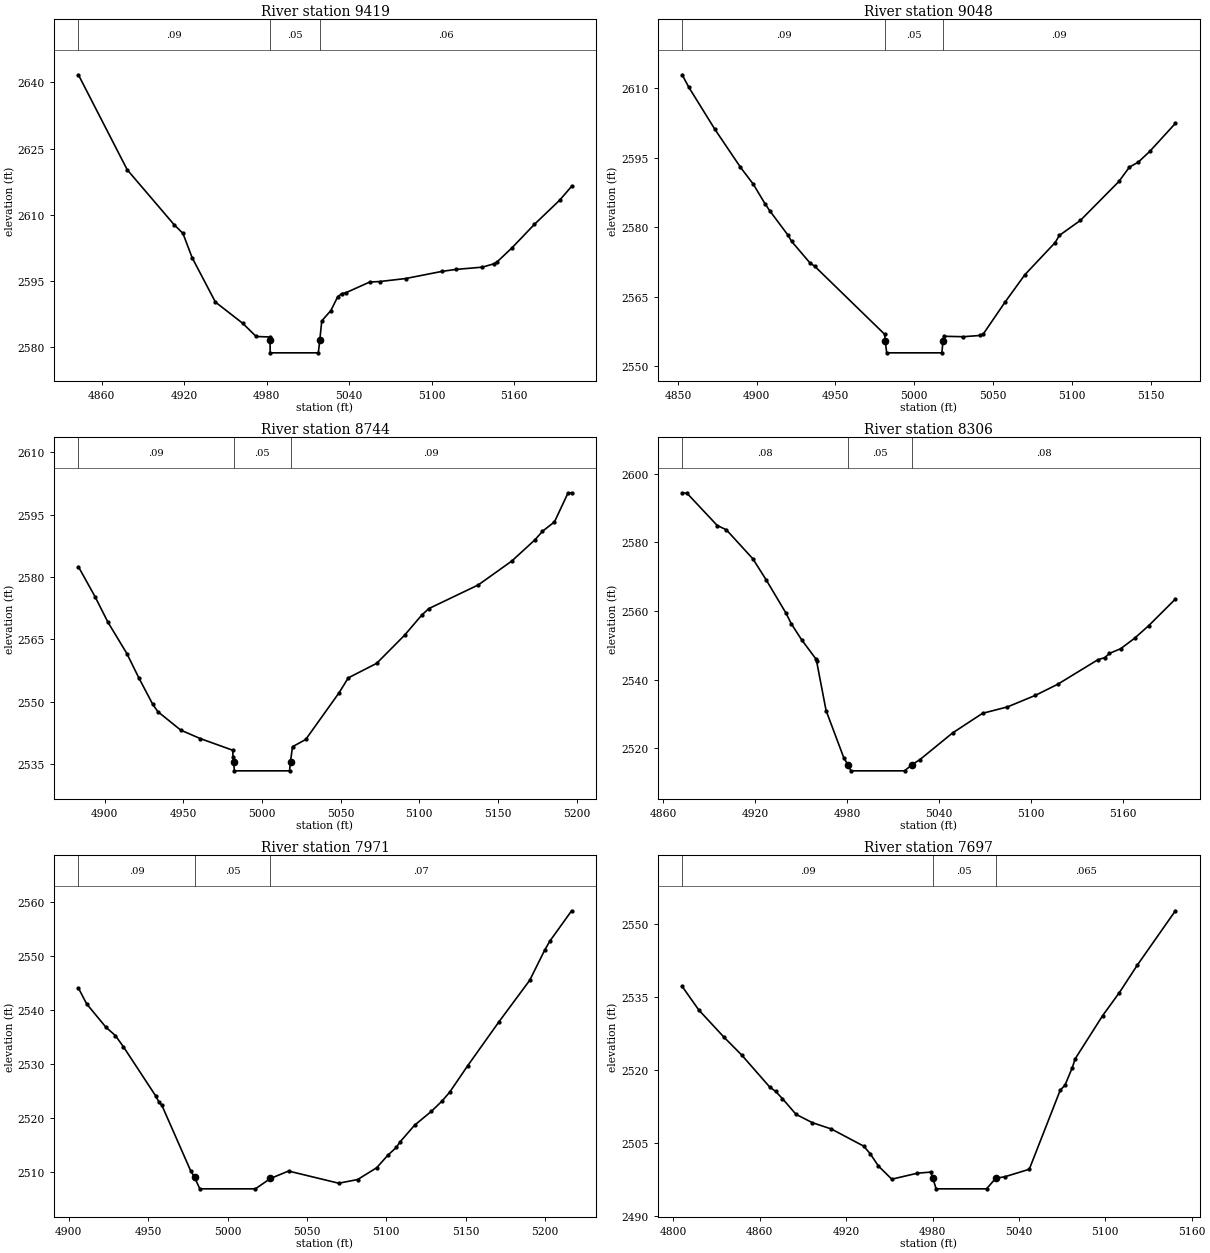
Type RM Length L Ch R = 1 ,9419    ,371,371,371
BEGIN DESCRIPTION:
Little_Rock_Crk_25
END DESCRIPTION:
XS GIS Cut Line= 2
      1056132.37       852726.38      1056359.09       853004.12
#Sta/Elev= 30
  4843.1 2641.75  4878.6 2620.21  4912.6 2607.79  4919.1 2605.78  4925.8 2600.26
  4942.7 2590.21  4962.5 2585.41  4972.3 2582.41  4982.1  2582.3 4982.39 2581.57
  4982.5  2578.7  5017.5  2578.7 5018.61 2581.72    5020 2585.94  5026.6 2588.28
  5031.6 2591.42  5034.5 2592.12  5037.7 2592.35  5054.9 2594.76  5062.3 2594.87
    5081 2595.55  5107.7 2597.19  5117.7 2597.62  5136.8 2598.13  5145.1 2598.89
  5147.2 2599.25  5158.1 2602.46  5174.5 2607.81    5193 2613.34  5201.6 2616.45
#Mann= 3 , 0 , 0
  4843.1     .09       0 4982.39     .05       0 5018.61     .06       0
Bank Sta=4982.39,5018.61
Exp/Cntr=0.3,0.1

Type RM Length L Ch R = 1 ,9048    ,304,304,304
BEGIN DESCRIPTION:
Little_Rock_Crk_24
END DESCRIPTION:
XS GIS Cut Line= 2
      1055953.82       852757.55      1055814.95       853038.12
#Sta/Elev= 30
  4852.7 2612.86    4857 2610.12  4873.4 2601.13  4889.7 2592.91  4897.9 2589.23
  4905.3 2585.02  4908.4 2583.47    4920  2578.2  4922.1 2576.94  4933.8 2572.28
  4936.9 2571.53  4981.2 2556.88 4981.58 2555.39  4982.5 2552.88  5017.5 2552.88
 5018.22 2555.35  5018.7 2556.45  5031.2 2556.36  5041.8 2556.63  5043.7  2556.9
  5057.5 2563.77  5070.2 2569.74  5089.4 2576.67  5092.1 2578.22  5105.4 2581.44
  5129.9 2589.86  5136.5 2592.93  5142.2 2594.03  5149.4 2596.32  5165.7 2602.38
#Mann= 3 , 0 , 0
  4852.7     .09       0 4981.58     .05       0 5018.22     .09       0
Bank Sta=4981.58,5018.22
Exp/Cntr=0.3,0.1

Type RM Length L Ch R = 1 ,8744    ,438,438,438
BEGIN DESCRIPTION:
Little_Rock_Crk_23
END DESCRIPTION:
XS GIS Cut Line= 2
      1055792.28       852644.19      1055489.04       852723.54
#Sta/Elev= 30
  4883.3 2582.51  4893.9 2575.28  4902.1 2569.13  4914.1 2561.61  4921.6 2555.84
  4930.5 2549.43  4933.8 2547.62  4948.4 2543.17  4960.8 2541.14  4981.4 2538.34
  4981.6 2536.78  4981.9 2535.47  4982.5 2533.38  5017.5 2533.38 5018.13 2535.62
  5019.4 2539.18  5027.8 2540.93    5049 2552.17  5054.8 2555.74  5072.9 2559.25
  5090.6    2566  5101.6 2570.88    5106 2572.41  5137.5 2578.12  5158.8 2583.87
  5173.5 2588.97  5178.3 2591.03  5185.9 2593.28  5194.5 2600.23  5196.8 2600.29
#Mann= 3 , 0 , 0
  4883.3     .09       0  4981.9     .05       0 5018.13     .09       0
Bank Sta=4981.9,5018.13
Exp/Cntr=0.3,0.1

Type RM Length L Ch R = 1 ,8306    ,335,335,335
BEGIN DESCRIPTION:
Little_Rock_Crk_22
END DESCRIPTION:
XS GIS Cut Line= 2
      1055741.27       852230.42      1055421.02       852261.59
#Sta/Elev= 30
  4872.4 2594.45  4875.6 2594.29  4895.3 2584.91  4901.2 2583.68  4918.5 2575.23
  4927.2 2569.09  4940.2 2559.34  4943.6 2556.28  4950.3 2551.65  4959.5 2546.14
  4960.1 2545.41  4966.3    2531  4977.9 2517.18 4980.68 2515.16  4982.5 2513.44
  5017.5 2513.44 5022.43 2515.25  5027.5 2516.71  5048.8 2524.47  5068.4  2530.2
  5084.6 2532.06  5102.7  2535.4  5117.3 2538.63  5143.6  2545.8  5148.2 2546.43
  5151.1 2547.64  5158.5 2549.02  5167.6 2552.07  5176.9 2555.78  5194.2 2563.49
#Mann= 3 , 0 , 0
  4872.4     .08       0 4980.68     .05       0 5022.43     .08       0
Bank Sta=4980.68,5022.43
Exp/Cntr=0.3,0.1

Type RM Length L Ch R = 1 ,7971    ,274,274,274
BEGIN DESCRIPTION:
Little_Rock_Crk_21
END DESCRIPTION:
XS GIS Cut Line= 2
      1055565.56        851870.5      1055341.67       852085.88
#Sta/Elev= 30
    4906  2544.1  4911.2 2541.16  4923.4 2536.82  4929.3  2535.3  4934.4 2533.21
  4954.6 2524.17  4956.6 2523.09  4958.6 2522.38  4976.7 2510.29 4979.15 2509.06
  4982.5 2506.93  5017.5 2506.93    5027 2508.85  5038.4 2510.22    5070 2507.97
  5081.9 2508.65  5093.9 2510.83  5100.9 2513.14  5106.3  2514.6  5108.6  2515.6
  5117.8 2518.71  5128.4 2521.28    5135 2523.15  5139.9 2524.82  5151.3 2529.74
  5170.8 2537.79  5190.3 2545.52  5199.8 2551.14    5203 2552.78  5216.7 2558.39
#Mann= 3 , 0 , 0
    4906     .09       0 4979.15     .05       0    5027     .07       0
Bank Sta=4979.15,5027
Exp/Cntr=0.3,0.1

Type RM Length L Ch R = 1 ,7697    ,431,431,431
BEGIN DESCRIPTION:
Little_Rock_Crk_20
END DESCRIPTION:
XS GIS Cut Line= 2
      1055321.83       851655.11      1055199.96       851975.36
#Sta/Elev= 30
  4806.1 2537.27  4817.6 2532.44  4835.2 2526.82  4847.5 2523.15  4866.8 2516.63
    4871 2515.69  4875.7 2514.22  4885.2 2510.98  4896.5 2509.27  4909.7 2507.97
  4932.3 2504.43  4936.8 2502.85  4942.4 2500.37  4951.7 2497.65  4969.4 2498.88
  4978.7 2499.11 4980.12 2497.95  4982.5 2495.67  5017.5 2495.67    5024 2497.86
  5030.1 2498.14  5047.2 2499.69  5068.7 2515.94    5072 2516.96  5077.1 2520.59
  5079.1 2522.39  5098.2 2531.28  5109.8    2536  5122.3 2541.66  5148.7 2552.81
#Mann= 3 , 0 , 0
  4806.1     .09       0 4980.12     .05       0    5024    .065       0
Bank Sta=4980.12,5024
Exp/Cntr=0.3,0.1

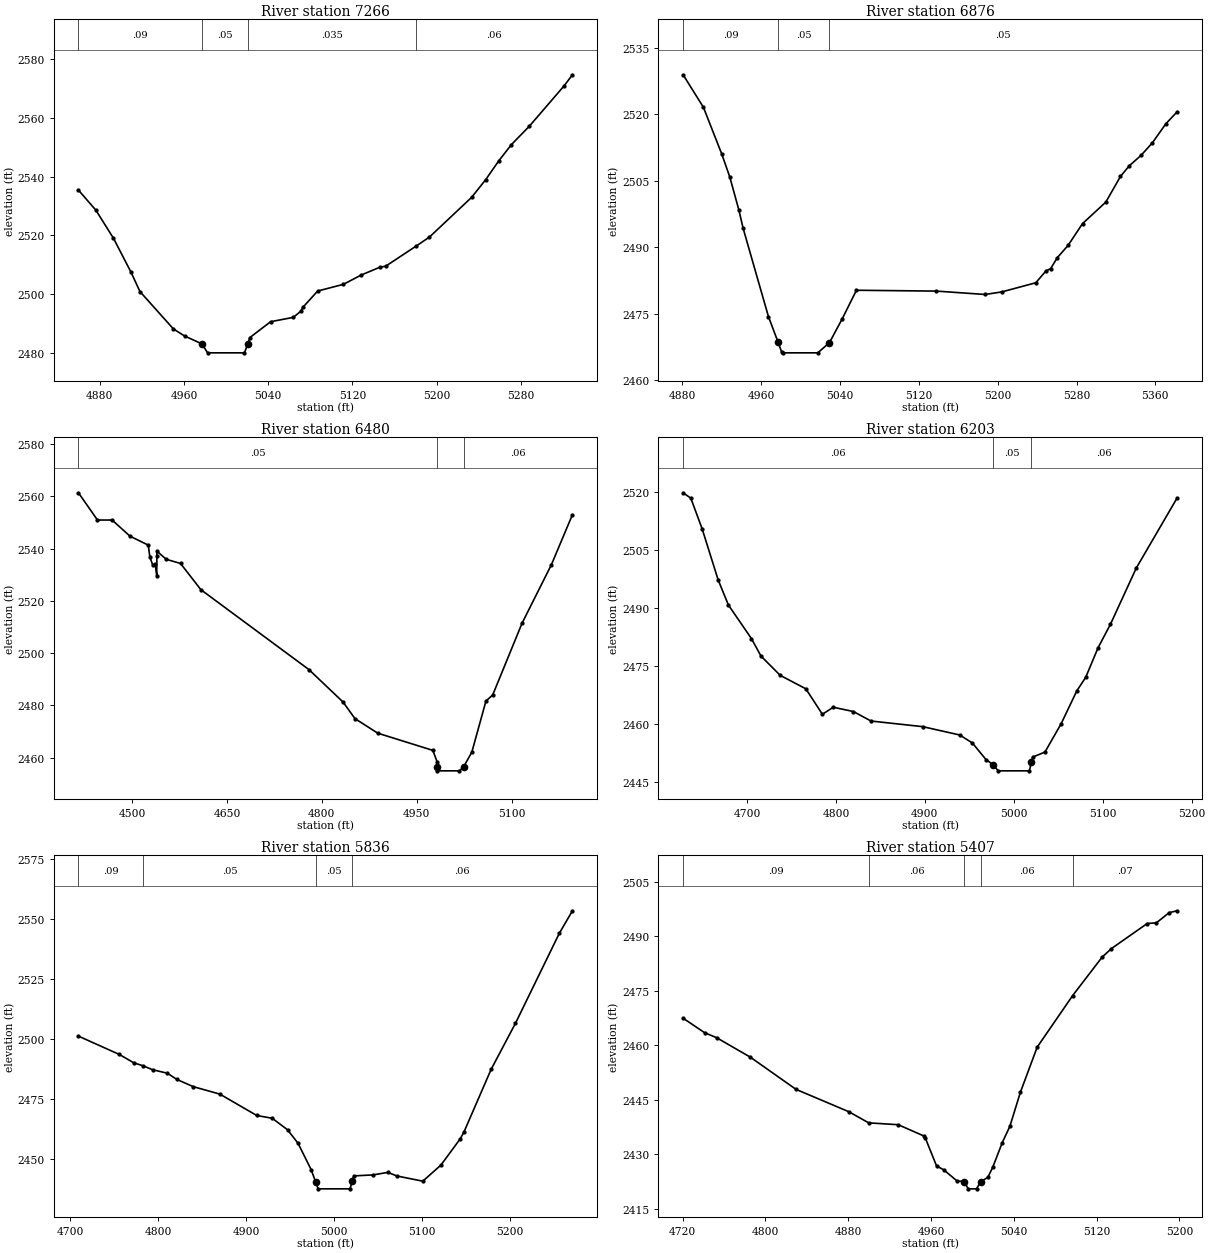
Type RM Length L Ch R = 1 ,7266    ,390,390,390
BEGIN DESCRIPTION:
Little_Rock_Crk_19.5
END DESCRIPTION:
XS GIS Cut Line= 2
      1054973.24       851485.06      1054709.67       851873.33
#Sta/Elev= 30
  4859.8  2535.4  4876.4 2528.56  4893.1 2519.02  4909.7 2507.54  4918.2 2500.95
    4950 2488.24  4960.6 2485.84  4977.1 2483.17  4982.5 2480.12  5017.5 2480.12
 5020.68  2483.2  5022.6  2485.3  5042.3 2490.69  5063.9 2492.17  5071.1 2494.28
  5072.8 2495.52    5087 2501.11  5111.5 2503.39  5128.5 2506.57  5145.8 2509.15
  5151.7 2509.57  5180.3 2516.32  5193.2 2519.44  5233.2 2532.92  5246.6 2538.94
    5259 2545.32  5271.1 2550.87    5288 2557.07    5321 2570.77    5329 2574.56
#Mann= 4 ,-1 , 0
  4859.8     .09       0  4977.1     .05       0 5020.68    .035       0
  5180.3     .06       0
Bank Sta=4977.1,5020.68
Exp/Cntr=0.3,0.1

Type RM Length L Ch R = 1 ,6876    ,396,396,396
BEGIN DESCRIPTION:
Little_Rock_Crk_19
END DESCRIPTION:
XS GIS Cut Line= 2
      1054624.65       851298.02      1054378.09       851734.46
#Sta/Elev= 30
  4880.8 2528.89  4901.4 2521.57    4920 2511.04  4928.1  2505.9  4937.3 2498.48
  4941.7 2494.29  4967.4 2474.37 4977.17 2468.61  4980.8 2466.38  4982.5  2466.2
  5017.5  2466.2  5029.3  2468.5  5042.1  2473.8  5056.7 2480.31  5137.8 2480.12
  5187.2 2479.36  5204.1 2479.93  5238.7    2482  5248.9 2484.64  5253.8  2485.2
  5260.5 2487.65  5271.4 2490.41  5286.1 2495.33  5309.8  2500.2  5324.6 2505.97
  5333.6 2508.38  5345.5 2510.72    5357 2513.55  5370.7 2517.86  5382.1 2520.54
#Mann= 3 , 0 , 0
  4880.8     .09       0 4977.17     .05       0  5029.3     .05       0
Bank Sta=4977.17,5029.3
Exp/Cntr=0.3,0.1

Type RM Length L Ch R = 1 ,6480    ,277,277,277
BEGIN DESCRIPTION:
Little_Rock_Crk_18
END DESCRIPTION:
XS GIS Cut Line= 2
      1054383.76       850824.73      1054103.19       851553.08
#Sta/Elev= 30
  4415.4 2561.38  4445.5 2550.95  4468.6 2550.95  4496.9 2544.77  4525.8 2541.34
  4528.2 2536.81  4532.9 2533.67  4536.8 2533.96  4539.2 2529.55  4539.3 2537.19
  4539.7 2538.99  4554.2 2535.91  4576.7 2534.34  4608.9 2524.29  4779.6 2493.72
  4833.5 2481.31  4852.4 2474.94  4888.4 2469.38  4975.4  2462.8  4982.2 2458.42
 4982.41 2456.57  4982.5 2454.97  5017.5 2454.97  5024.2 2456.57    5037 2462.11
  5059.3 2481.67    5070 2484.02  5116.5 2511.54  5162.6 2533.78    5196 2553.01
#Mann= 3 , 0 , 0
  4415.4     .05       0 4982.41     .05       0  5024.2     .06       0
Bank Sta=4982.41,5024.2
Exp/Cntr=0.3,0.1

Type RM Length L Ch R = 1 ,6203    ,367,367,367
BEGIN DESCRIPTION:
Little_Rock_Crk_17
END DESCRIPTION:
XS GIS Cut Line= 2
      1054066.34        850963.6      1053833.95       851468.06
#Sta/Elev= 30
  4628.2 2519.74  4636.9 2518.34  4649.7 2510.36  4667.6 2497.24  4679.1 2490.76
    4705 2482.08  4715.8 2477.55  4737.4 2472.57  4766.2  2469.1  4784.8 2462.52
    4797 2464.34  4819.7 2463.23  4839.4 2460.78  4897.7 2459.32  4939.2 2457.17
  4953.4 2455.11  4968.8  2450.8  4976.9 2449.47  4982.5 2447.91  5017.5 2447.91
 5019.81 2450.13  5021.2 2451.46    5035 2452.76  5053.2 2460.07  5070.8 2468.56
  5080.8 2472.05  5094.8 2479.74  5108.7  2485.8  5137.6 2500.26  5183.6 2518.41
#Mann= 3 , 0 , 0
  4628.2     .06       0  4976.9     .05       0 5019.81     .06       0
Bank Sta=4976.9,5019.81
Exp/Cntr=0.3,0.1

Type RM Length L Ch R = 1 ,5836    ,429,429,429
BEGIN DESCRIPTION:
Little_Rock_Crk_16
END DESCRIPTION:
XS GIS Cut Line= 2
      1053508.04        850963.6      1053607.23       851516.24
#Sta/Elev= 30
  4709.4 2501.27  4755.9 2493.63  4772.2 2490.16  4783.3 2488.83  4793.6 2487.27
  4810.5  2485.8  4821.2 2483.22    4840 2480.19  4870.1 2477.09  4912.1 2468.17
  4929.7 2467.01  4947.2 2462.17    4959 2456.58  4973.9 2445.59 4978.97 2440.47
  4981.9 2437.58  5018.1 2437.58  5020.6 2440.72  5022.4 2442.98  5043.9 2443.38
  5061.2 2444.44  5071.3 2442.95  5100.8 2440.77  5121.4 2447.48  5143.5 2458.51
  5147.7 2461.38  5178.5 2487.44  5206.1 2506.61  5256.1 2544.25  5270.9 2553.55
#Mann= 4 ,-1 , 0
  4709.4     .09       0  4783.3     .05       0 4978.97     .05       0
  5020.6     .06       0
Bank Sta=4978.97,5020.6
Exp/Cntr=0.5,0.3

Type RM Length L Ch R = 1 ,5407    ,83,83,83
BEGIN DESCRIPTION:
Little_Rock_Crk_15
END DESCRIPTION:
XS GIS Cut Line= 2
      1053186.57       851173.39       1053221.8       851649.44
#Sta/Elev= 30
  4720.5 2467.46  4741.3 2463.47  4752.8 2462.11  4785.3 2456.77  4829.6 2447.88
  4880.5 2441.74  4899.8 2438.66  4928.3 2438.15    4953 2435.07  4954.5 2434.51
  4965.4 2426.79  4972.3 2425.74  4985.1 2422.68    4992  2422.5    4996  2420.5
    5004  2420.5    5008  2422.5  5014.9 2423.64  5019.7 2426.46  5028.9 2433.25
  5036.2  2437.7  5046.4  2447.1  5062.6  2459.5  5096.9  2473.7  5125.3 2484.26
  5134.3 2486.62  5168.9 2493.52  5177.8 2493.72  5190.2 2496.53  5197.8 2497.03
#Mann= 5 ,-1 , 0
  4720.5     .09       0  4899.8     .06       0    4992     .05       0
    5008     .06       0  5096.9     .07       0
#XS Ineff= 2 , 0
       0    4950    2430    5050       0    2430
Permanent Ineff=
       F       F
Bank Sta=4992,5008
Exp/Cntr=0.5,0.3