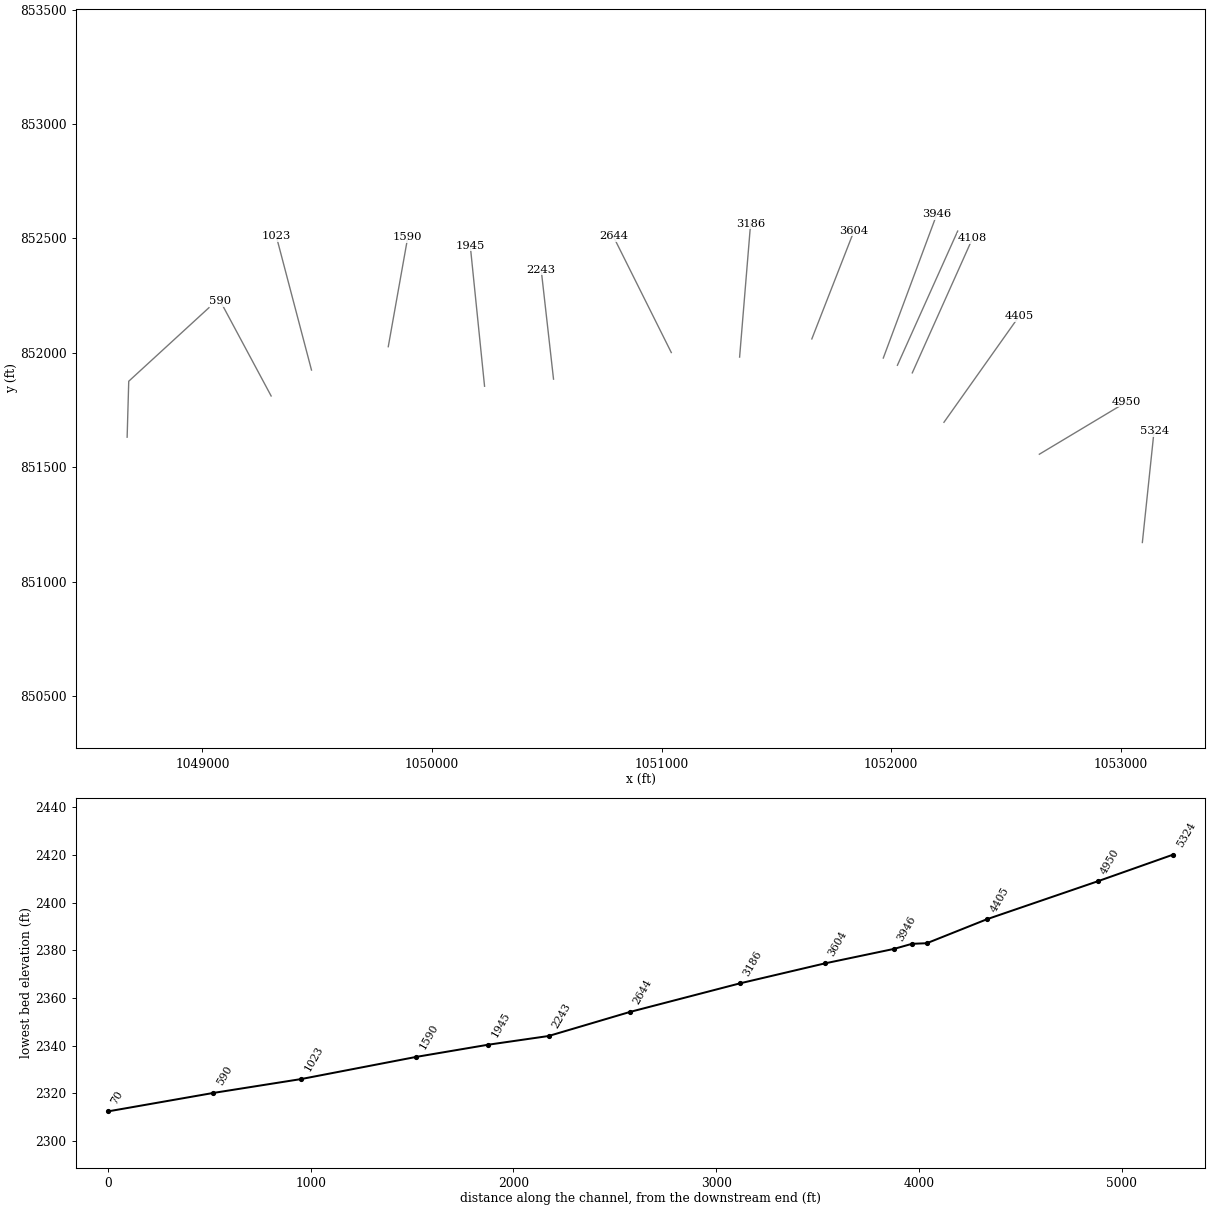
HEC-RAS study lds_little_rock_crk.prj: Little Rock Creek Limited Detail Study

--- lds_little_rock_crk.g01 (geometry) --- (continued)

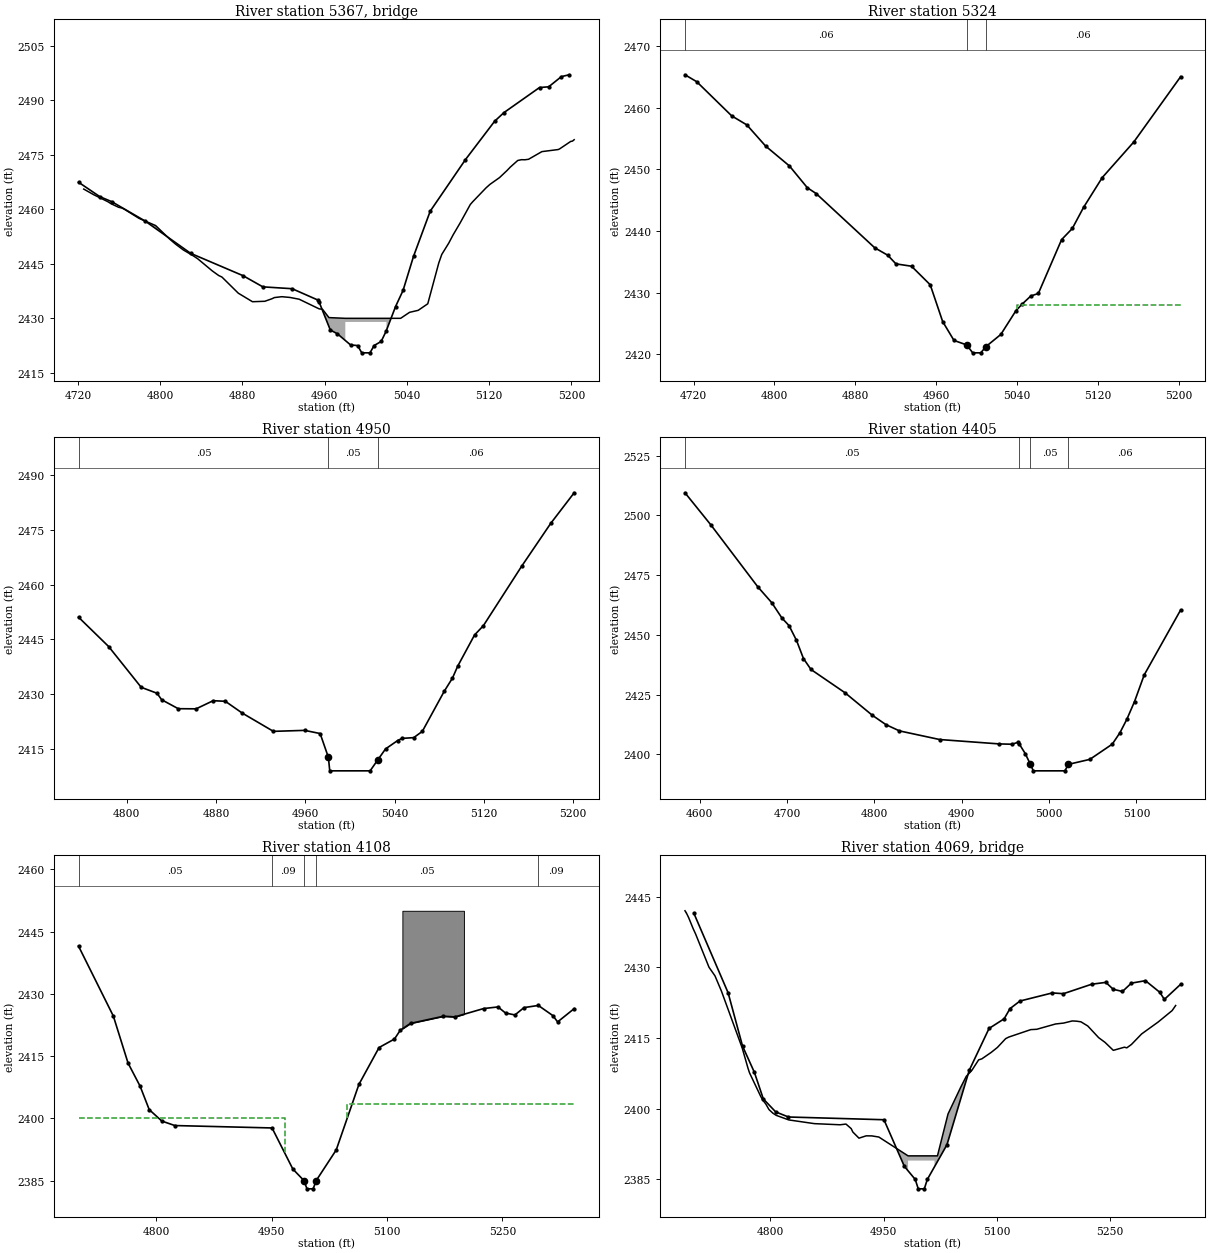
Type RM Length L Ch R = 3 ,5367    ,,,
BEGIN DESCRIPTION:
Little_Rock_Crk_14
Structure ID: Rockdale Road side street 2
Approximate Survey Structure
END DESCRIPTION:
Bridge Culvert--1,0,-1,-1, 0
Deck Dist Width WeirC Skew NumUp NumDn MinLoCord MaxHiCord MaxSubmerge Is_Ogee
33,14,3,0, 58, 58, , , , 0, 1,1,,
  4725.6  4735.3  4749.1  4752.3  4759.5  4762.8  4765.6  4779.3  4795.5  4809.2
  4814.9  4822.5  4831.9  4836.4  4850.7  4856.9    4860  4875.9  4889.7  4901.7
  4908.6    4911  4918.2  4926.1  4935.1  4954.5  4957.8  4964.1    4980    4980
    5020    5020  5033.8  5042.5  5050.9  5060.2  5070.9  5073.8  5080.6  5084.9
  5091.7  5101.6    5104  5116.9  5120.7    5130  5137.4  5140.4  5147.7  5151.3
  5154.7  5158.2  5171.2  5187.2  5188.6  5199.2    5201  5202.6
 2465.57 2464.02 2462.09 2461.52 2460.56 2460.35 2459.94 2457.52 2455.53  2451.8
 2450.42 2448.81 2447.24  2446.4 2443.03 2441.77 2441.36 2436.92 2434.57 2434.69
 2435.38 2435.71 2435.95 2435.75 2435.26 2432.61 2432.49  2430.2    2430    2430
    2430    2430    2430 2431.65  2432.2    2434 2445.22 2447.57 2450.69 2452.99
 2456.26 2461.34 2462.11 2465.91 2466.87 2468.73 2470.71  2471.6 2473.44 2473.66
 2473.64 2473.77 2475.88 2476.46 2476.66 2478.68 2478.78 2479.16
  2400.5  2400.5  2400.5  2400.5  2400.5  2400.5  2400.5  2400.5  2400.5  2400.5
  2400.5  2400.5  2400.5  2400.5  2400.5  2400.5  2400.5  2400.5  2400.5  2400.5
  2400.5  2400.5  2400.5  2400.5  2400.5  2400.5  2400.5  2400.5  2400.5    2429
    2429  2400.5  2400.5  2400.5  2400.5  2400.5  2400.5  2400.5  2400.5  2400.5
  2400.5  2400.5  2400.5  2400.5  2400.5  2400.5  2400.5  2400.5  2400.5  2400.5
  2400.5  2400.5  2400.5  2400.5  2400.5  2400.5  2400.5  2400.5
  4725.6  4735.3  4749.1  4752.3  4759.5  4762.8  4765.6  4779.3  4795.5  4809.2
  4814.9  4822.5  4831.9  4836.4  4850.7  4856.9    4860  4875.9  4889.7  4901.7
  4908.6    4911  4918.2  4926.1  4935.1  4954.5  4957.8  4964.1    4980    4980
    5020    5020  5033.8  5042.5  5050.9  5060.2  5070.9  5073.8  5080.6  5084.9
  5091.7  5101.6    5104  5116.9  5120.7    5130  5137.4  5140.4  5147.7  5151.3
  5154.7  5158.2  5171.2  5187.2  5188.6  5199.2    5201  5202.6
 2465.57 2464.02 2462.09 2461.52 2460.56 2460.35 2459.94 2457.52 2455.53  2451.8
 2450.42 2448.81 2447.24  2446.4 2443.03 2441.77 2441.36 2436.92 2434.57 2434.69
 2435.38 2435.71 2435.95 2435.75 2435.26 2432.61 2432.49  2430.2    2430    2430
    2430    2430    2430 2431.65  2432.2    2434 2445.22 2447.57 2450.69 2452.99
 2456.26 2461.34 2462.11 2465.91 2466.87 2468.73 2470.71  2471.6 2473.44 2473.66
 2473.64 2473.77 2475.88 2476.46 2476.66 2478.68 2478.78 2479.16
  2400.5  2400.5  2400.5  2400.5  2400.5  2400.5  2400.5  2400.5  2400.5  2400.5
  2400.5  2400.5  2400.5  2400.5  2400.5  2400.5  2400.5  2400.5  2400.5  2400.5
  2400.5  2400.5  2400.5  2400.5  2400.5  2400.5  2400.5  2400.5  2400.5    2429
    2429  2400.5  2400.5  2400.5  2400.5  2400.5  2400.5  2400.5  2400.5  2400.5
  2400.5  2400.5  2400.5  2400.5  2400.5  2400.5  2400.5  2400.5  2400.5  2400.5
  2400.5  2400.5  2400.5  2400.5  2400.5  2400.5  2400.5  2400.5
BR Coef= 1 , 1 , 0 ,1.25, 0 ,,,0.8,0,2,0,
WSPro=,,,, 1 ,,,, 0 ,,,, 0 ,,,,-1 ,-1 ,-1 , 0 , 0 , 0 , 0 , 0
BC Design=,, 0 ,, 0 ,,,,,,
BC HTab HWMax=2497.03

Type RM Length L Ch R = 1 ,5324    ,374,374,374
BEGIN DESCRIPTION:
Little_Rock_Crk_13
END DESCRIPTION:
XS GIS Cut Line= 2
      1053094.27       851170.49      1053145.28       851657.94
#Sta/Elev= 30
  4711.5 2465.32  4723.1  2464.2  4757.7 2458.66  4772.7 2457.19  4791.2 2453.77
  4814.8 2450.54  4832.5 2447.01  4841.2 2446.07  4899.1 2437.28    4912 2436.07
  4920.1 2434.67  4935.5 2434.29    4954 2431.28  4966.3 2425.32  4977.5 2422.26
  4990.1 2421.53    4996 2420.25    5004 2420.25    5009 2421.25  5023.8 2423.23
  5038.7 2427.07  5044.7 2428.12  5053.5 2429.47  5060.9 2429.87  5083.9  2438.6
  5094.5 2440.41  5105.6 2443.82  5124.1 2448.66  5155.3 2454.43  5201.6 2465.01
#Mann= 3 , 0 , 0
  4711.5     .06       0  4990.1     .05       0    5009     .06       0
#XS Ineff= 2 , 0
       0    4960    2428    5040       0    2428
Permanent Ineff=
       F       F
Bank Sta=4990.1,5009
Exp/Cntr=0.5,0.3

Type RM Length L Ch R = 1 ,4950    ,545,545,545
BEGIN DESCRIPTION:
Little_Rock_Crk_12
END DESCRIPTION:
XS GIS Cut Line= 2
      1052645.53       851556.37      1053026.25       851785.47
#Sta/Elev= 30
  4756.7  2451.1  4783.7 2443.06  4812.9 2431.88  4827.1 2430.25  4831.2 2428.48
  4846.1 2426.02  4862.1 2425.98  4877.4 2428.21  4888.3 2428.05  4903.4 2424.83
  4931.4 2419.81  4959.4 2420.08  4973.3 2419.21  4980.7 2412.67  4981.9 2408.99
  5018.1 2408.99 5025.11 2412.06  5031.9 2414.99  5042.8  2417.3  5046.6 2417.88
  5057.2 2418.09  5064.9 2419.81  5084.6 2430.83  5091.9  2434.4  5096.6 2437.67
  5111.7 2446.22  5119.6 2448.76  5153.8    2465    5180 2476.81    5201 2485.19
#Mann= 3 , 0 , 0
  4756.7     .05       0  4980.7     .05       0 5025.11     .06       0
Bank Sta=4980.7,5025.11
Exp/Cntr=0.3,0.1

Type RM Length L Ch R = 1 ,4405    ,297,297,297
BEGIN DESCRIPTION:
Little_Rock_Crk_11
END DESCRIPTION:
XS GIS Cut Line= 2
      1052230.07       851695.96      1052557.45       852159.61
#Sta/Elev= 30
    4583 2509.41  4612.9 2495.86  4666.4 2470.06  4682.4 2463.42  4693.9 2457.07
  4702.2 2453.82  4710.7 2447.67  4718.7 2440.05  4727.3 2435.49  4766.2 2425.77
  4797.4 2416.37  4813.1 2412.42  4828.6  2409.8  4874.6 2406.19    4943 2404.35
  4957.5 2404.22  4964.3 2405.03  4965.6 2404.45  4972.7 2400.28 4978.57  2395.8
  4981.9 2393.09  5018.1 2393.09 5022.01  2395.8  5046.6 2397.88  5072.3 2404.25
  5081.1 2409.03    5089 2414.65  5097.8 2422.07  5108.9 2433.23  5150.6 2460.38
#Mann= 4 ,-1 , 0
    4583     .05       0  4965.6     .09       0 4978.57     .05       0
 5022.01     .06       0
Bank Sta=4978.57,5022.01
Exp/Cntr=0.5,0.3

Type RM Length L Ch R = 1 ,4108    ,73,73,73
BEGIN DESCRIPTION:
Little_Rock_Crk_9.75
END DESCRIPTION:
XS GIS Cut Line= 2
      1052092.14         851912.      1052354.71       852500.28
#Sta/Elev= 30
    4699 2441.49  4744.3 2424.62  4763.4  2413.3  4779.1 2407.72  4790.9 2402.09
  4807.3 2399.33  4824.2 2398.25  4950.6 2397.67  4977.6 2387.77    4992    2385
    4996    2383    5004    2383    5008    2385    5034 2392.37  5063.5 2408.17
  5089.7 2417.05  5109.7  2419.1  5117.4 2421.25  5130.6 2422.87  5173.4 2424.59
  5188.2 2424.43  5225.6 2426.44  5244.3 2426.83  5254.1 2425.36  5266.3  2424.9
  5278.1 2426.67  5296.7 2427.19  5315.6 2424.74  5321.8 2423.22  5343.3 2426.42
#Mann= 5 ,-1 , 0
    4699     .05       0  4950.6     .09       0    4992     .05       0
    5008     .05       0  5296.7     .09       0
#XS Ineff= 2 , 0
       0    4968    2400  5048.5       0 2403.34
Permanent Ineff=
       F       F
#Block Obstruct= 1 ,-1
    5120    5200    2450
Bank Sta=4992,5008
Exp/Cntr=0.5,0.3

Type RM Length L Ch R = 3 ,4069    ,,,
BEGIN DESCRIPTION:
Little_Rock_Crk_9.5
Structure ID: Rockdale Road side street 1
Approximate Survey Structure
END DESCRIPTION:
Bridge Culvert--1,0,-1,-1, 0
Deck Dist Width WeirC Skew NumUp NumDn MinLoCord MaxHiCord MaxSubmerge Is_Ogee
31,16,3,0, 60, 60, , , , 0, 1,1,,
  4687.2  4688.8  4692.1    4698  4701.2    4719  4726.9  4735.5  4762.9  4770.8
  4772.6  4787.4  4790.4  4794.1  4798.4  4803.5    4808  4824.6  4858.6  4892.5
  4900.3  4907.2  4909.4  4917.5    4927  4934.5  4943.8  4982.5  4982.5  5017.5
  5017.5  5021.4  5035.4  5052.1  5059.5  5066.8  5075.9  5080.1  5092.5  5100.7
  5111.7  5115.8  5144.9  5152.8  5177.8  5188.4  5199.8  5205.2  5211.3  5220.4
  5234.8  5243.1  5254.2  5268.9    5272  5278.2  5291.7  5313.6  5332.1  5336.7
 2442.03 2441.65 2440.56 2438.24 2437.13 2430.04 2428.22 2424.96 2412.92 2408.51
 2407.64 2402.64 2401.79 2401.03 2399.83 2399.07  2398.6 2397.63 2396.84  2396.6
 2396.75 2395.79 2395.06 2393.76 2394.25 2394.24    2394    2390    2390    2390
    2390    2390  2398.9 2404.54 2406.87 2408.12 2410.38 2410.59 2411.96 2413.01
 2414.89 2415.22  2416.8 2416.87    2418 2418.19 2418.64  2418.6 2418.46 2417.57
 2415.09 2414.11  2412.4 2413.07 2412.93 2413.65 2415.89 2418.42 2420.85 2421.92
    2363    2363    2363    2363    2363    2363    2363    2363    2363    2363
    2363    2363    2363    2363    2363    2363    2363    2363    2363    2363
    2363    2363    2363    2363    2363    2363    2363    2363    2389    2389
    2363    2363    2363    2363    2363    2363    2363    2363    2363    2363
    2363    2363    2363    2363    2363    2363    2363    2363    2363    2363
    2363    2363    2363    2363    2363    2363    2363    2363    2363    2363
  4687.2  4688.8  4692.1    4698  4701.2    4719  4726.9  4735.5  4762.9  4770.8
  4772.6  4787.4  4790.4  4794.1  4798.4  4803.5    4808  4824.6  4858.6  4892.5
  4900.3  4907.2  4909.4  4917.5    4927  4934.5  4943.8  4982.5  4982.5  5017.5
  5017.5  5021.4  5035.4  5052.1  5059.5  5066.8  5075.9  5080.1  5092.5  5100.7
  5111.7  5115.8  5144.9  5152.8  5177.8  5188.4  5199.8  5205.2  5211.3  5220.4
  5234.8  5243.1  5254.2  5268.9    5272  5278.2  5291.7  5313.6  5332.1  5336.7
 2442.03 2441.65 2440.56 2438.24 2437.13 2430.04 2428.22 2424.96 2412.92 2408.51
 2407.64 2402.64 2401.79 2401.03 2399.83 2399.07  2398.6 2397.63 2396.84  2396.6
 2396.75 2395.79 2395.06 2393.76 2394.25 2394.24    2394    2390    2390    2390
    2390    2390  2398.9 2404.54 2406.87 2408.12 2410.38 2410.59 2411.96 2413.01
 2414.89 2415.22  2416.8 2416.87    2418 2418.19 2418.64  2418.6 2418.46 2417.57
 2415.09 2414.11  2412.4 2413.07 2412.93 2413.65 2415.89 2418.42 2420.85 2421.92
    2363    2363    2363    2363    2363    2363    2363    2363    2363    2363
    2363    2363    2363    2363    2363    2363    2363    2363    2363    2363
    2363    2363    2363    2363    2363    2363    2363    2363    2389    2389
    2363    2363    2363    2363    2363    2363    2363    2363    2363    2363
    2363    2363    2363    2363    2363    2363    2363    2363    2363    2363
    2363    2363    2363    2363    2363    2363    2363    2363    2363    2363
BR Coef= 1 , 1 , 0 ,1.25, 0 ,,,0.8,0,2,0,
WSPro=,,,, 1 ,,,, 0 ,,,, 0 ,,,,-1 ,-1 ,-1 , 0 , 0 , 0 , 0 , 0
BC Design=,, 0 ,, 0 ,,,,,,
BC HTab HWMax=2441.49

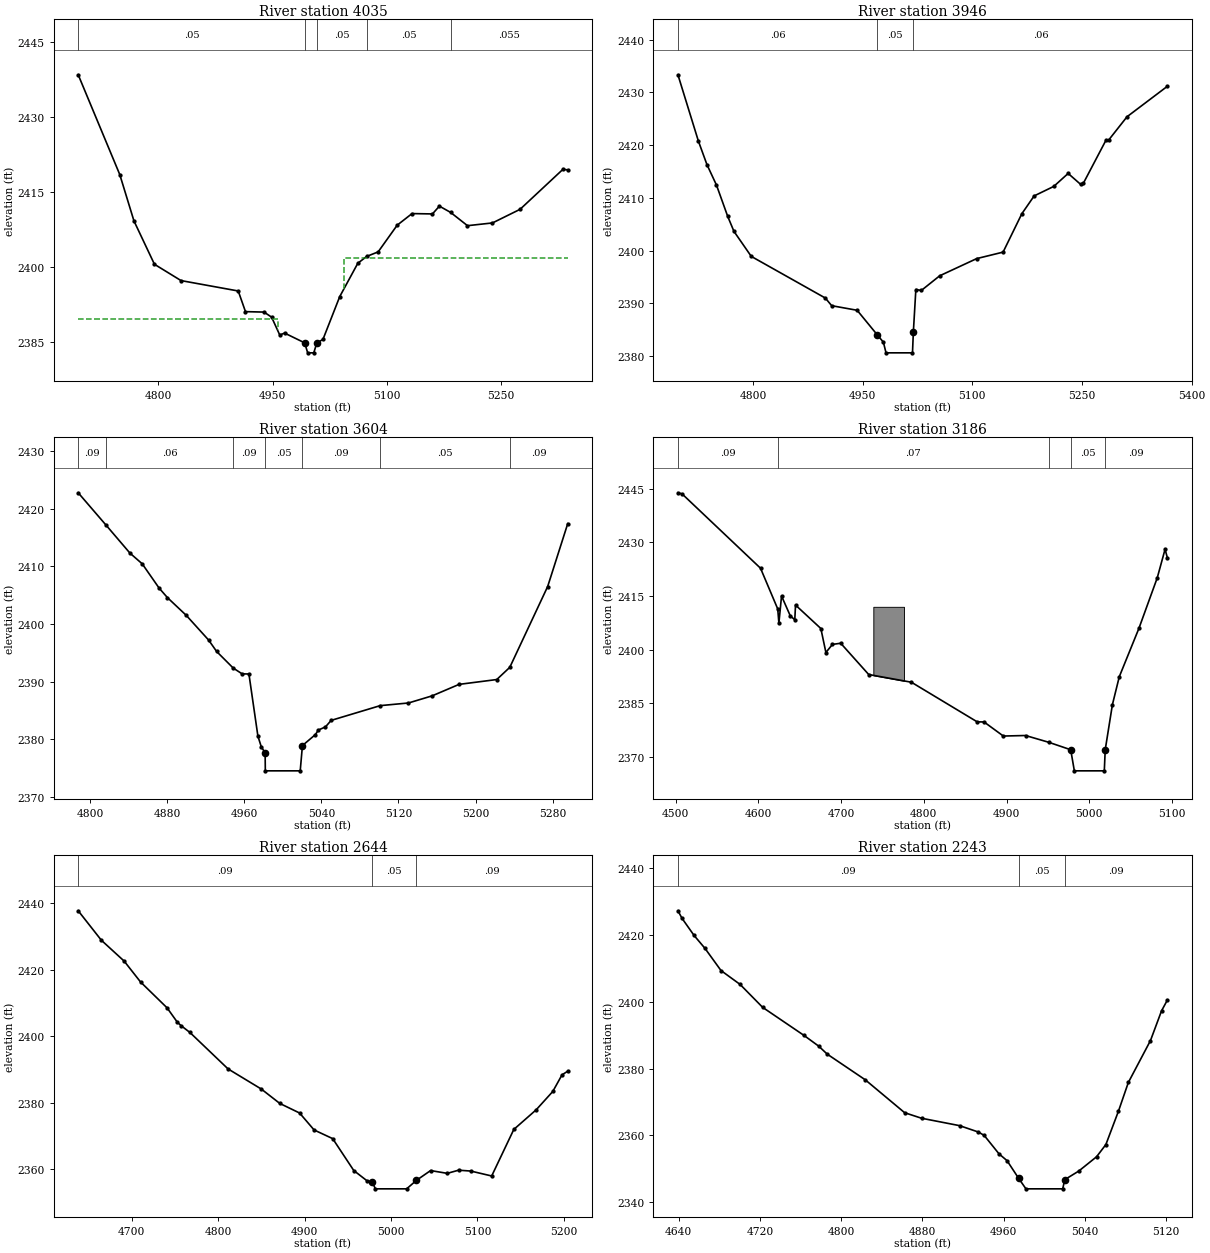
Type RM Length L Ch R = 1 ,4035    ,89,89,89
BEGIN DESCRIPTION:
Little_Rock_Crk_9.25
END DESCRIPTION:
XS GIS Cut Line= 2
      1052027.33       851945.23      1052289.89       852531.86
#Sta/Elev= 30
  4694.7 2438.36  4749.3 2418.39  4767.9 2409.13  4794.8 2400.46  4829.7  2397.2
  4904.8 2395.12  4914.3 2390.99  4938.7  2390.9  4948.6 2389.89  4959.3 2386.32
  4965.7  2386.7    4992 2384.75    4996 2382.75    5004 2382.75    5008 2384.75
    5016 2385.42  5038.1 2394.01  5061.8 2400.66  5073.4 2402.03  5088.5 2402.94
  5113.5 2408.28    5133  2410.6  5159.8 2410.53  5168.9 2412.09  5183.6 2410.84
  5205.8 2408.18  5238.6 2408.73  5274.8 2411.45  5331.1 2419.45  5337.4 2419.34
#Mann= 5 ,-1 , 0
  4694.7     .05       0    4992     .05       0    5008     .05       0
  5073.4     .05       0  5183.6    .055       0
#XS Ineff= 2 , 0
       0  4956.5 2389.56  5043.5       0 2401.67
Permanent Ineff=
       F       F
Bank Sta=4992,5008
Exp/Cntr=0.5,0.3

Type RM Length L Ch R = 1 ,3946    ,342,342,342
BEGIN DESCRIPTION:
Little_Rock_Crk_10
END DESCRIPTION:
XS GIS Cut Line= 2
      1051965.84       851976.81      1052198.71       852604.51
#Sta/Elev= 30
  4697.3 2433.34  4725.3 2420.76    4737  2416.3    4750 2412.43  4765.4 2406.48
  4773.9 2403.65  4797.6  2398.9  4898.9    2391  4907.6 2389.55  4942.4 2388.68
    4970 2384.01  4978.3 2382.63  4981.9 2380.61  5018.1 2380.61  5019.3  2384.6
  5022.7 2392.62  5030.2 2392.44  5055.3 2395.22  5105.9 2398.48    5142 2399.71
  5167.7    2407  5184.5 2410.37  5211.3 2412.17    5231 2414.63  5248.2 2412.54
  5251.8 2412.77  5282.7 2420.93  5286.6    2421  5311.5 2425.38  5366.8 2431.17
#Mann= 3 , 0 , 0
  4697.3     .06       0    4970     .05       0  5019.3     .06       0
Bank Sta=4970,5019.3
Exp/Cntr=0.3,0.1

Type RM Length L Ch R = 1 ,3604    ,418,418,418
BEGIN DESCRIPTION:
Little_Rock_Crk_09
END DESCRIPTION:
XS GIS Cut Line= 2
      1051654.57       852060.38      1051838.78       852533.66
#Sta/Elev= 30
  4787.8 2422.77  4816.7 2417.15  4841.5 2412.29  4854.2 2410.44  4871.7 2406.23
  4880.3 2404.58  4899.9 2401.49  4923.1  2397.2  4931.4 2395.22  4948.6 2392.34
  4957.8 2391.34  4964.9 2391.31  4974.2 2380.53  4977.8 2378.63  4981.7 2377.65
  4981.9  2374.5  5018.1  2374.5  5020.4 2378.89  5033.9  2380.8  5036.9 2381.58
  5044.3 2382.13  5050.2 2383.26  5101.1 2385.82  5130.4 2386.28    5155 2387.52
  5182.9 2389.51    5222 2390.35  5235.5 2392.47  5274.8  2406.5  5295.6 2417.41
#Mann= 7 ,-1 , 0
  4787.8     .09       0  4816.7     .06       0  4948.6     .09       0
  4981.7     .05       0  5020.4     .09       0  5101.1     .05       0
  5235.5     .09       0
Bank Sta=4981.7,5020.4
Exp/Cntr=0.3,0.1

Type RM Length L Ch R = 1 ,3186    ,542,542,542
BEGIN DESCRIPTION:
Little_Rock_Crk_08
END DESCRIPTION:
XS GIS Cut Line= 3
      1051339.99       851981.02      1051388.17       852567.67
      1051388.17       852564.84
#Sta/Elev= 30
  4502.9 2443.89  4507.9 2443.58  4602.7 2422.79  4623.5  2411.4  4624.9 2407.45
  4628.1 2415.02  4638.7 2409.46  4644.1 2408.38    4645 2412.49  4675.6 2405.93
  4681.7 2399.22  4689.6 2401.49  4699.6 2401.81  4733.4 2393.07    4785 2390.91
  4864.5 2379.83  4872.8  2379.8  4896.1 2375.86  4922.9 2376.01  4950.9 2374.12
  4977.5 2372.03  4981.9 2366.13  5018.1 2366.13  5019.2 2372.02  5027.9 2384.65
  5036.2 2392.45    5060 2406.02  5082.1 2420.12  5091.5 2428.08  5094.4 2425.65
#Mann= 5 ,-1 , 0
  4502.9     .09       0  4623.5     .07       0  4950.9     .09       0
  4977.5     .05       0  5019.2     .09       0
#Block Obstruct= 1 ,-1
    4739    4776    2412
Bank Sta=4977.5,5019.2
Exp/Cntr=0.3,0.1

Type RM Length L Ch R = 1 ,2644    ,401,401,401
BEGIN DESCRIPTION:
Little_Rock_Crk_07
END DESCRIPTION:
XS GIS Cut Line= 2
      1051042.41       852000.86      1050790.18       852508.16
#Sta/Elev= 30
    4638 2437.64  4664.8 2428.79  4691.2 2422.52  4710.1 2416.27  4740.8  2408.5
  4752.7 2404.18    4757 2403.15  4767.3 2401.09  4811.4 2390.15  4849.9  2384.1
  4871.3 2379.78  4894.2  2376.9    4911 2371.81  4932.5 2369.21  4956.9 2359.63
  4972.6 2356.47  4978.1 2356.29  4981.9 2354.13  5018.1 2354.13  5029.3 2356.66
  5045.8 2359.62  5065.1 2358.78  5078.2 2359.73  5092.3 2359.47  5116.5 2357.99
  5142.1 2371.97    5168 2377.87  5187.2 2383.37  5197.9 2388.37  5204.5 2389.46
#Mann= 3 ,-1 , 0
    4638     .09       0  4978.1     .05       0  5029.3     .09       0
Bank Sta=4978.1,5029.3
Exp/Cntr=0.3,0.1

Type RM Length L Ch R = 1 ,2243    ,298,298,298
BEGIN DESCRIPTION:
Little_Rock_Crk_06
END DESCRIPTION:
XS GIS Cut Line= 2
      1050529.45       851884.67       1050475.6       852363.62
#Sta/Elev= 30
  4639.3 2427.21  4643.4 2424.92  4655.2 2419.83    4666 2415.94  4681.7 2409.33
  4700.5 2405.18  4722.7 2398.32  4763.3 2389.95  4777.9 2386.71  4786.3 2384.32
  4823.7 2376.65  4862.5  2366.8  4879.1 2365.15  4916.6 2362.93  4935.1 2361.02
  4940.8 2360.01  4955.4 2354.49  4963.3 2352.46  4974.8 2347.13  4981.9 2344.03
  5018.1 2344.03  5020.1 2346.78  5033.9 2349.35  5051.4 2353.62  5060.6 2357.29
    5073 2367.29  5082.7 2375.85  5104.5  2388.4  5115.4 2397.29  5121.2 2400.55
#Mann= 3 ,-1 , 0
  4639.3     .09       0  4974.8     .05       0  5020.1     .09       0
Bank Sta=4974.8,5020.1
Exp/Cntr=0.3,0.1

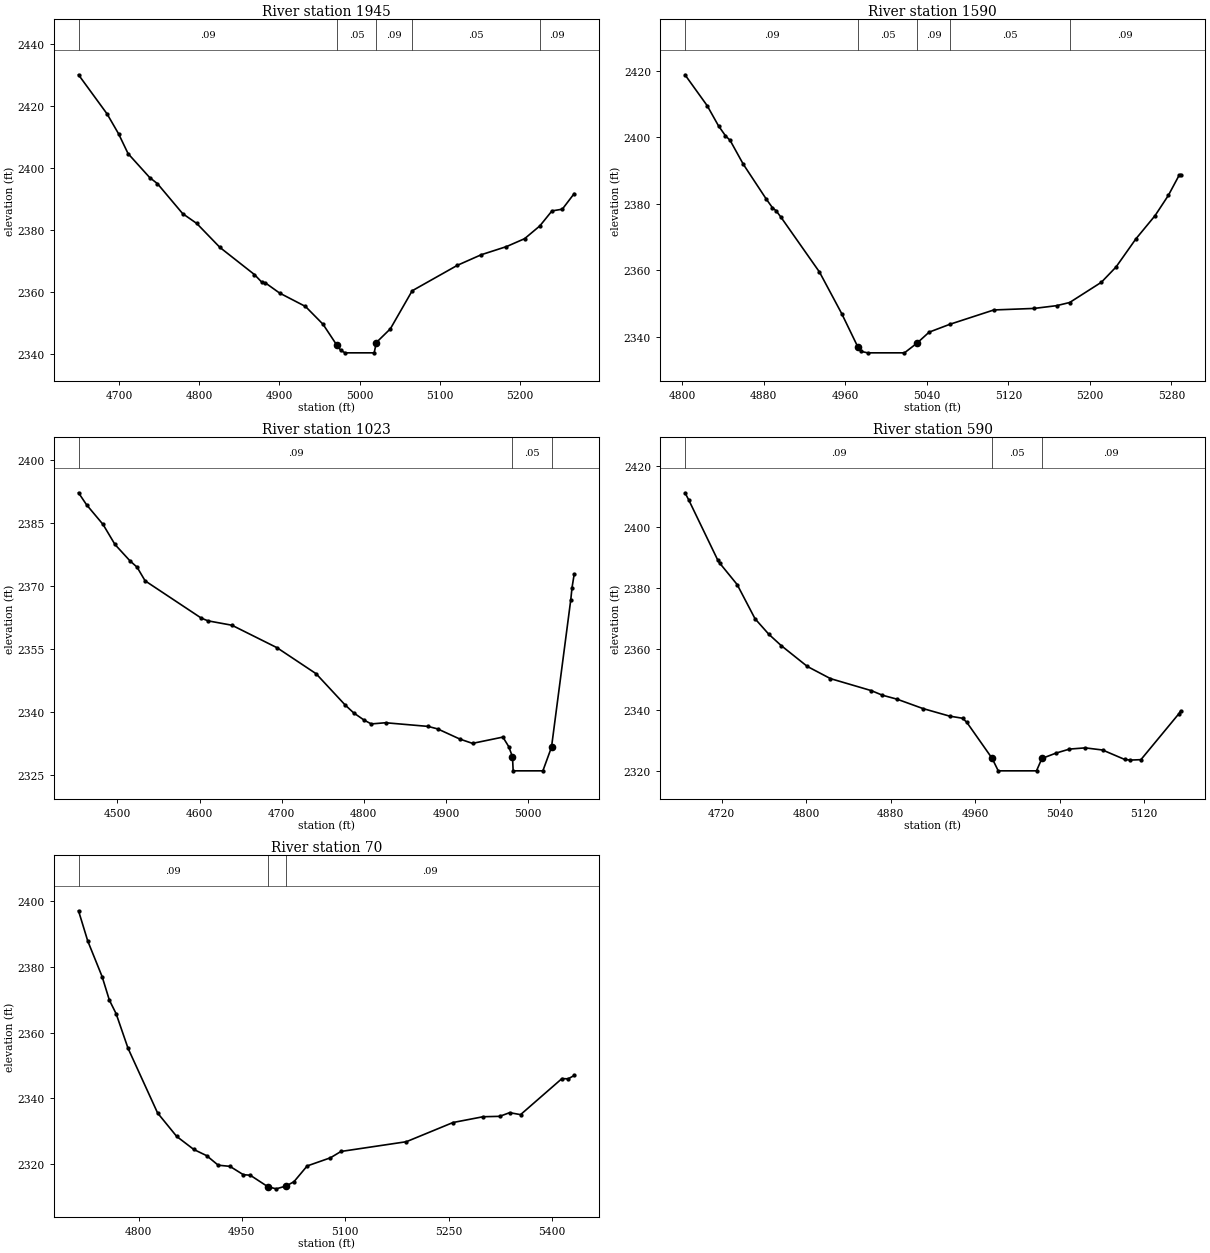
Type RM Length L Ch R = 1 ,1945    ,355,355,355
BEGIN DESCRIPTION:
Little_Rock_Crk_05
END DESCRIPTION:
XS GIS Cut Line= 2
      1050229.04       851853.49      1050166.69       852468.48
#Sta/Elev= 30
  4649.4 2430.03    4685 2417.42  4699.4 2410.98  4711.2 2404.61  4738.2 2396.88
  4747.8 2394.93  4779.3 2385.25  4796.8  2382.1  4825.8 2374.35  4868.7 2365.63
  4877.6 2363.25  4882.5 2362.91  4900.2 2359.64  4932.4 2355.33  4954.3 2349.59
  4971.3 2342.94  4976.5 2341.15  4981.9 2340.37  5018.1 2340.37  5020.8  2343.7
  5038.3 2348.12  5065.5 2360.38  5121.9  2368.6  5151.6    2372  5183.1 2374.63
  5205.7 2377.18  5224.7  2381.3  5239.8 2386.13  5252.7 2386.69  5267.5 2391.71
#Mann= 5 ,-1 , 0
  4649.4     .09       0  4971.3     .05       0  5020.8     .09       0
  5065.5     .05       0  5224.7     .09       0
Bank Sta=4971.3,5020.8
Exp/Cntr=0.3,0.1

Type RM Length L Ch R = 1 ,1590    ,567,567,567
BEGIN DESCRIPTION:
Little_Rock_Crk_04
END DESCRIPTION:
XS GIS Cut Line= 2
       1049809.6       852026.37      1049894.62       852505.32
#Sta/Elev= 30
  4802.7 2418.83  4824.5 2409.54  4835.6 2403.48  4842.4 2400.51    4847 2399.11
  4859.9 2391.95  4882.6 2381.41  4888.5 2378.89  4892.1 2377.96  4896.9 2376.02
  4934.7 2359.53  4956.5 2347.04  4972.4 2336.98  4975.5 2335.69  4981.9 2335.25
  5018.1 2335.25  5030.3 2338.14  5042.3 2341.47  5062.7 2343.84  5105.8 2348.14
  5145.3  2348.6  5167.4 2349.43  5180.2 2350.38  5211.3 2356.46  5225.7 2361.05
  5245.1 2369.47    5264 2376.49    5277 2382.55  5287.7 2388.67  5289.1 2388.83
#Mann= 5 ,-1 , 0
  4802.7     .09       0  4972.4     .05       0  5030.3     .09       0
  5062.7     .05       0  5180.2     .09       0
Bank Sta=4972.4,5030.3
Exp/Cntr=0.3,0.1

Type RM Length L Ch R = 1 ,1023    ,433,433,433
BEGIN DESCRIPTION:
Little_Rock_Crk_03
END DESCRIPTION:
XS GIS Cut Line= 2
      1049475.19       851924.34      1049322.15       852508.16
#Sta/Elev= 30
  4452.6 2392.27  4462.4 2389.41  4482.5 2384.71    4497 2379.94  4515.3 2376.03
  4523.9 2374.53  4533.7 2371.27  4602.1 2362.38  4610.2 2361.73  4639.4 2360.68
  4694.4 2355.31  4741.9 2349.12  4777.2 2341.68  4787.7 2339.77  4800.4 2338.05
  4809.1 2337.14  4826.6 2337.42  4878.2 2336.55    4890 2335.95  4917.2 2333.51
  4932.4  2332.5  4969.4    2334  4976.5 2331.73  4981.1 2329.29  4981.9 2325.95
  5018.1 2325.95  5028.6 2331.59  5052.1 2366.81  5053.6 2369.66  5056.2 2372.81
#Mann= 3 ,-1 , 0
  4452.6     .09       0  4981.1     .05       0  5028.6     .09       0
Bank Sta=4981.1,5028.6
Exp/Cntr=0.3,0.1

Type RM Length L Ch R = 1 ,590     ,520,520,520
BEGIN DESCRIPTION:
Little_Rock_Crk_02
END DESCRIPTION:
XS GIS Cut Line= 2
      1049299.47       851810.98      1049078.42       852224.75
#Sta/Elev= 30
  4685.4 2411.27  4688.9 2408.97  4716.2 2389.36  4718.1 2388.28  4734.8 2381.18
  4751.7 2369.98  4764.7 2364.91  4776.4  2361.2  4801.2 2354.34  4823.1 2350.35
  4861.7 2346.42  4872.2 2344.92  4886.3 2343.59  4910.6 2340.54  4935.8 2338.06
  4948.2 2337.35  4952.2 2335.99  4976.1  2324.2  4981.9 2320.12  5018.1 2320.12
  5023.2 2324.18  5036.7 2325.95  5049.3 2327.25  5064.2 2327.65  5080.6 2326.95
  5101.5 2323.86  5106.8 2323.65  5116.9 2323.78  5152.9 2338.87  5154.5 2339.77
#Mann= 3 ,-1 , 0
  4685.4     .09       0  4976.1     .05       0  5023.2     .09       0
Bank Sta=4976.1,5023.2
Exp/Cntr=0.3,0.1

Type RM Length L Ch R = 1 ,70      ,0,0,0
BEGIN DESCRIPTION:
Little_Rock_Crk_01
END DESCRIPTION:
XS GIS Cut Line= 3
      1048672.21       851630.83       1048679.2       851875.44
      1049028.63       852196.92
#Sta/Elev= 30
  4712.9 2397.16  4726.3 2387.95  4747.2 2377.06  4757.7 2369.91  4767.5 2365.77
  4784.8 2355.22  4827.7 2335.49  4855.4 2328.35  4880.3 2324.36  4898.9 2322.48
  4915.7 2319.57  4932.7 2319.22  4952.1 2316.68  4962.2 2316.51  4987.9 2312.99
  4999.9 2312.36    5014 2313.21  5025.6 2314.52  5044.8 2319.34  5078.6 2321.83
  5093.9 2323.76  5188.8 2326.73  5256.6 2332.59  5300.2 2334.35  5324.3 2334.47
  5338.7 2335.59  5354.6 2334.99  5414.7 2345.99  5423.6  2345.9  5432.4 2346.93
#Mann= 3 ,-1 , 0
  4712.9     .09       0  4987.9     .05       0    5014     .09       0
Bank Sta=4987.9,5014
Exp/Cntr=0.3,0.1
Stream Node=Little Rock Cree,Reach-1         , 0 , 0 ,Upstream end
Stream Node=Little Rock Cree,Reach-1         , 0 , 1 ,Downstream end

Chan Stop Cuts=-1
Use User Specified Reach Order=0
User Specified Reach Order=Little Rock Cree,Reach-1