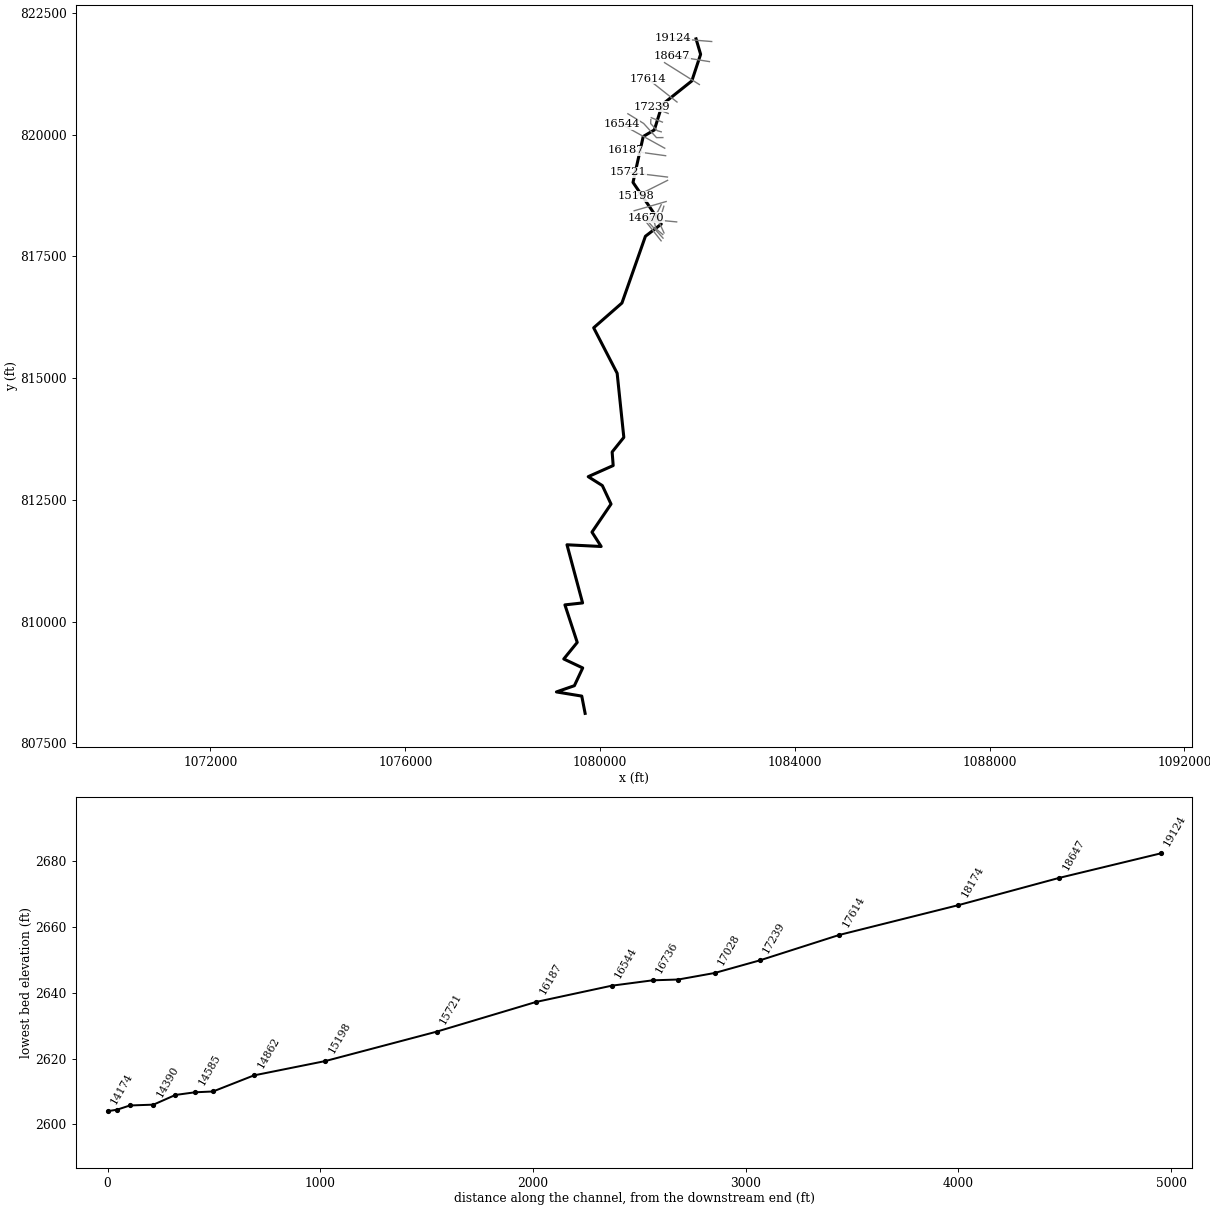
--- lds_bear_crk.prj (project) ---

Proj Title=Bear Creek Limited Detail Study
Current Plan=p01
Default Exp/Contr=0.3,0.1
English Units
Geom File=g01
Flow File=f01
Plan File=p01
Y Axis Title=Elevation
X Axis Title(PF)=Main Channel Distance
X Axis Title(XS)=Station
BEGIN DESCRIPTION:
Bear Creek
END DESCRIPTION:
DSS Export Rating Curves= 0
DSS Export Rating Curve Sorted= 0
DSS Export Volume Flow Curves= 0
DXF OffsetX= 0
DXF OffsetY= 0
DXF ScaleX= 1
DXF ScaleY= 10

--- lds_bear_crk.p01 (plan) ---

Plan Title=Floodway Run
Program Version=3.13
Short Identifier=Floodway
Geom File=g01
Flow File=f01
Subcritical Flow
K Sum by GR= 0
Std Step Tol= 0.01
Critical Tol= 0.01
Num of Std Step Trials= 20
Max Error Tol= 0.3
Flow Tol Ratio= 0.001
Split Flow NTrial= 30
Split Flow Tol= 0.02
Split Flow Ratio= 0.02
Log Output Level= 0
Friction Slope Method= 1
Unsteady Friction Slope Method= 2
Unsteady Bridges Friction Slope Method= 1
Parabolic Critical Depth
Global Vel Dist= 0 , 0 , 0
Global Log Level= 0
CheckData=True
Encroach Param=-1 ,10,10, 2
Encroach River=Bear Creek
Encroach Reach=Reach-1
Encroach Node=19124
       1    4975    5018
Encroach Node=18647
       1    4972    5045
Encroach Node=18174
       4      .7
Encroach Node=17614
       1    4972    5029
Encroach Node=17239
       1  4961.5  5035.5
Encroach Node=17028
       1    4983  5052.1
Encroach Node=16857
       4      .7
Encroach Node=16736
       1    4960    5040
Encroach Node=16544
       1    4940    5035
Encroach Node=16187
       1    4852    5017
Encroach Node=15721
       1    4900    5035
Encroach Node=15198
       1    4940    5035
Encroach Node=14862
       1    4970    5050
Encroach Node=14670
       1    4962    5030
Encroach Node=14585
       14964.9995023.551
Encroach Node=14493
       14929.999 5042.86
Encroach Node=14390
       14939.9995060.001
Encroach Node=14279
       1    4974    5040
Encroach Node=14219
       1    4970  5058.5
Encroach Node=14174
       14963.9995046.001
Encroach Node=13919
       1    4973  5026.5
Encroach Node=13653
       1    4981    5019
Encroach Node=13184
       1    4947    5030
Encroach Node=12731
       1    4890    5026
Encroach Node=12485
       1    4955  5024.2
Encroach Node=12319
       1    4970  5025.5
Encroach Node=12122
       1  4976.2    5045
Encroach Node=11753
       4      .7
Encroach Node=11219
       4      .7
Encroach Node=10687
       1    4980    5040
Encroach Node=10377
       1 4969.23 5028.66
Encroach Node=10222
       1    4968    5030
Encroach Node=9976
       1    4978    5022
Encroach Node=9503
       1    4975    5022
Encroach Node=8872
       1    4978    5021
Encroach Node=8418
       1    4950    5050
Encroach Node=7973
       1    4940    5021
Encroach Node=7411
       4      .7
Encroach Node=6859
       4      .7
Encroach Node=6466
       4      .7
Encroach Node=6095
       1  4986.5    5025
Encroach Node=5712
       4      .7
Encroach Node=5297
       4      .7
Encroach Node=4954
       4      .7
Encroach Node=4503
       4      .7
Encroach Node=3977
       4      .7
Encroach Node=3597
       4      .7
Encroach Node=3322
       4      .7
Encroach Node=2891
       4      .7
Encroach Node=2514
       4      .7
Encroach Node=2268
       1    4972    5030
Encroach Node=1907
       4      .7
Encroach Node=1517
       4      .7
Encroach Node=1251
       4      .7
Encroach Node=945
       1    4960    5024
Encroach Node=674
       4      .7
Encroach Node=480
       1    4975    5040
Encroach Node=330
       1    4978    5022
Encroach Node=187
       1    4968    5022
Encroach Node=126
       1    4968    5028
Encroach Node=83
       1    4955    5035
BEGIN DESCRIPTION:
Floodway Run
END DESCRIPTION:
Computation Interval=1HOUR
Output Interval=1HOUR
Run HTab= 0
Run UNet= 0
Run PostProcess= 0
UNET Theta= 1
UNET Theta Warmup= 1
UNET ZTol= 0.02
UNET ZSATol= 0.05
UNET MxIter= 20
UNET MaxInSteps= 0
UNET DtIC= 0
UNET DtMin= 0
UNET MaxCRTS= 20
UNET WFStab= 2
UNET SFStab= 1
UNET WFX= 1
UNET SFX= 1
UNET DSS MLevel= 4
UNET DZMax Abort= 100
UNET Convert EG Bridges=-1
UNET Use Existing IB Tables=-1
UNET Froude Reduction=False
UNET Froude Limit= 1
UNET Froude Power= 10
Instantaneous Interval=1HOUR
Write IC File= 0
Echo Input=False
Echo Output=False
Write Detailed= 0
Detailed Automatic Start=False, 10

--- lds_bear_crk.f01 (steady flow) ---

Flow Title=Floodway
Program Version=3.13
Number of Profiles= 2
Profile Names=100-year,100-FW
River Rch & RM=Bear Creek,Reach-1         ,19124
    1650    1650
River Rch & RM=Bear Creek,Reach-1         ,18647
    1750    1750
River Rch & RM=Bear Creek,Reach-1         ,16544
    2110    2110
River Rch & RM=Bear Creek,Reach-1         ,14862
    2360    2360
River Rch & RM=Bear Creek,Reach-1         ,14493
    2540    2540
River Rch & RM=Bear Creek,Reach-1         ,11219
    2700    2700
River Rch & RM=Bear Creek,Reach-1         ,8872
    2910    2910
Boundary for River Rch & Prof#=Bear Creek,Reach-1         , 1
Up Type= 0
Dn Type= 3
Dn Slope=0.01505
Boundary for River Rch & Prof#=Bear Creek,Reach-1         , 2
Up Type= 0
Dn Type= 3
Dn Slope=0.01505
DSS Import GetInterval= 0
DSS Import GetPeak= 0
DSS Import FillOption= 0

--- lds_bear_crk.g01 (geometry) ---

Geom Title=Existing Conditions
Program Version=3.13

River Reach=Bear Creek      ,Reach-1
Reach XY= 30
      1081971.45       821967.11      1082065.08       821649.23
      1081884.69       821103.18      1081277.57       820618.94
      1081114.87       820096.55      1080886.47       819961.42
      1080676.91       819019.45      1081257.39       818163.41
      1080931.52       817912.99      1080449.54       816542.48
      1079869.07       816033.76      1080351.16       815099.77
      1080488.24       813783.22      1080248.35       813483.36
      1080269.77       813204.92      1079756.89       812976.48
      1080047.01       812793.68       1080225.5       812413.85
       1079834.2       811838.14       1080023.2       811542.52
      1079320.98       811577.98      1079641.38       810383.76
      1079278.61       810343.72      1079531.56       809573.22
      1079255.03       809232.88      1079643.78       809048.78
        1079473.       808684.31      1079103.97       808556.18
      1079624.53       808470.71      1079693.38       808115.78

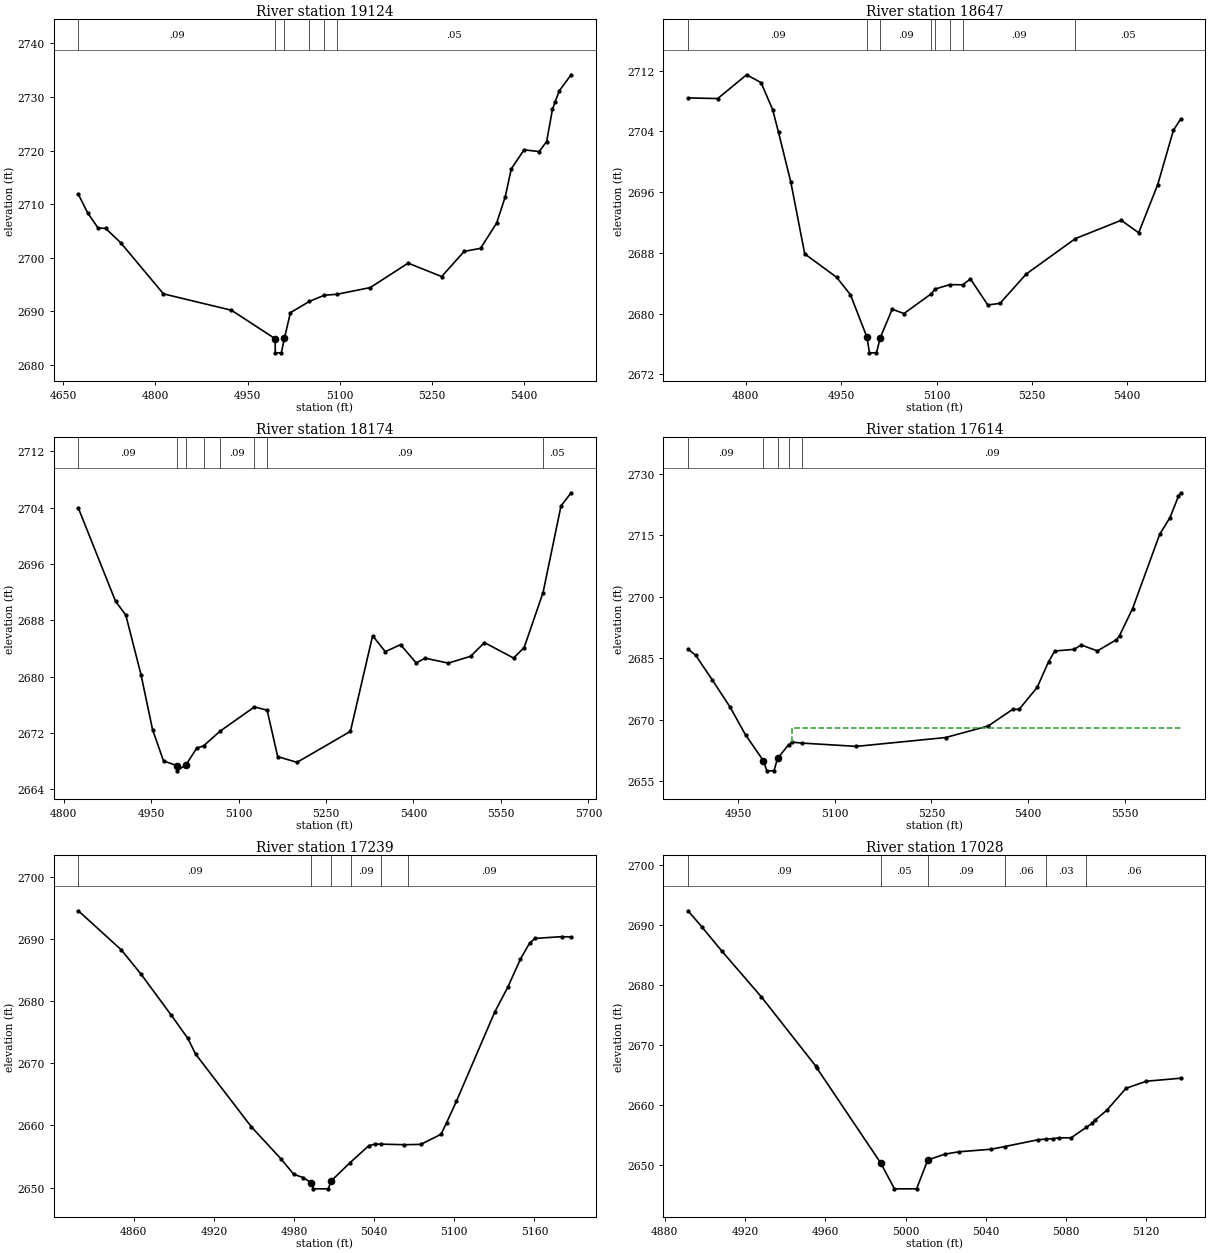
Type RM Length L Ch R = 1 ,19124   ,477,477,477
BEGIN DESCRIPTION:
bear_crk_xs_0
END DESCRIPTION:
XS GIS Cut Line= 2
      1082292.57       821911.99      1081492.92       821977.59
#Sta/Elev= 30
  4674.4 2711.83  4689.7 2708.34  4706.6 2705.55  4718.6 2705.49  4743.1 2702.85
    4813 2693.28  4923.7 2690.23  4994.9 2684.92    4995 2682.29    5005 2682.29
  5009.9 2684.98  5019.7 2689.78  5050.5 2691.87    5075 2693.03    5095  2693.2
  5149.7 2694.45  5211.4 2699.01    5266 2696.51  5302.7  2701.2  5329.3 2701.77
  5355.5 2706.46  5369.5 2711.35  5379.4 2716.58  5400.2 2720.13  5424.8 2719.81
    5437 2721.67  5446.4 2727.66  5450.7 2729.02  5457.5 2731.12  5476.8 2734.12
#Mann= 6 ,-1 , 0
  4674.4     .09       0  4994.9     .05       0  5009.9     .09       0
  5050.5     .05       0    5075     .03       0    5095     .05       0
Bank Sta=4994.9,5009.9
Exp/Cntr=0.3,0.1

Type RM Length L Ch R = 1 ,18647   ,473,473,473
BEGIN DESCRIPTION:
bear_crk_xs_1
END DESCRIPTION:
XS GIS Cut Line= 2
      1082245.72       821499.67      1081480.42       821621.49
#Sta/Elev= 30
  4709.2  2708.4  4755.8 2708.31  4801.3 2711.44    4824 2710.41  4842.3 2706.84
  4851.5 2703.86  4870.9 2697.28  4892.7 2687.87  4942.8  2684.8  4964.5 2682.51
  4990.7 2676.88  4994.5 2674.85  5005.5 2674.85  5011.5 2676.84  5030.2 2680.59
  5048.8 2680.02  5091.8 2682.63  5097.5 2683.24  5121.1 2683.83  5141.1  2683.8
  5153.3 2684.57  5180.6 2681.15  5199.8 2681.36    5241 2685.22  5318.3 2689.88
  5390.4 2692.29  5417.9 2690.65  5447.8 2696.98  5472.5 2704.13  5484.1 2705.65
#Mann= 8 ,-1 , 0
  4709.2     .09       0  4990.7     .05       0  5011.5     .09       0
  5091.8     .05       0  5097.5     .09       0  5121.1     .03       0
  5141.1     .09       0  5318.3     .05       0
Bank Sta=4990.7,5011.5
Exp/Cntr=0.3,0.1

Type RM Length L Ch R = 1 ,18174   ,560,560,560
BEGIN DESCRIPTION:
bear_crk_xs_2
Ineffective flow area due to road blocking
END DESCRIPTION:
XS GIS Cut Line= 2
      1082039.56       821028.94      1081324.24       821478.74
#Sta/Elev= 30
  4825.4 2703.95  4889.2 2690.69  4906.7 2688.75  4932.8 2680.27  4952.6 2672.46
  4971.4    2668  4994.4 2667.33  4994.5 2666.59  5009.8 2667.43  5028.2 2669.79
  5040.5 2670.17  5068.4 2672.23  5127.3 2675.68  5149.1 2675.21  5167.2 2668.61
  5200.3  2667.8  5291.9  2672.2    5330 2685.81  5351.6 2683.54  5377.9 2684.53
  5404.7 2681.93  5420.1 2682.61  5459.7 2681.91  5497.9 2682.87  5521.7 2684.83
  5571.7 2682.63  5589.8 2684.12  5622.2 2691.93    5653 2704.25  5670.3 2706.13
#Mann= 8 ,-1 , 0
  4825.4     .09       0  4994.4     .05       0  5009.8     .09       0
  5040.5     .03       0  5068.4     .09       0  5127.3     .03       0
  5149.1     .09       0  5622.2     .05       0
#XS Ineff= 2 , 0
       0                    5125       0    2675
Permanent Ineff=
       F       F
Bank Sta=4994.4,5009.8
Exp/Cntr=0.3,0.1

Type RM Length L Ch R = 1 ,17614   ,375,375,375
BEGIN DESCRIPTION:
bear_crk_xs_3
Ineffective flow area due to road blocking
END DESCRIPTION:
XS GIS Cut Line= 2
      1081580.38       820669.72      1080980.64       821144.51
#Sta/Elev= 30
  4872.1 2687.29  4884.1  2685.7    4910 2679.68  4937.5 2673.06  4961.3 2666.33
  4989.2 2659.98  4994.5 2657.54  5005.5 2657.54    5011 2660.57  5028.2 2663.92
    5034 2664.54  5049.7 2664.31  5133.4 2663.51  5271.9 2665.67    5338 2668.49
  5375.9 2672.53  5386.1 2672.56  5414.1 2677.92  5431.7 2684.16  5441.4 2686.79
  5471.3 2687.19  5482.5 2688.26  5507.6 2686.82    5537 2689.54  5541.9 2690.55
  5562.2 2697.15  5604.2 2715.25  5620.2 2719.34  5633.3 2724.54    5637 2725.41
#Mann= 5 ,-1 , 0
  4872.1     .09       0  4989.2     .05       0    5011     .09       0
  5028.2     .03       0  5049.7     .09       0
#XS Ineff= 2 , 0
       0                    5034       0    2668
Permanent Ineff=
       F       F
Bank Sta=4989.2,5011
Exp/Cntr=0.3,0.1

Type RM Length L Ch R = 1 ,17239   ,211,211,211
BEGIN DESCRIPTION:
bear_crk_xs_4
END DESCRIPTION:
XS GIS Cut Line= 2
      1081399.21       820435.45      1081055.61       820569.76
#Sta/Elev= 30
  4818.5 2694.52  4850.7 2688.22  4865.4 2684.33  4888.2 2677.68  4900.5 2673.98
  4906.2 2671.49    4948 2659.77  4970.2 2654.61  4979.8 2652.12  4986.9  2651.6
 4993.01 2650.73  4994.5 2649.79  5005.5 2649.79 5007.95  2651.1 5021.81 2653.98
 5035.94 2656.73  5040.7 2656.99  5044.9 2656.98 5062.59 2656.89 5074.93 2656.94
    5090 2658.57  5094.2 2660.43  5101.6 2663.91  5130.1 2678.17    5140 2682.23
  5149.5 2686.75  5156.3 2689.32  5160.4 2690.07  5180.3 2690.36  5187.4 2690.31
#Mann= 6 ,-1 , 0
  4818.5     .09       0 4993.01     .05       0 5007.95     .06       0
  5022.4     .09       0  5044.9     .03       0    5065     .09       0
Bank Sta=4993.01,5007.95
Exp/Cntr=0.3,0.1

Type RM Length L Ch R = 1 ,17028   ,171,171,171
BEGIN DESCRIPTION:
bear_crk_xs_5
END DESCRIPTION:
XS GIS Cut Line= 2
      1081280.51        820257.4      1081052.28       820347.97
#Sta/Elev= 26
  4891.6  2692.3  4898.5 2689.61  4908.6 2685.52  4928.2 2677.94  4955.3 2666.41
  4955.8 2666.11  4987.6  2650.3  4994.5 2645.98  5005.5 2645.98  5011.1 2650.79
  5019.6 2651.76  5026.6 2652.15  5042.6 2652.58  5049.4 2653.02  5066.1 2654.16
  5070.1 2654.27  5073.4 2654.33  5076.4 2654.48  5082.5 2654.48  5090.1 2656.22
  5093.1 2656.91  5094.3 2657.38  5100.3 2659.06  5109.9 2662.73  5120.1 2663.91
  5137.2 2664.41
#Mann= 6 ,-1 , 0
  4891.6     .09       0  4987.6     .05       0  5011.1     .09       0
  5049.4     .06       0  5070.1     .03       0  5090.1     .06       0
Bank Sta=4987.6,5011.1
Exp/Cntr=0.5,0.3

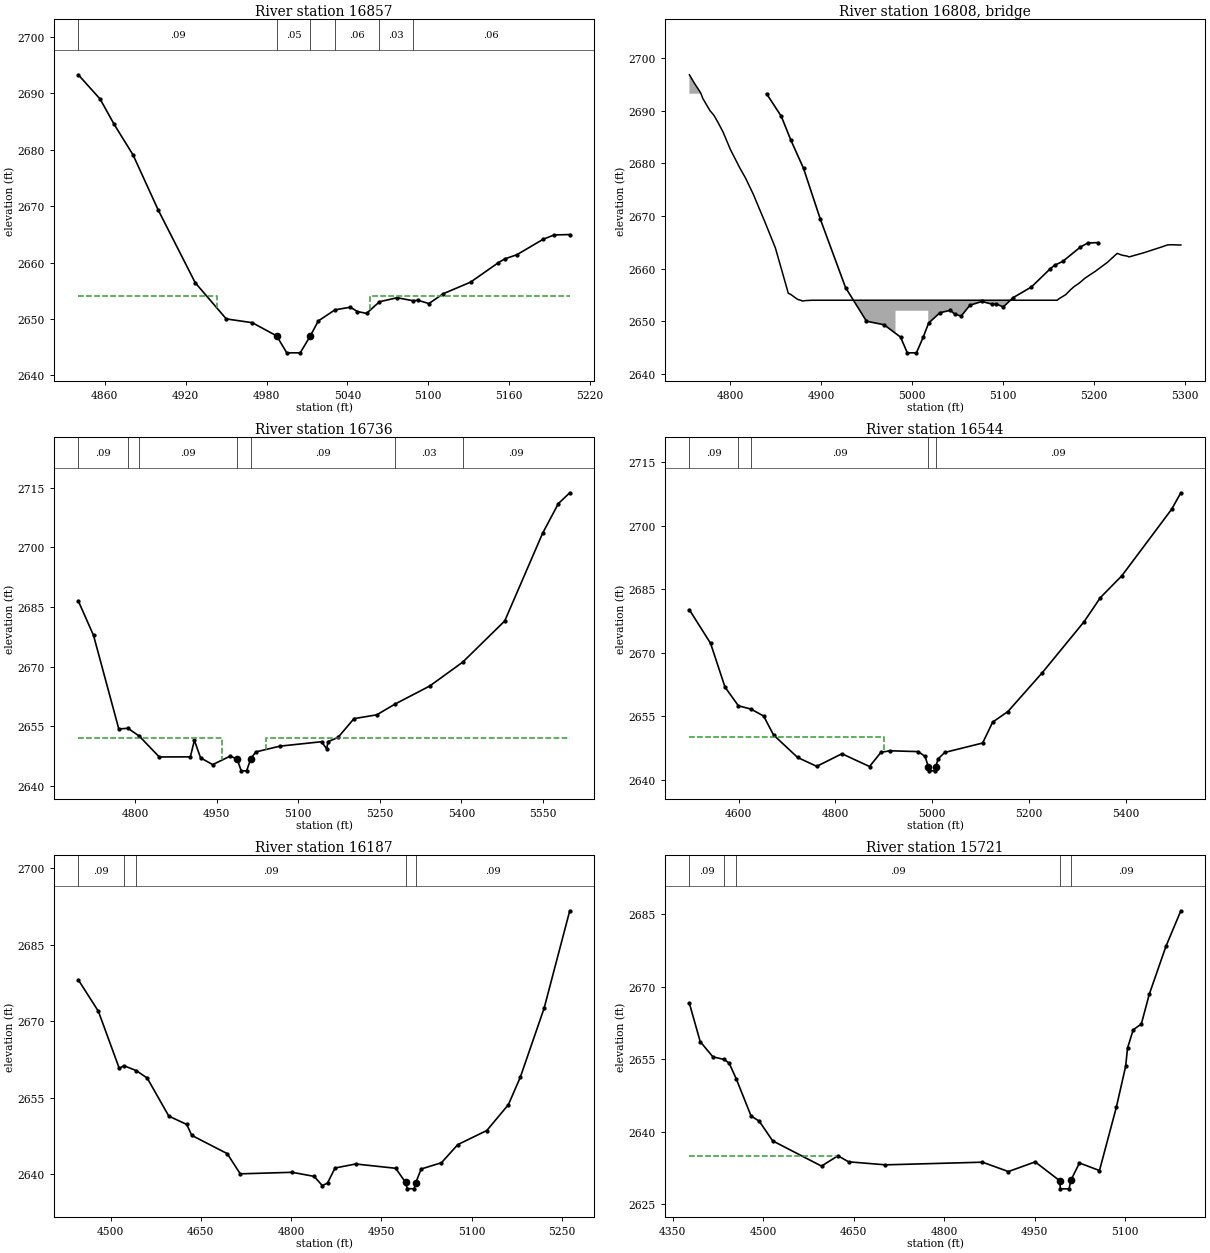
Type RM Length L Ch R = 1 ,16857   ,121,121,121
BEGIN DESCRIPTION:
bear_crk_xs_9
END DESCRIPTION:
XS GIS Cut Line= 4
      1081256.69       820057.98      1081174.49       820081.65
      1081039.45       820227.71      1081042.66       820307.89
#Sta/Elev= 30
  4840.3 2693.25  4856.5 2688.95  4866.9 2684.47  4880.9 2679.07  4899.5 2669.35
  4927.1 2656.41  4950.1 2650.01  4969.4 2649.34  4987.5    2647    4995    2644
    5005    2644  5012.5    2647  5018.4 2649.65  5030.8 2651.62  5042.2 2652.08
  5047.4 2651.32  5054.2 2650.99  5063.8 2653.05  5076.9 2653.76  5088.4 2653.24
  5092.3 2653.31  5100.5 2652.73  5111.2 2654.48  5131.4 2656.52  5152.1 2659.98
  5156.8 2660.64  5165.8 2661.38  5185.3 2664.12  5193.4 2664.88    5205 2664.95
#Mann= 6 ,-1 , 0
  4840.3     .09       0  4987.5     .05       0  5012.5     .09       0
  5030.8     .06       0  5063.8     .03       0  5088.4     .06       0
#XS Ineff= 2 , 0
       0    4943    2654    5057       0    2654
Permanent Ineff=
       F       F
Bank Sta=4987.5,5012.5
Exp/Cntr=0.5,0.3

Type RM Length L Ch R = 3 ,16808   ,,,
BEGIN DESCRIPTION:
bear_crk_xs_6
Structure ID: State_BR_Hamburg_Rd
Approximate Survey Structure
END DESCRIPTION:
Bridge Culvert--1,0,-1,-1, 0
Deck Dist Width WeirC Skew NumUp NumDn MinLoCord MaxHiCord MaxSubmerge Is_Ogee
39,20,3,0, 54, 54, , , , 0, 1,1,,
  4755.5  4760.4  4767.9  4770.2    4778  4782.5  4786.9  4789.2  4792.4  4800.6
  4810.7  4817.4  4825.8  4826.5    4827  4838.4    4850  4862.6  4864.2  4866.4
  4874.4  4878.6  4879.3  4883.2  4890.5    4982    4982    5018    5018  5159.8
  5161.3  5169.1  5174.5  5178.3  5184.2  5190.3  5200.9  5201.8  5202.2  5215.1
  5224.3  5225.7    5231  5236.5  5238.4  5239.1  5254.9  5276.9  5277.8  5281.5
  5285.6  5290.4  5293.4  5295.6
 2696.85 2695.41 2693.41 2692.37 2690.05 2689.14  2687.8 2687.04    2686 2682.63
 2679.21 2677.15 2674.11 2673.84  2673.6 2668.91 2663.94 2656.29  2655.3 2655.16
 2654.16 2653.96 2653.85 2653.93    2654    2654    2654    2654    2654    2654
 2654.24 2655.06 2656.01 2656.59 2657.29  2658.2 2659.42  2659.5 2659.57 2661.23
  2662.7  2662.9 2662.56 2662.39 2662.25 2662.25 2663.02 2664.26 2664.33 2664.53
 2664.54 2664.52 2664.49  2664.5
    2624    2624    2624    2624    2624    2624    2624    2624    2624    2624
    2624    2624    2624    2624    2624    2624    2624    2624    2624    2624
    2624    2624    2624    2624    2624    2624    2652    2652    2624    2624
    2624    2624    2624    2624    2624    2624    2624    2624    2624    2624
    2624    2624    2624    2624    2624    2624    2624    2624    2624    2624
    2624    2624    2624    2624
  4755.5  4760.4  4767.9  4770.2    4778  4782.5  4786.9  4789.2  4792.4  4800.6
  4810.7  4817.4  4825.8  4826.5    4827  4838.4    4850  4862.6  4864.2  4866.4
  4874.4  4878.6  4879.3  4883.2  4890.5    4982    4982    5018    5018  5159.8
  5161.3  5169.1  5174.5  5178.3  5184.2  5190.3  5200.9  5201.8  5202.2  5215.1
  5224.3  5225.7    5231  5236.5  5238.4  5239.1  5254.9  5276.9  5277.8  5281.5
  5285.6  5290.4  5293.4  5295.6
 2696.85 2695.41 2693.41 2692.37 2690.05 2689.14  2687.8 2687.04    2686 2682.63
 2679.21 2677.15 2674.11 2673.84  2673.6 2668.91 2663.94 2656.29  2655.3 2655.16
 2654.16 2653.96 2653.85 2653.93    2654    2654    2654    2654    2654    2654
 2654.24 2655.06 2656.01 2656.59 2657.29  2658.2 2659.42  2659.5 2659.57 2661.23
  2662.7  2662.9 2662.56 2662.39 2662.25 2662.25 2663.02 2664.26 2664.33 2664.53
 2664.54 2664.52 2664.49  2664.5
    2624    2624    2624    2624    2624    2624    2624    2624    2624    2624
    2624    2624    2624    2624    2624    2624    2624    2624    2624    2624
    2624    2624    2624    2624    2624    2624    2652    2652    2624    2624
    2624    2624    2624    2624    2624    2624    2624    2624    2624    2624
    2624    2624    2624    2624    2624    2624    2624    2624    2624    2624
    2624    2624    2624    2624
BR Coef= 0 , 1 , 0 ,1.25, 0 ,,,0.8,-1,2,6,
WSPro=,,,, 1 ,,,, 0 ,,,, 0 ,,,,-1 ,-1 ,-1 , 0 , 0 , 0 , 0 , 0
BC Design=,, 0 ,, 0 ,,,,,,
BC HTab HWMax=2693.25

Type RM Length L Ch R = 1 ,16736   ,192,192,192
BEGIN DESCRIPTION:
bear_crk_xs_7
END DESCRIPTION:
XS GIS Cut Line= 4
      1081289.59       819939.73      1081159.71       819938.13
      1080895.14       820229.96      1080571.24       820428.79
#Sta/Elev= 30
  4695.4 2686.52  4723.4 2677.85  4769.9 2654.29  4786.7 2654.46  4807.3 2652.52
  4844.4 2647.24  4901.5 2647.27  4908.9 2651.43  4920.3 2647.02  4942.6 2645.32
  4974.6 2647.44  4987.5 2646.75    4995 2643.75    5005 2643.75  5012.5 2646.75
  5021.6  2648.5  5066.5 2649.97  5142.8 2651.08  5152.1  2649.3    5155  2651.1
  5173.3 2652.18  5202.4 2656.89  5244.3 2657.85  5278.4 2660.59  5341.6 2665.09
  5402.4 2671.11  5479.7 2681.48  5549.4 2703.56  5578.3 2711.01  5599.3 2713.75
#Mann= 7 ,-1 , 0
  4695.4     .09       0  4786.7     .03       0  4807.3     .09       0
  4987.5     .05       0  5012.5     .09       0  5278.4     .03       0
  5402.4     .09       0
#XS Ineff= 2 , 0
       0    4960    2652    5040       0    2652
Permanent Ineff=
       F       F
Bank Sta=4987.5,5012.5
Exp/Cntr=0.5,0.3

Type RM Length L Ch R = 1 ,16544   ,357,357,357
BEGIN DESCRIPTION:
bear_crk_xs_8, LOB ineffective flow due to upstream expansion
END DESCRIPTION:
XS GIS Cut Line= 2
      1081328.37       819721.47      1080438.95       820213.16
#Sta/Elev= 30
  4497.9 2680.16  4541.7 2672.24  4571.5 2661.91  4599.2 2657.49  4625.4  2656.7
  4651.4 2655.07    4672 2650.58  4721.7 2645.28  4761.3 2643.18  4813.3 2646.16
  4870.4 2643.14  4894.1  2646.5  4912.8 2646.86  4971.2 2646.66  4985.3 2645.52
 4992.16 2643.02 4993.12 2642.12 5006.38 2642.12 5007.35 2643.05  5012.2 2644.94
  5025.8 2646.46  5104.3 2648.69  5125.1 2653.64  5156.5 2656.12  5227.6  2665.3
  5314.1 2677.35  5347.9 2683.06  5392.2  2688.2  5495.1 2703.91  5514.2 2707.81
#Mann= 5 ,-1 , 0
  4497.9     .09       0  4599.2     .03       0  4625.4     .09       0
 4992.16    .045       0 5007.35     .09       0
#XS Ineff= 2 , 0
       0    4900    2650               0
Permanent Ineff=
       F       F
Bank Sta=4992.16,5007.35
Exp/Cntr=0.3,0.1

Type RM Length L Ch R = 1 ,16187   ,466,466,466
BEGIN DESCRIPTION:
bear_crk_xs_10
END DESCRIPTION:
XS GIS Cut Line= 2
      1081346.72       819567.26      1080538.02       819679.36
#Sta/Elev= 30
  4446.4 2678.13  4479.8 2671.95  4514.5 2660.76    4522  2661.3  4542.8 2660.33
  4560.9 2658.87  4596.8 2651.41  4626.5 2649.79  4634.9 2647.64  4693.8 2644.06
  4715.5  2640.1  4801.8  2640.4  4838.3  2639.6  4851.8 2637.79  4860.5  2638.3
  4872.9 2641.24  4907.2 2642.03  4973.7 2641.19 4990.17 2638.42  4992.8 2637.21
 5004.35 2637.16 5006.75 2638.28 5016.12 2641.05  5049.8 2642.28  5076.9 2645.83
  5125.1 2648.59    5161 2653.66  5180.8 2659.05  5220.3 2672.55  5262.9 2691.66
#Mann= 5 ,-1 , 0
  4446.4     .09       0    4522     .03       0  4542.8     .09       0
 4990.17     .05       0 5006.75     .09       0
Bank Sta=4990.17,5006.75
Exp/Cntr=0.3,0.1

Type RM Length L Ch R = 1 ,15721   ,523,523,523
BEGIN DESCRIPTION:
bear_crk_xs_11
END DESCRIPTION:
XS GIS Cut Line= 2
      1081384.09       819129.02      1080575.39       819227.77
#Sta/Elev= 30
  4377.8 2666.57  4395.7 2658.65  4416.8  2655.5  4435.6 2654.95  4443.8 2654.17
  4455.8 2650.84  4480.1 2643.23  4493.5 2642.19  4515.8  2638.1  4596.8 2632.87
  4624.1 2635.01  4641.6 2633.76  4702.8 2633.13  4863.6 2633.68  4906.6 2631.74
    4951 2633.74  4991.6 2629.85  4992.8 2628.16  5007.2 2628.16 5010.15 2629.92
  5024.4 2633.52  5057.6 2631.95  5085.5 2645.02    5101 2653.54  5104.1  2657.3
  5113.5 2661.09    5127 2662.31  5140.3 2668.51  5167.9 2678.42  5192.5 2685.75
#Mann= 5 ,-1 , 0
  4377.8     .09       0  4435.6     .03       0  4455.8     .09       0
  4991.6     .05       0 5010.15     .09       0
#XS Ineff= 2 , 0
       0    4620    2635               0
Permanent Ineff=
       F       F
Bank Sta=4991.6,5010.15
Exp/Cntr=0.3,0.1

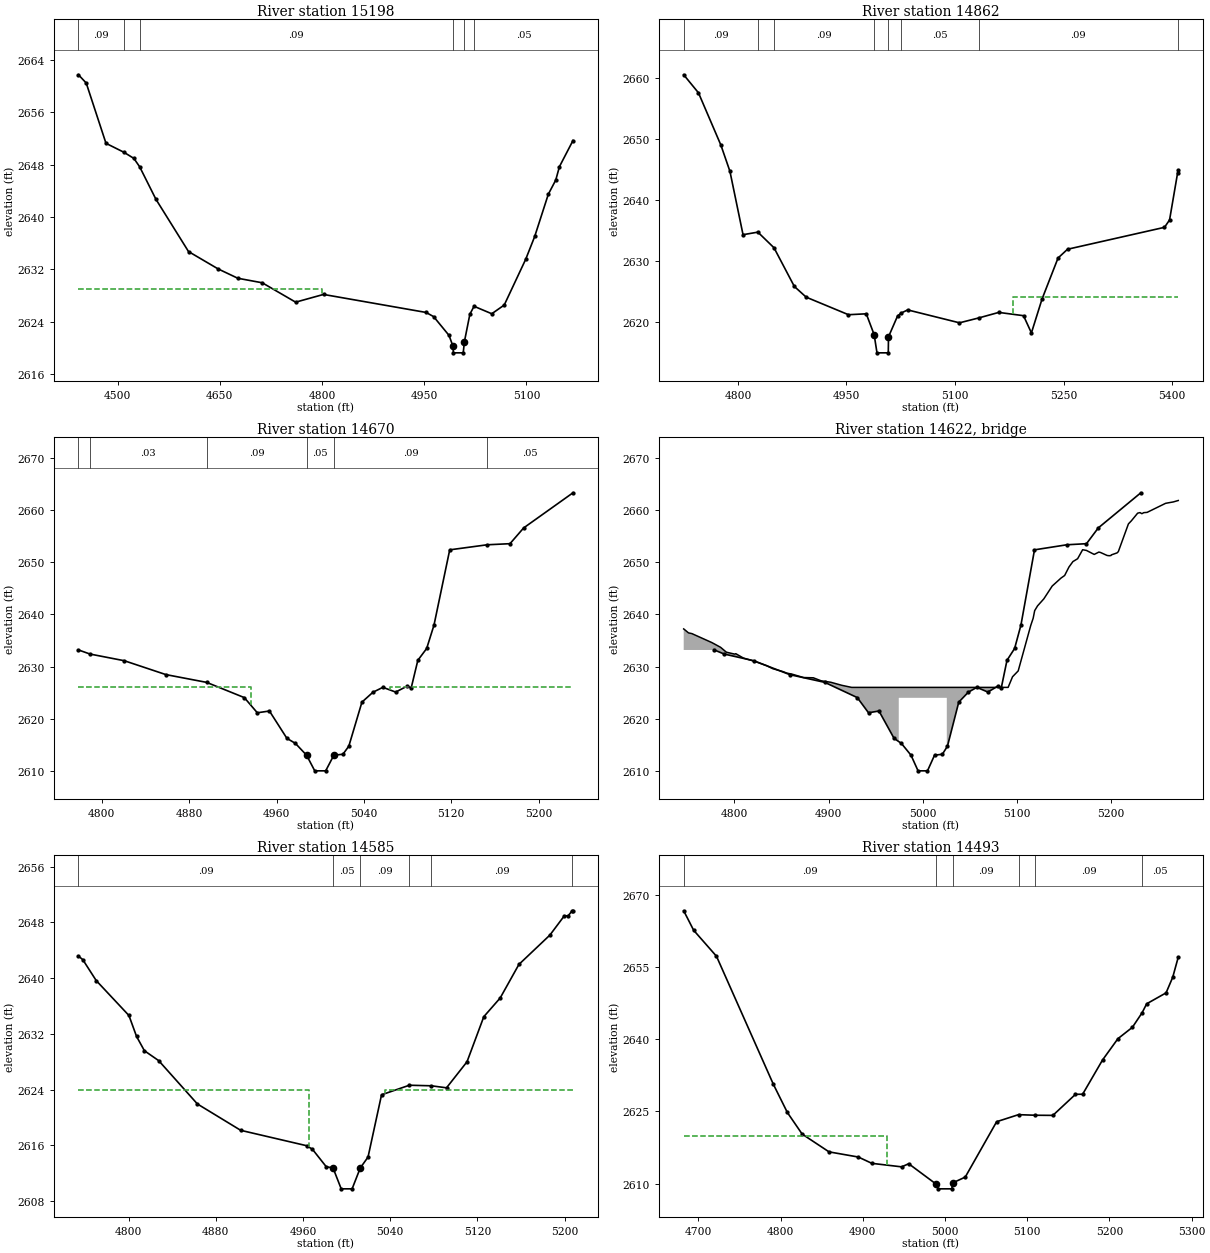
Type RM Length L Ch R = 1 ,15198   ,336,336,336
BEGIN DESCRIPTION:
bear_crk_xs_13
END DESCRIPTION:
XS GIS Cut Line= 2
      1081386.76       819061.49       1080738.2       818735.88
#Sta/Elev= 30
  4442.6 2661.71    4454 2660.45    4483 2651.24  4509.2 2649.88  4523.9 2648.94
  4532.4 2647.66  4556.3 2642.69  4604.1 2634.71  4647.5 2632.06  4676.5 2630.63
  4712.3 2629.94  4761.3 2626.98  4802.2 2628.16  4952.7 2625.41  4963.8 2624.77
  4986.4  2621.9  4992.2 2620.24  4992.8 2619.24  5007.2 2619.24    5009 2620.97
    5017 2625.15  5023.1 2626.35  5049.1 2625.21  5067.4 2626.54  5098.9 2633.53
  5112.1 2637.01  5132.1 2643.47    5143 2645.63  5148.4 2647.68  5168.3 2651.67
#Mann= 6 ,-1 , 0
  4442.6     .09       0  4509.2     .03       0  4532.4     .09       0
  4992.2     .05       0    5009     .09       0  5023.1     .05       0
#XS Ineff= 2 , 0
       0    4800    2629               0
Permanent Ineff=
       F       F
Bank Sta=4992.2,5009
Exp/Cntr=0.3,0.1

Type RM Length L Ch R = 1 ,14862   ,192,192,192
BEGIN DESCRIPTION:
bear_crk_xs_12, ROB ineffective flow due to upstream expansion
END DESCRIPTION:
XS GIS Cut Line= 2
       1081357.4       818626.45      1080700.83       818436.95
#Sta/Elev= 30
  4725.1 2660.54  4745.5 2657.58  4776.5 2648.99    4789 2644.68  4807.1 2634.28
  4827.6  2634.7  4849.9 2632.13    4878 2625.78  4894.4 2624.02  4952.8 2621.14
  4977.4 2621.29  4988.3 2617.86  4992.2 2614.88  5007.8 2614.88  5008.1 2617.51
  5020.6 2620.92  5025.6 2621.41  5034.6 2621.93  5106.2 2619.81  5132.8 2620.61
  5160.5 2621.52  5194.7 2620.98  5205.6 2618.15  5220.3 2623.72  5242.4 2630.45
  5255.5 2631.89  5389.5 2635.49  5396.5  2636.7  5407.5 2644.34  5408.5 2644.91
#Mann= 8 ,-1 , 0
  4725.1     .09       0  4827.6     .03       0  4849.9     .09       0
  4988.3     .05       0  5008.1     .09       0  5025.6     .05       0
  5132.8     .09       0  5407.5     .05       0
#XS Ineff= 2 , 0
       0                    5180       0    2624
Permanent Ineff=
       F       F
Bank Sta=4988.3,5008.1
Exp/Cntr=0.5,0.3

Type RM Length L Ch R = 1 ,14670   ,85,85,85
BEGIN DESCRIPTION:
bear_crk_xs_15
END DESCRIPTION:
XS GIS Cut Line= 4
      1081255.23       818560.77      1081189.15       818424.02
      1081098.69       818319.75      1080937.18       818297.39
#Sta/Elev= 30
  4778.6 2633.18  4789.2 2632.39  4820.6 2631.11  4858.7 2628.45    4896 2626.96
  4930.5 2624.04  4942.4 2621.13  4953.5 2621.47  4969.5 2616.23  4977.3 2615.26
  4987.5    2613    4995    2610    5005    2610  5012.5    2613  5020.8 2613.18
  5026.2 2614.73  5038.2 2623.17  5048.3 2625.07  5057.4 2626.01  5069.1  2625.1
  5079.8 2626.26  5083.3 2625.87  5089.4 2631.19  5097.5 2633.46  5104.2 2637.94
  5118.6 2652.37  5152.9 2653.34  5173.8 2653.55  5186.3 2656.57  5231.5 2663.31
#Mann= 6 ,-1 , 0
  4778.6     .09       0  4789.2     .03       0    4896     .09       0
  4987.5     .05       0  5012.5     .09       0  5152.9     .05       0
#XS Ineff= 2 , 0
       0  4936.5    2626  5063.5       0    2626
Permanent Ineff=
       F       F
Bank Sta=4987.5,5012.5
Exp/Cntr=0.5,0.3

Type RM Length L Ch R = 3 ,14622   ,,,
BEGIN DESCRIPTION:
bear_crk_xs_14
Structure ID: State_BR_2_SR1197
Approximate Survey Structure
END DESCRIPTION:
Bridge Culvert--1,0,-1,-1, 0
Deck Dist Width WeirC Skew NumUp NumDn MinLoCord MaxHiCord MaxSubmerge Is_Ogee
38,20,3,0, 60, 60, , , , 0, 1,1,,
  4746.2  4751.3  4754.9  4776.1  4785.3  4791.5  4800.3  4801.5  4809.5  4822.4
  4834.2  4840.7  4851.5  4855.6  4861.4  4873.3  4883.8    4892  4902.4    4914
  4924.5  4974.5  4974.5  5025.5  5025.5  5090.6  5095.3  5101.3  5114.6  5117.2
  5118.8  5121.9  5128.5  5137.4  5146.7  5150.6  5155.2  5159.4  5164.4  5169.7
  5173.7    5182  5186.9  5188.6  5195.7    5198  5199.8  5200.3  5206.3  5207.6
  5218.3  5221.5  5228.1  5230.6  5232.6  5234.6  5238.1  5257.8  5266.1  5271.2
 2637.21 2636.45 2636.31 2634.59 2633.69 2632.75 2632.38 2632.46 2631.63 2630.94
 2630.16 2629.59 2629.03 2628.74 2628.53 2627.89 2627.84 2627.27 2626.98  2626.4
    2626    2626    2626    2626    2626    2626 2628.04 2629.16 2637.86 2639.26
 2640.72 2641.64 2642.97 2645.43 2646.95 2647.45 2649.08 2650.12 2650.67 2652.39
 2652.26 2651.49 2651.94 2651.87 2651.29 2651.24 2651.28 2651.41 2651.79 2652.03
 2657.34 2657.95  2659.4 2659.51  2659.3  2659.5 2659.55 2661.29 2661.56 2661.83
    2590    2590    2590    2590    2590    2590    2590    2590    2590    2590
    2590    2590    2590    2590    2590    2590    2590    2590    2590    2590
    2590    2590    2624    2624    2590    2590    2590    2590    2590    2590
    2590    2590    2590    2590    2590    2590    2590    2590    2590    2590
    2590    2590    2590    2590    2590    2590    2590    2590    2590    2590
    2590    2590    2590    2590    2590    2590    2590    2590    2590    2590
  4746.2  4751.3  4754.9  4776.1  4785.3  4791.5  4800.3  4801.5  4809.5  4822.4
  4834.2  4840.7  4851.5  4855.6  4861.4  4873.3  4883.8    4892  4902.4    4914
  4924.5  4974.5  4974.5  5025.5  5025.5  5090.6  5095.3  5101.3  5114.6  5117.2
  5118.8  5121.9  5128.5  5137.4  5146.7  5150.6  5155.2  5159.4  5164.4  5169.7
  5173.7    5182  5186.9  5188.6  5195.7    5198  5199.8  5200.3  5206.3  5207.6
  5218.3  5221.5  5228.1  5230.6  5232.6  5234.6  5238.1  5257.8  5266.1  5271.2
 2637.21 2636.45 2636.31 2634.59 2633.69 2632.75 2632.38 2632.46 2631.63 2630.94
 2630.16 2629.59 2629.03 2628.74 2628.53 2627.89 2627.84 2627.27 2626.98  2626.4
    2626    2626    2626    2626    2626    2626 2628.04 2629.16 2637.86 2639.26
 2640.72 2641.64 2642.97 2645.43 2646.95 2647.45 2649.08 2650.12 2650.67 2652.39
 2652.26 2651.49 2651.94 2651.87 2651.29 2651.24 2651.28 2651.41 2651.79 2652.03
 2657.34 2657.95  2659.4 2659.51  2659.3  2659.5 2659.55 2661.29 2661.56 2661.83
    2590    2590    2590    2590    2590    2590    2590    2590    2590    2590
    2590    2590    2590    2590    2590    2590    2590    2590    2590    2590
    2590    2590    2624    2624    2590    2590    2590    2590    2590    2590
    2590    2590    2590    2590    2590    2590    2590    2590    2590    2590
    2590    2590    2590    2590    2590    2590    2590    2590    2590    2590
    2590    2590    2590    2590    2590    2590    2590    2590    2590    2590
Abutment Skew #Up #Dn= , 2 , 2
  4974.5  4982.5
    2624 2613.84
  4974.5  4982.5
    2624 2612.89
Abutment Skew #Up #Dn= , 2 , 2
  5017.5  5025.5
  2610.4    2624
  5017.5  5025.5
 2613.84    2624
BR Coef= 0 , 1 , 0 ,1.25, 0 ,,,0.8,0,2,6,
WSPro=,,,, 1 ,,,, 0 ,,,, 0 ,,,,-1 ,-1 ,-1 , 0 , 0 , 0 , 0 , 0
BC Design=,, 0 ,, 0 ,,,,,,
BC HTab HWMax=2663.31

Type RM Length L Ch R = 1 ,14585   ,92,92,92
BEGIN DESCRIPTION:
bear_crk_xs_16
END DESCRIPTION:
XS GIS Cut Line= 4
        1081310.       818529.55      1081265.75       818381.47
      1081166.32       818269.86      1081016.77       818272.88
#Sta/Elev= 30
    4754 2643.16    4758 2642.64  4770.3 2639.64  4800.3 2634.63  4807.3 2631.62
  4814.5 2629.57  4827.6 2628.15  4863.1 2621.93  4902.8 2618.15  4963.3 2615.94
  4968.6 2615.43  4981.3 2612.92  4987.5 2612.75    4995 2609.75    5005 2609.75
  5012.5 2612.75  5019.6 2614.31    5032 2623.25  5057.5 2624.62  5077.7 2624.54
  5091.6 2624.25  5110.4 2627.99  5125.8 2634.46  5140.8 2637.14    5158 2641.96
  5186.4 2646.17  5199.7 2648.95  5203.1 2648.92  5206.8 2649.66  5207.6 2649.66
#Mann= 6 ,-1 , 0
    4754     .09       0  4987.5     .05       0  5012.5     .09       0
  5057.5     .03       0  5077.7     .09       0  5206.8     .05       0
#XS Ineff= 2 , 0
       0    4965    2624    5035       0    2624
Permanent Ineff=
       F       F
Bank Sta=4987.5,5012.5
Exp/Cntr=0.5,0.3

Type RM Length L Ch R = 1 ,14493   ,103,103,103
BEGIN DESCRIPTION:
bear_crk_xs_17, ineffective flow due to upstream expansion and down stream contraction
END DESCRIPTION:
XS GIS Cut Line= 2
       1081573.4       818208.07      1080974.48       818265.33
#Sta/Elev= 30
  4682.1 2666.63  4694.2 2662.59    4722 2657.19  4791.2 2630.62  4808.2 2624.78
  4826.2  2620.3  4858.9 2616.61  4894.5 2615.54    4911 2614.23  4947.3  2613.5
  4955.8 2614.15 4988.93 2609.95  4991.7 2608.94  5008.3 2608.94  5009.2 2610.16
  5024.6 2611.38  5062.8 2622.87  5089.4 2624.33  5109.7 2624.21  5131.2 2624.18
  5158.7 2628.55  5167.4 2628.57  5191.6 2635.67  5210.3 2640.09  5227.9 2642.45
  5239.7 2645.46  5245.3 2647.33  5268.9  2649.6    5277 2652.84  5283.7    2657
#Mann= 6 ,-1 , 0
  4682.1     .09       0 4988.93     .05       0  5009.2     .09       0
  5089.4     .03       0  5109.7     .09       0  5239.7     .05       0
#XS Ineff= 2 , 0
       0    4930    2620               0
Permanent Ineff=
       F       F
Bank Sta=4988.93,5009.2
Exp/Cntr=0.5,0.3

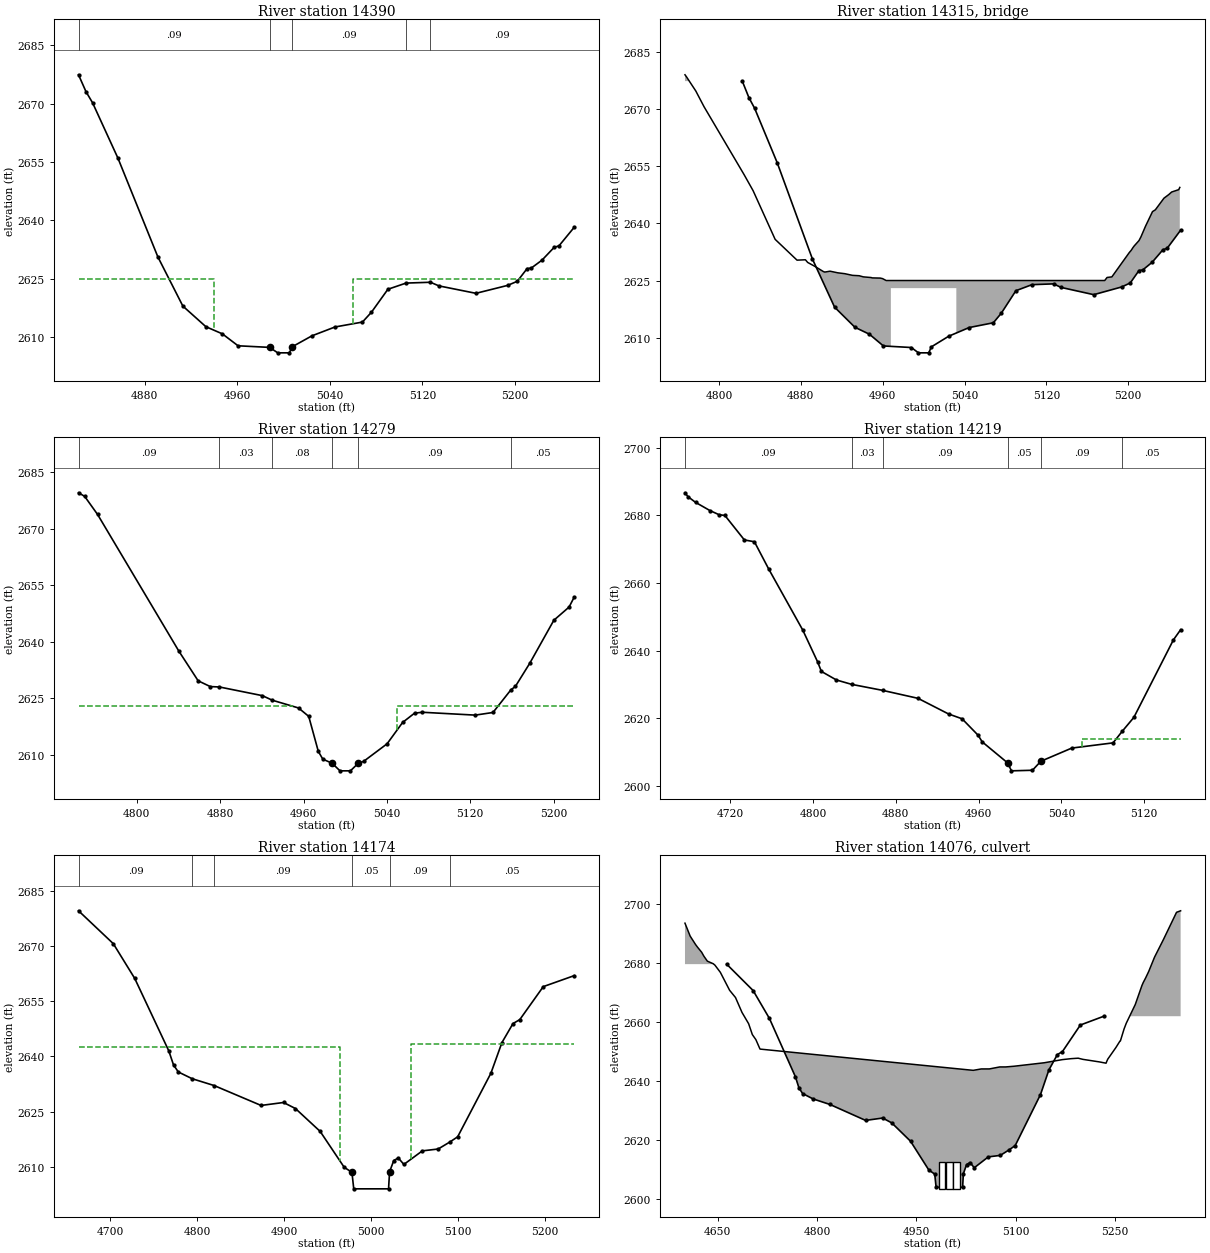
Type RM Length L Ch R = 1 ,14390   ,111,111,111
BEGIN DESCRIPTION:
bear_crk_xs_20
END DESCRIPTION:
XS GIS Cut Line= 3
       1081313.5       817981.29      1081216.07       818194.72
      1081030.37       818250.22
#Sta/Elev= 30
  4822.8 2677.39  4829.3 2673.03  4834.9 2670.23  4856.9 2655.97  4891.4 2630.62
    4913    2618  4932.9 2612.71  4947.1 2610.88  4960.7 2607.81 4987.99  2607.4
    4995    2606    5005    2606 5007.65 2607.58 5024.57 2610.37  5044.5 2612.64
  5068.2  2613.9    5076 2616.43  5090.2 2622.32  5105.9 2623.91    5127 2624.12
  5134.3 2623.19  5166.3 2621.28  5193.6 2623.31    5202 2624.36  5210.5 2627.62
  5214.2 2627.78  5223.4  2629.8  5233.8 2633.05  5238.1 2633.48  5251.2 2638.22
#Mann= 5 ,-1 , 0
  4822.8     .09       0 4987.99     .05       0 5007.65     .09       0
  5105.9     .03       0    5127     .09       0
#XS Ineff= 2 , 0
       0    4940    2625    5060       0    2625
Permanent Ineff=
       F       F
Bank Sta=4987.99,5007.65
Exp/Cntr=0.5,0.3

Type RM Length L Ch R = 3 ,14315   ,,,
BEGIN DESCRIPTION:
bear_crk_xs_22
Structure ID: State_BR_3_SR1197
Approximate Survey Structure
END DESCRIPTION:
Bridge Culvert--1,0,-1,-1, 0
Deck Dist Width WeirC Skew NumUp NumDn MinLoCord MaxHiCord MaxSubmerge Is_Ogee
40,20,3,0, 45, 45, , , , 0, 1,1,,
  4766.8  4768.1  4777.4  4785.4  4824.5  4833.4  4854.9  4876.3  4884.5  4886.7
  4893.8    4902  4903.4  4908.6  4916.2  4922.9  4930.5    4937  4941.1  4948.8
  4949.7  4957.6  4959.9  4963.4    4968    4968    5032    5032    5177  5179.3
    5184  5201.1  5202.8  5204.7  5205.9  5210.5  5212.4  5216.9  5223.7  5226.5
  5234.9  5239.6  5242.4  5249.3  5250.4
 2679.05 2678.58 2674.78 2670.67 2652.85 2648.59 2635.82 2630.35 2630.45 2629.75
 2628.71 2627.36 2627.22 2627.45 2627.02  2626.8 2626.36 2626.26 2625.96 2625.78
 2625.69 2625.64  2625.5    2625    2625    2625    2625    2625    2625  2625.8
 2625.96 2632.38  2632.9 2633.68 2634.11 2635.49 2636.47 2639.28  2643.1 2643.58
 2646.63 2647.58 2648.25 2648.87 2649.46
    2586    2586    2586    2586    2586    2586    2586    2586    2586    2586
    2586    2586    2586    2586    2586    2586    2586    2586    2586    2586
    2586    2586    2586    2586    2586    2623    2623    2586    2586    2586
    2586    2586    2586    2586    2586    2586    2586    2586    2586    2586
    2586    2586    2586    2586    2586
  4766.8  4768.1  4777.4  4785.4  4824.5  4833.4  4854.9  4876.3  4884.5  4886.7
  4893.8    4902  4903.4  4908.6  4916.2  4922.9  4930.5    4937  4941.1  4948.8
  4949.7  4957.6  4959.9  4963.4    4968    4968    5032    5032    5177  5179.3
    5184  5201.1  5202.8  5204.7  5205.9  5210.5  5212.4  5216.9  5223.7  5226.5
  5234.9  5239.6  5242.4  5249.3  5250.4
 2679.05 2678.58 2674.78 2670.67 2652.85 2648.59 2635.82 2630.35 2630.45 2629.75
 2628.71 2627.36 2627.22 2627.45 2627.02  2626.8 2626.36 2626.26 2625.96 2625.78
 2625.69 2625.64  2625.5    2625    2625    2625    2625    2625    2625  2625.8
 2625.96 2632.38  2632.9 2633.68 2634.11 2635.49 2636.47 2639.28  2643.1 2643.58
 2646.63 2647.58 2648.25 2648.87 2649.46
    2586    2586    2586    2586    2586    2586    2586    2586    2586    2586
    2586    2586    2586    2586    2586    2586    2586    2586    2586    2586
    2586    2586    2586    2586    2586    2623    2623    2586    2586    2586
    2586    2586    2586    2586    2586    2586    2586    2586    2586    2586
    2586    2586    2586    2586    2586
Abutment Skew #Up #Dn= , 2 , 2
    4968    4985
    2623 2607.56
    4968    4985
    2623 2608.06
Abutment Skew #Up #Dn= , 2 , 2
    5015    5032
 2609.11    2623
    5015    5032
    2608    2623
BR Coef= 0 , 1 , 0 ,1.25, 0 ,,,0.8,0,2,6,
WSPro=,,,, 1 ,,,, 0 ,,,, 0 ,,,,-1 ,-1 ,-1 , 0 , 0 , 0 , 0 , 0
BC Design=,, 0 ,, 0 ,,,,,,
BC HTab HWMax=2677.39

Type RM Length L Ch R = 1 ,14279   ,60,60,60
BEGIN DESCRIPTION:
bear_crk_xs_21
END DESCRIPTION:
XS GIS Cut Line= 4
      1081287.98       817948.81      1081146.47       818069.44
      1081118.63        818192.4      1080963.19       818243.44
#Sta/Elev= 30
  4744.1 2679.56    4750 2678.61  4762.4  2673.8  4840.4 2637.52  4858.9 2629.65
  4870.5 2628.12  4879.3 2628.01  4920.5 2625.71    4930  2624.5  4955.2 2622.44
    4965 2620.21  4974.2 2610.91  4978.5 2608.86  4987.5 2607.75    4995 2605.75
    5005 2605.75  5012.5 2607.75  5017.6 2608.25  5040.2 2612.93  5055.1  2618.6
  5066.5 2621.05  5073.8  2621.3  5124.8 2620.54  5141.8 2621.24    5159 2627.25
  5163.3 2628.16    5177 2634.26  5200.2 2645.72  5214.8 2649.22  5219.7 2651.84
#Mann= 6 ,-1 , 0
  4744.1     .09       0  4879.3     .03       0    4930     .08       0
  4987.5     .05       0  5012.5     .09       0    5159     .05       0
#XS Ineff= 2 , 0
       0    4950    2623    5050       0    2623
Permanent Ineff=
       F       F
Bank Sta=4987.5,5012.5
Exp/Cntr=0.5,0.3

Type RM Length L Ch R = 1 ,14219   ,45,45,45
BEGIN DESCRIPTION:
bear_crk_xs_23, ROB ineff due to upstream restriction
END DESCRIPTION:
XS GIS Cut Line= 2
      1081293.46       817875.21       1080971.3        818229.6
#Sta/Elev= 30
  4676.2 2686.69  4679.1 2685.54  4686.4 2683.86  4700.2 2681.45  4709.1 2680.21
  4714.8 2679.98  4733.6 2672.74  4743.3 2672.21    4757 2664.21  4790.1 2646.05
  4804.5 2636.61    4808 2633.87  4822.6 2631.33  4837.3 2630.04  4867.1 2628.27
  4901.4 2625.91  4930.9 2621.29    4944 2619.86  4959.5 2614.99  4963.4 2613.05
    4988 2606.82  4991.7 2604.47    5012 2604.64  5020.1  2607.3    5050  2611.2
  5089.9 2612.74  5098.8 2616.18    5110 2620.27  5148.2 2643.19  5155.2  2646.2
#Mann= 6 ,-1 , 0
  4676.2     .09       0  4837.3     .03       0  4867.1     .09       0
    4988     .05       0  5020.1     .09       0  5098.8     .05       0
#XS Ineff= 2 , 0
       0                    5060       0    2614
Permanent Ineff=
       F       F
Bank Sta=4988,5020.1
Exp/Cntr=0.5,0.3

Type RM Length L Ch R = 1 ,14174   ,255,255,255
BEGIN DESCRIPTION:
bear_crk_xs_24
END DESCRIPTION:
XS GIS Cut Line= 2
      1081254.46       817819.26      1080900.08       818265.21
#Sta/Elev= 30
  4663.7 2679.52  4703.7 2670.58  4728.3 2661.15  4767.5 2641.44  4772.9 2637.64
  4778.4 2635.74  4794.4  2633.9  4819.6 2632.05  4873.5 2626.65  4899.3 2627.45
    4913 2625.81  4941.4  2619.6    4969 2609.86 4977.91 2608.48    4980    2604
    5020    2604 5021.16 2608.63    5026 2611.69  5031.2 2612.39  5037.6 2610.63
  5058.8 2614.31    5077 2614.82  5090.3  2616.7  5099.4 2618.13  5137.6 2635.39
  5150.3 2643.73    5163 2648.89  5170.8 2649.96  5197.8 2658.92  5233.3  2661.9
#Mann= 6 ,-1 , 0
  4663.7     .09       0  4794.4     .03       0  4819.6     .09       0
 4977.91     .05       0 5021.16     .09       0  5090.3     .05       0
#XS Ineff= 2 , 0
       0    4964 2642.55    5046       0 2643.43
Permanent Ineff=
       F       F
Bank Sta=4977.91,5021.16
Exp/Cntr=0.5,0.3

Type RM Length L Ch R = 2 ,14076   ,,,
BEGIN DESCRIPTION:
bear_crk_xs_19
Structure ID: State_Culvert_1_NC226
Approximate Survey Structure
END DESCRIPTION:
Bridge Culvert--1,0,-1,-1, 0
Deck Dist Width WeirC Skew NumUp NumDn MinLoCord MaxHiCord MaxSubmerge Is_Ogee
90,80,3,0, 46, 46, , , , 0, 1,1,,
  4600.8  4608.6  4616.7  4619.8    4626  4629.4  4634.6  4643.4    4646  4654.2
  4668.2  4677.1  4686.9  4696.9  4702.5  4707.8  4714.1    5036  5048.1  5060.4
  5076.1  5084.9  5097.3  5143.1  5170.8  5183.8  5194.5  5201.5  5226.6  5236.6
  5237.9  5239.2  5251.5  5257.5  5258.2  5263.8  5267.1  5280.7  5290.7  5292.6
  5296.4    5301  5309.8    5323    5343  5349.2
 2693.38 2689.01 2686.18 2685.24 2683.54 2682.19 2680.53 2679.66 2679.18 2676.75
 2670.67 2668.22 2663.18 2659.37 2655.69 2653.99 2650.78 2643.59 2644.06 2644.07
 2644.74 2644.74 2644.97 2646.15 2647.22 2647.54  2647.7 2647.31 2646.44 2646.01
 2646.75 2647.38 2651.32 2653.46  2653.5 2657.59 2659.52 2665.86 2672.25 2673.24
 2674.88 2677.05 2681.89 2687.74 2697.05 2697.57
    2580    2580    2580    2580    2580    2580    2580    2580    2580    2580
    2580    2580    2580    2580    2580    2580    2580    2580    2580    2580
    2580    2580    2580    2580    2580    2580    2580    2580    2580    2580
    2580    2580    2580    2580    2580    2580    2580    2580    2580    2580
    2580    2580    2580    2580    2580    2580
  4600.8  4608.6  4616.7  4619.8    4626  4629.4  4634.6  4643.4    4646  4654.2
  4668.2  4677.1  4686.9  4696.9  4702.5  4707.8  4714.1    5036  5048.1  5060.4
  5076.1  5084.9  5097.3  5143.1  5170.8  5183.8  5194.5  5201.5  5226.6  5236.6
  5237.9  5239.2  5251.5  5257.5  5258.2  5263.8  5267.1  5280.7  5290.7  5292.6
  5296.4    5301  5309.8    5323    5343  5349.2
 2693.38 2689.01 2686.18 2685.24 2683.54 2682.19 2680.53 2679.66 2679.18 2676.75
 2670.67 2668.22 2663.18 2659.37 2655.69 2653.99 2650.78 2643.59 2644.06 2644.07
 2644.74 2644.74 2644.97 2646.15 2647.22 2647.54  2647.7 2647.31 2646.44 2646.01
 2646.75 2647.38 2651.32 2653.46  2653.5 2657.59 2659.52 2665.86 2672.25 2673.24
 2674.88 2677.05 2681.89 2687.74 2697.05 2697.57
    2580    2580    2580    2580    2580    2580    2580    2580    2580    2580
    2580    2580    2580    2580    2580    2580    2580    2580    2580    2580
    2580    2580    2580    2580    2580    2580    2580    2580    2580    2580
    2580    2580    2580    2580    2580    2580    2580    2580    2580    2580
    2580    2580    2580    2580    2580    2580
BR Coef= 0 , 1 , 0 ,, 0 ,,,0.8,0,,6,
WSPro=,,,, 1 ,,,, 0 ,,,, 0 ,,,,-1 ,-1 ,-1 , 0 , 0 , 0 , 0 , 0
Multiple Barrel Culv=2,9,10,192,0.015,0.4,1,8,1,2603.5,2599.5, 3,Culvert #1  , 0 ,30
    4989    4989    5000    5000    5011    5011
Culvert Bottom n=0.015
BC Design=,, 0 ,, 0 ,,,,,,
BC HTab HWMax=2679.52