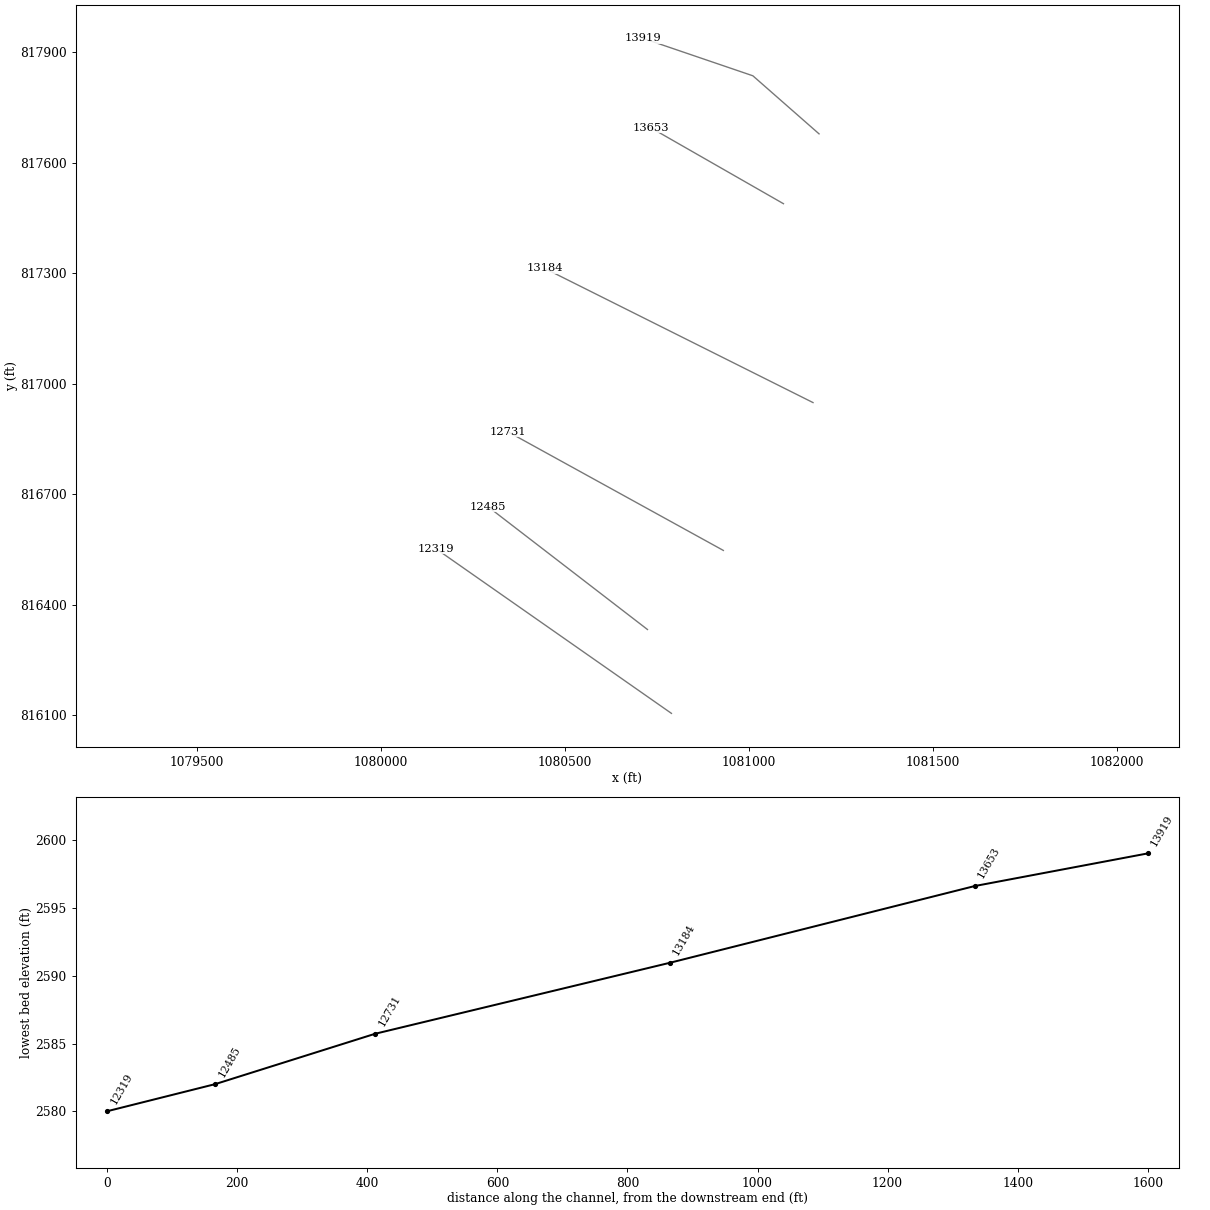
HEC-RAS study lds_bear_crk.prj: Bear Creek Limited Detail Study

--- lds_bear_crk.g01 (geometry) --- (continued)

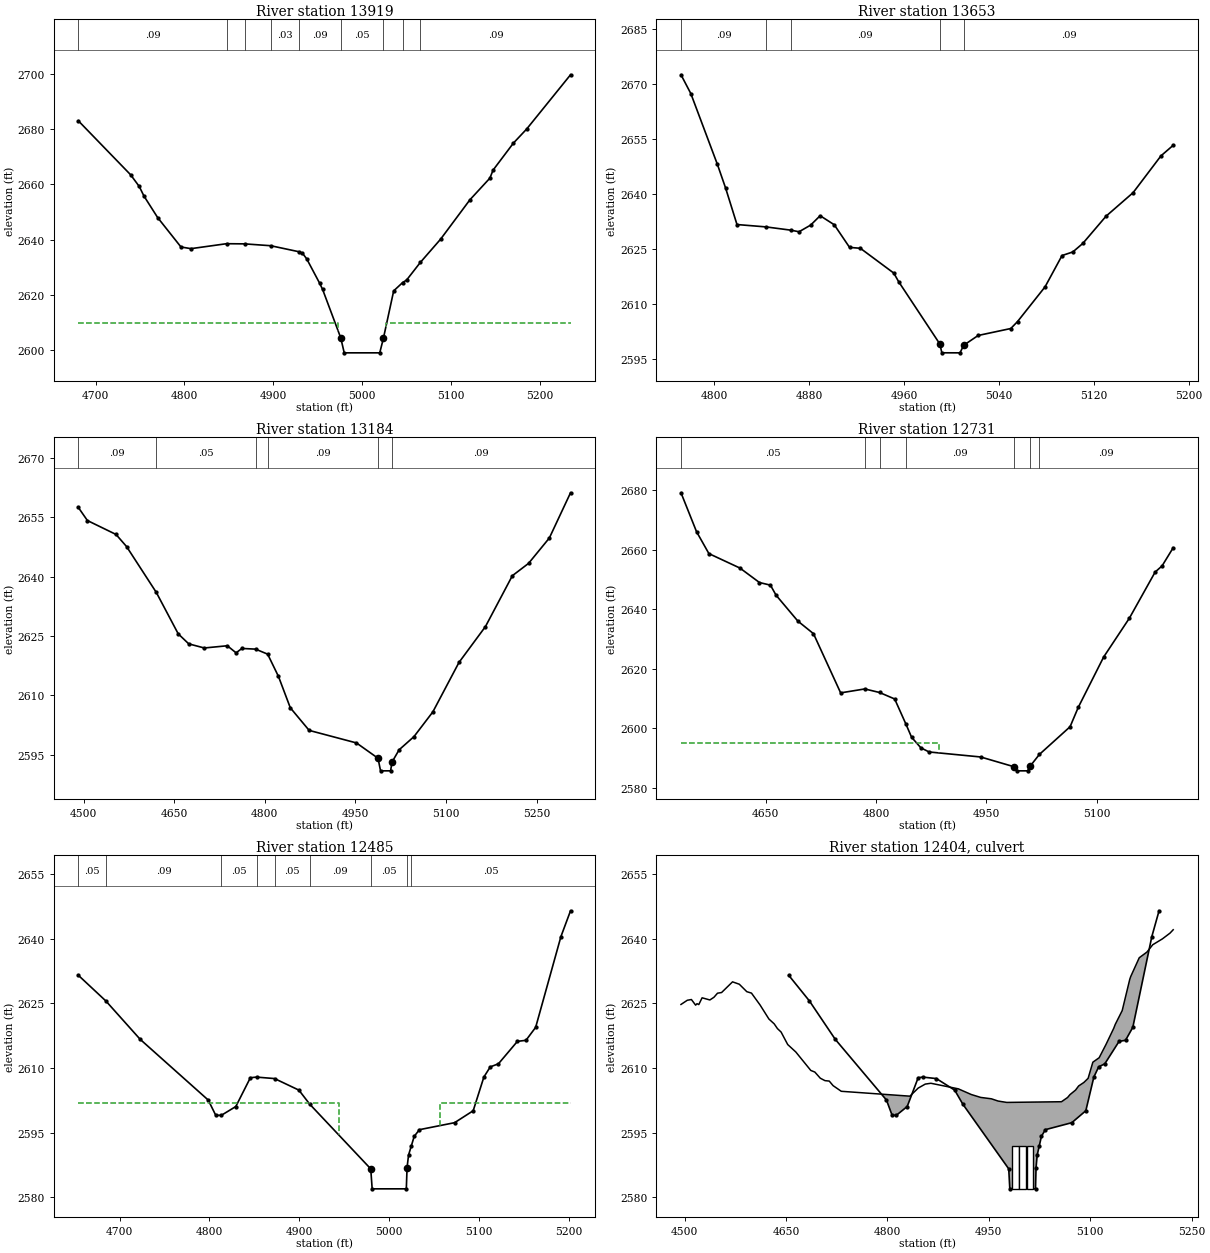
Type RM Length L Ch R = 1 ,13919   ,266,266,266
BEGIN DESCRIPTION:
bear_crk_xs_18
END DESCRIPTION:
XS GIS Cut Line= 3
      1081190.03       817678.52      1081010.29       817836.22
      1080711.86       817937.95
#Sta/Elev= 30
  4680.5 2682.98  4739.4 2663.45  4749.1 2659.23  4754.4 2655.77  4769.8 2647.99
  4796.1 2637.33  4807.4 2636.73  4847.4 2638.52  4867.8 2638.46  4897.2 2637.79
  4928.9 2635.62  4932.8 2635.14  4937.7 2633.06  4952.2 2624.28  4955.6 2622.01
 4976.04 2604.48    4980 2599.04    5020 2599.04 5024.18 2604.38  5035.7 2621.46
  5045.7 2624.44  5050.3 2625.39  5065.7 2631.74  5088.6 2640.18  5121.6 2654.42
  5144.1 2662.25  5147.6 2665.12  5170.6 2674.93  5185.5 2680.01  5234.9 2699.63
#Mann= 9 ,-1 , 0
  4680.5     .09       0  4847.4     .03       0  4867.8     .09       0
  4897.2     .03       0  4928.9     .09       0 4976.04     .05       0
 5024.18     .09       0  5045.7     .03       0  5065.7     .09       0
#XS Ineff= 2 , 0
       0    4973    2610    5027       0    2610
Permanent Ineff=
       F       F
Bank Sta=4976.04,5024.18
Exp/Cntr=0.5,0.3

Type RM Length L Ch R = 1 ,13653   ,469,469,469
BEGIN DESCRIPTION:
bear_crk_xs_25
END DESCRIPTION:
XS GIS Cut Line= 2
      1081093.38       817488.83      1080733.28       817694.91
#Sta/Elev= 30
  4771.8 2672.53  4780.1 2667.39  4802.5 2648.06  4809.4 2641.61    4819 2631.65
  4843.3 2631.01  4864.3 2630.12  4871.3 2629.68  4881.1  2631.5  4889.1 2634.06
    4901 2631.59  4913.9 2625.41    4923 2625.17  4951.2 2618.39  4955.2 2616.09
 4989.96 2599.06  4991.7 2596.64    5007 2596.63  5010.1  2598.7  5022.3 2601.37
  5049.8 2603.27  5055.5 2605.17  5078.7 2614.65    5093 2623.19  5102.1 2624.17
  5110.5 2626.49  5130.1 2633.93  5152.9 2640.35  5176.4  2650.4  5186.7 2653.28
#Mann= 5 ,-1 , 0
  4771.8     .09       0  4843.3     .03       0  4864.3     .09       0
 4989.96     .05       0  5010.1     .09       0
Bank Sta=4989.96,5010.1
Exp/Cntr=0.3,0.1

Type RM Length L Ch R = 1 ,13184   ,453,453,453
BEGIN DESCRIPTION:
bear_crk_xs_26
END DESCRIPTION:
XS GIS Cut Line= 2
      1081173.64       816948.69      1080444.78       817313.12
#Sta/Elev= 30
  4491.4  2657.5  4506.4  2654.2  4553.8 2650.68  4571.2 2647.63  4620.5 2636.03
  4656.8 2625.56  4674.2 2623.04  4699.9    2622    4738 2622.56  4752.6 2620.77
  4762.1 2621.88  4784.8 2621.71  4804.8 2620.44  4822.7 2614.81  4842.3 2606.89
  4873.5 2601.18  4951.8 2598.01  4987.5 2594.14  4991.7 2590.96  5008.3 2590.96
  5010.7 2593.18  5022.4 2596.27    5047  2599.6  5078.3 2605.86  5121.5 2618.34
  5165.4 2627.42  5209.9 2640.26  5236.7 2643.37  5271.1 2649.78  5306.2 2661.21
#Mann= 6 ,-1 , 0
  4491.4     .09       0  4620.5     .05       0  4784.8     .03       0
  4804.8     .09       0  4987.5     .05       0  5010.7     .09       0
Bank Sta=4987.5,5010.7
Exp/Cntr=0.3,0.1

Type RM Length L Ch R = 1 ,12731   ,246,246,246
BEGIN DESCRIPTION:
bear_crk_xs_27, IEF due to downstream restrictioin
END DESCRIPTION:
XS GIS Cut Line= 2
      1080930.14       816547.11      1080344.45       816869.78
#Sta/Elev= 30
  4535.1 2679.16  4556.2 2666.09    4573 2658.72  4615.2 2653.86  4641.7    2649
  4656.6 2648.12  4664.3 2644.73  4693.8 2636.06  4715.1 2631.81    4752 2611.92
  4784.8 2613.24  4804.8 2612.05  4825.4 2609.87  4840.5 2601.53  4848.4    2597
    4861 2593.45  4872.2 2592.06  4942.2 2590.38 4987.52  2587.1  4991.7 2585.72
 5006.02 2585.72 5009.19 2587.21    5022 2591.23  5063.7 2600.54  5074.8 2607.04
  5109.3 2623.96  5144.3 2637.03  5179.3 2652.53  5188.7 2654.59  5203.8 2660.69
#Mann= 7 ,-1 , 0
  4535.1     .05       0  4784.8     .03       0  4804.8     .05       0
  4840.5     .09       0 4987.52     .05       0 5009.19     .06       0
    5022     .09       0
#XS Ineff= 2 , 0
       0    4885    2595               0
Permanent Ineff=
       F       F
Bank Sta=4987.52,5009.19
Exp/Cntr=0.5,0.3

Type RM Length L Ch R = 1 ,12485   ,166,166,166
BEGIN DESCRIPTION:
bear_crk_xs_29
END DESCRIPTION:
XS GIS Cut Line= 2
      1080724.06       816332.35      1080290.22       816666.42
#Sta/Elev= 30
  4654.1 2631.52  4684.7 2625.57  4722.9 2616.67  4798.6 2602.59    4807 2599.05
  4813.2 2599.05  4829.3 2601.09  4845.5 2607.77  4852.4 2607.91  4872.4 2607.57
  4899.5 2604.89  4911.5 2601.64 4979.42 2586.63    4981    2582    5019    2582
 5019.83 2586.94  5021.5 2589.84  5024.4 2591.84  5027.8 2594.18  5033.6 2595.72
  5072.7 2597.34  5093.4 2600.11  5105.3 2607.93  5112.4 2610.28  5121.5    2611
  5142.6  2616.2  5152.1 2616.44  5162.9 2619.45    5191 2640.49  5201.7 2646.48
#Mann= 9 ,-1 , 0
  4654.1     .05       0  4684.7     .09       0  4813.2     .05       0
  4852.4     .03       0  4872.4     .05       0  4911.5     .09       0
 4979.42     .05       0 5019.83     .09       0  5024.4     .05       0
#XS Ineff= 2 , 0
       0    4944    2602    5056       0    2602
Permanent Ineff=
       F       F
Bank Sta=4979.42,5019.83
Exp/Cntr=0.5,0.3

Type RM Length L Ch R = 2 ,12404   ,,,
BEGIN DESCRIPTION:
bear_crk_xs_30
Structure ID: State_Culvert_2_SR1162
Approximate Survey Structure
END DESCRIPTION:
Bridge Culvert--1,0,-1,-1, 0
Deck Dist Width WeirC Skew NumUp NumDn MinLoCord MaxHiCord MaxSubmerge Is_Ogee
56,50,3,0, 60, 60, , , , 0, 1,1,,
  4494.8  4504.1  4510.2  4516.4  4518.5  4521.1    4526  4537.5  4543.5  4548.8
  4554.8    4571    4581  4592.1    4599  4611.7  4624.8  4632.6  4637.4  4642.8
  4652.6  4664.6  4686.7  4692.7  4700.8  4707.7    4714  4719.7  4731.8  4833.3
  4845.5    4856  4864.3  4904.9  4924.1    4938  4953.8  4963.7  4976.5  5057.4
  5066.4    5070  5078.2  5082.8  5090.5  5096.8  5103.8  5113.1  5123.2  5134.7
  5136.9  5147.2  5158.4  5159.8  5172.4  5183.8  5192.4  5206.6  5217.9  5222.6
 2624.76 2625.73  2625.9  2624.6 2624.93 2624.73  2626.3  2625.8 2626.42 2627.37
 2627.52    2630 2629.45 2627.72 2627.39 2624.64 2621.38 2620.26 2619.16 2618.36
 2615.46 2613.73 2609.46 2609.08 2607.65 2607.09 2606.99 2605.93 2604.62 2603.49
 2605.36 2606.29 2606.48 2605.19 2603.87  2603.2 2602.88 2602.36 2602.04  2602.2
 2603.18 2603.85  2604.9 2605.86 2606.67 2607.63 2611.37  2612.4 2615.47 2619.24
 2620.13 2623.34  2630.6 2631.24 2635.59 2636.91 2638.61 2639.96  2641.3 2642.08
    2560    2560    2560    2560    2560    2560    2560    2560    2560    2560
    2560    2560    2560    2560    2560    2560    2560    2560    2560    2560
    2560    2560    2560    2560    2560    2560    2560    2560    2560    2560
    2560    2560    2560    2560    2560    2560    2560    2560    2560    2560
    2560    2560    2560    2560    2560    2560    2560    2560    2560    2560
    2560    2560    2560    2560    2560    2560    2560    2560    2560    2560
  4494.8  4504.1  4510.2  4516.4  4518.5  4521.1    4526  4537.5  4543.5  4548.8
  4554.8    4571    4581  4592.1    4599  4611.7  4624.8  4632.6  4637.4  4642.8
  4652.6  4664.6  4686.7  4692.7  4700.8  4707.7    4714  4719.7  4731.8  4833.3
  4845.5    4856  4864.3  4904.9  4924.1    4938  4953.8  4963.7  4976.5  5057.4
  5066.4    5070  5078.2  5082.8  5090.5  5096.8  5103.8  5113.1  5123.2  5134.7
  5136.9  5147.2  5158.4  5159.8  5172.4  5183.8  5192.4  5206.6  5217.9  5222.6
 2624.76 2625.73  2625.9  2624.6 2624.93 2624.73  2626.3  2625.8 2626.42 2627.37
 2627.52    2630 2629.45 2627.72 2627.39 2624.64 2621.38 2620.26 2619.16 2618.36
 2615.46 2613.73 2609.46 2609.08 2607.65 2607.09 2606.99 2605.93 2604.62 2603.49
 2605.36 2606.29 2606.48 2605.19 2603.87  2603.2 2602.88 2602.36 2602.04  2602.2
 2603.18 2603.85  2604.9 2605.86 2606.67 2607.63 2611.37  2612.4 2615.47 2619.24
 2620.13 2623.34  2630.6 2631.24 2635.59 2636.91 2638.61 2639.96  2641.3 2642.08
    2560    2560    2560    2560    2560    2560    2560    2560    2560    2560
    2560    2560    2560    2560    2560    2560    2560    2560    2560    2560
    2560    2560    2560    2560    2560    2560    2560    2560    2560    2560
    2560    2560    2560    2560    2560    2560    2560    2560    2560    2560
    2560    2560    2560    2560    2560    2560    2560    2560    2560    2560
    2560    2560    2560    2560    2560    2560    2560    2560    2560    2560
BR Coef= 0 , 1 , 0 ,, 0 ,,,0.8,0,,6,
WSPro=,,,, 1 ,,,, 0 ,,,, 0 ,,,,-1 ,-1 ,-1 , 0 , 0 , 0 , 0 , 0
Multiple Barrel Culv=2,10,10,82,0.015,0.4,1,8,1,2582,2580, 3,Culvert #1  , 0 ,40
    4989    4989    5000    5000    5011    5011
Culvert Bottom n=0.015
BC Design=,, 0 ,, 0 ,,,,,,
BC HTab HWMax=2646.48

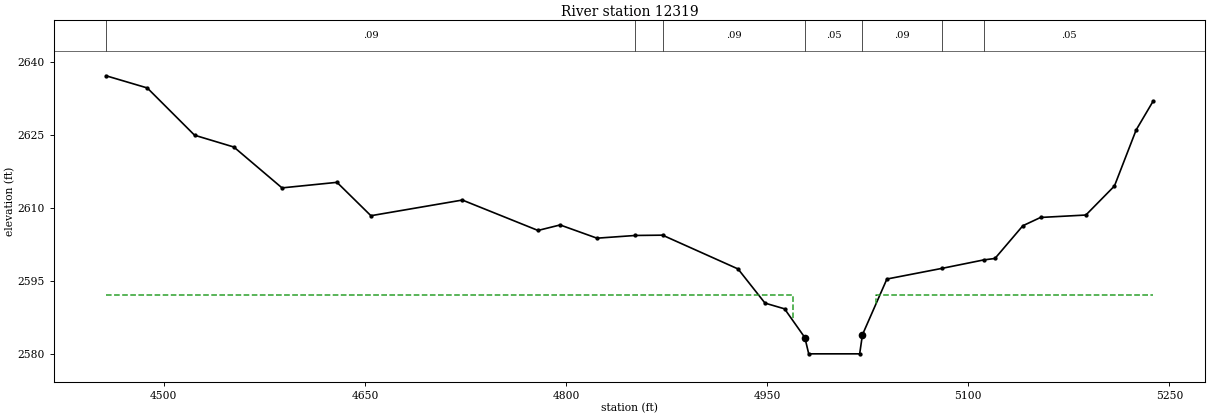
Type RM Length L Ch R = 1 ,12319   ,197,197,197
BEGIN DESCRIPTION:
bear_crk_xs_28
END DESCRIPTION:
XS GIS Cut Line= 2
      1080789.14       816104.58      1080149.22       816551.99
#Sta/Elev= 30
    4457 2637.17  4487.7 2634.67    4523 2624.95  4552.3 2622.52  4588.2 2614.12
  4629.2 2615.26  4654.5  2608.4  4722.7 2611.62  4779.1 2605.37  4795.6  2606.5
  4823.1 2603.78  4851.8 2604.34    4872  2604.4  4928.3 2597.45  4948.4 2590.43
    4963 2589.25 4978.12 2583.34    4981    2580    5019    2580 5021.07 2583.93
  5039.3 2595.38  5080.5 2597.58  5111.5 2599.31  5119.9 2599.61  5140.7 2606.34
  5153.9 2608.04  5187.7 2608.54    5209 2614.51  5225.2 2626.04  5237.8 2631.93
#Mann= 7 ,-1 , 0
    4457     .09       0  4851.8     .03       0    4872     .09       0
 4978.12     .05       0 5021.07     .09       0  5080.5     .03       0
  5111.5     .05       0
#XS Ineff= 2 , 0
       0    4969    2592    5031       0    2592
Permanent Ineff=
       F       F
Bank Sta=4978.12,5021.07
Exp/Cntr=0.5,0.3