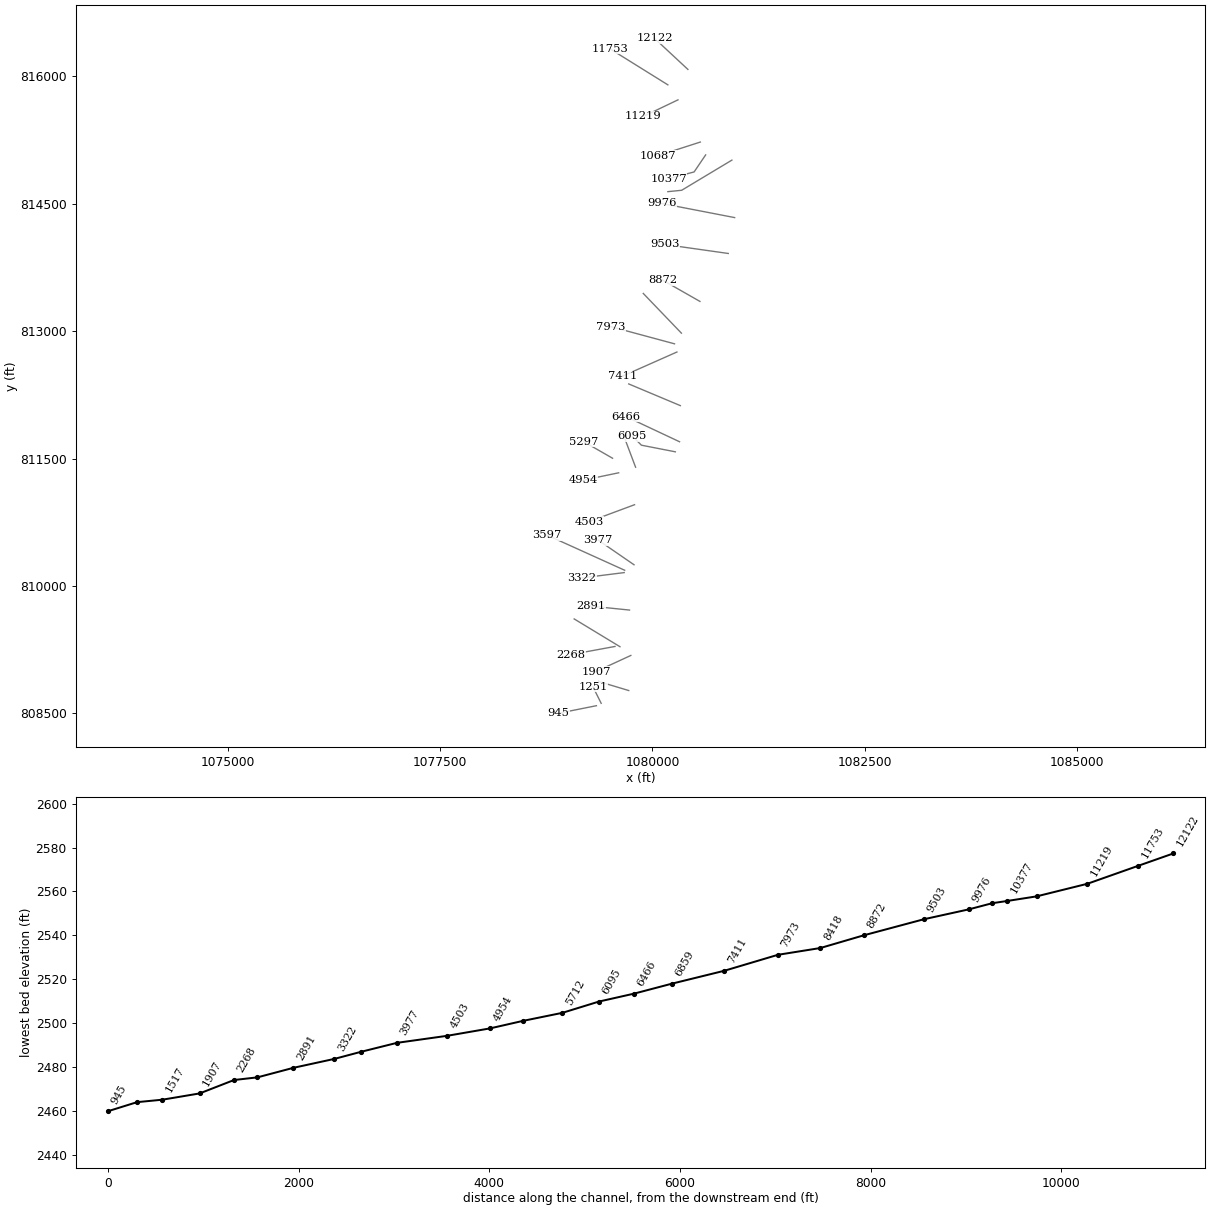
HEC-RAS study lds_bear_crk.prj: Bear Creek Limited Detail Study

--- lds_bear_crk.g01 (geometry) --- (continued)

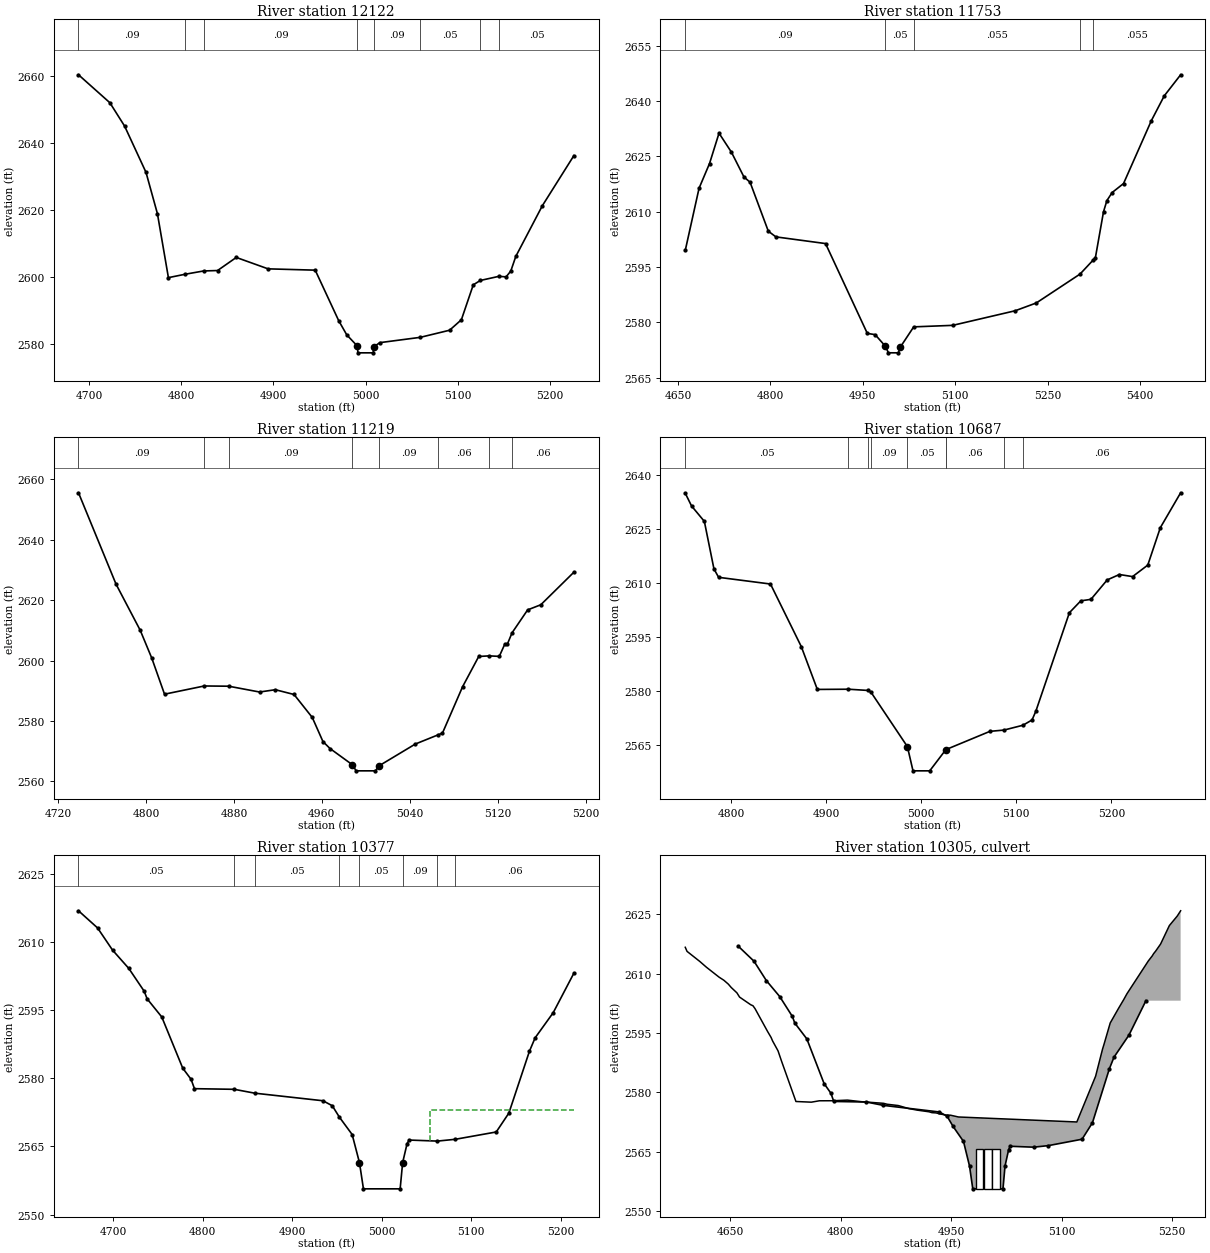
Type RM Length L Ch R = 1 ,12122   ,369,369,369
BEGIN DESCRIPTION:
bear_crk_xs_31
END DESCRIPTION:
XS GIS Cut Line= 2
      1080417.66       816082.89      1080024.48       816448.95
#Sta/Elev= 30
  4688.7 2660.24  4722.7 2651.91  4738.7 2644.94  4761.9 2631.15  4774.3 2618.81
  4786.2 2599.76  4804.3 2600.77  4824.4 2601.75  4839.5 2601.88  4859.8 2605.78
  4894.3 2602.38  4945.4 2601.99  4970.9 2586.91  4979.6  2582.7  4991.1 2579.36
  4991.7 2577.34  5008.3 2577.34    5009 2579.17  5015.5 2580.38  5059.3 2581.96
  5091.1 2584.08  5103.9  2587.2  5116.8 2597.62  5124.5 2598.92  5144.6 2600.15
  5152.4 2599.99  5157.5 2601.73  5162.9 2606.08  5191.7  2621.2  5225.9 2636.14
#Mann= 8 ,-1 , 0
  4688.7     .09       0  4804.3     .03       0  4824.4     .09       0
  4991.1     .05       0    5009     .09       0  5059.3     .05       0
  5124.5     .03       0  5144.6     .05       0
Bank Sta=4991.1,5009
Exp/Cntr=0.3,0.1

Type RM Length L Ch R = 1 ,11753   ,534,534,534
BEGIN DESCRIPTION:
bear_crk_xs_32
END DESCRIPTION:
XS GIS Cut Line= 2
      1080181.75       815901.22      1079498.44       816326.93
#Sta/Elev= 30
  4661.9 2599.46  4684.3 2616.32  4701.3 2623.02  4716.7 2631.24  4736.8  2626.1
  4757.1 2619.39  4767.1 2617.94  4796.7 2604.68    4809 2603.13  4889.6 2601.32
  4957.4 2576.97 4970.15 2576.63 4986.57 2573.52  4991.7 2571.71 5007.95  2571.7
 5010.62 2573.16  5032.7 2578.74    5096 2579.15  5197.5 2583.11  5231.7 2585.22
  5302.7 2593.05  5324.1 2596.87  5327.6 2597.47  5340.8 2609.95  5346.3 2612.97
  5354.8 2615.15  5373.3 2617.59  5418.5 2634.65  5439.4 2641.36    5466 2647.07
#Mann= 5 ,-1 , 0
  4661.9     .09       0 4986.57     .05       0  5032.7    .055       0
  5302.7     .03       0  5324.1    .055       0
Bank Sta=4986.57,5010.62
Exp/Cntr=0.3,0.1

Type RM Length L Ch R = 1 ,11219   ,532,532,532
BEGIN DESCRIPTION:
bear_crk_xs_33
END DESCRIPTION:
XS GIS Cut Line= 2
      1080301.06       815724.42      1079894.33       815529.74
#Sta/Elev= 30
  4738.5  2655.5  4772.7 2625.24  4794.7 2609.99  4805.2 2600.79  4816.8 2588.86
    4853 2591.58  4875.2  2591.5  4903.3 2589.58  4917.7 2590.34  4934.7 2588.76
  4951.3 2581.15    4961 2573.19  4967.4 2570.89 4987.83  2565.5  4991.2  2563.5
  5008.8  2563.5 5011.93 2565.13  5045.1 2572.37  5065.9 2575.42  5069.8    2576
  5088.1 2591.33  5102.8 2601.34  5112.3 2601.54  5121.5 2601.37  5126.6 2605.49
  5128.8 2605.38  5133.1 2609.15  5147.3 2616.75  5159.3 2618.45  5189.4 2629.22
#Mann= 8 ,-1 , 0
  4738.5     .09       0    4853     .03       0  4875.2     .09       0
 4987.83     .05       0 5011.93     .09       0  5065.9     .06       0
  5112.3     .03       0  5133.1     .06       0
Bank Sta=4987.83,5011.93
Exp/Cntr=0.3,0.1

Type RM Length L Ch R = 1 ,10687   ,310,310,310
BEGIN DESCRIPTION:
bear_crk_xs_34
END DESCRIPTION:
XS GIS Cut Line= 2
      1080564.08        815227.4      1080067.87       815067.42
#Sta/Elev= 30
  4751.5  2634.8  4758.1 2631.28  4771.6 2626.99  4781.7  2613.8  4786.6 2611.47
  4841.2 2609.61  4873.6 2592.26  4890.5 2580.36  4923.3 2580.42  4943.8 2580.08
  4946.8 2579.66  4985.3 2564.49  4991.2 2557.77  5008.8 2557.77  5025.6 2563.59
    5026 2563.68  5072.2 2568.73  5086.9 2569.08  5106.9 2570.42  5116.5 2571.89
  5120.5 2574.32  5155.8 2601.65  5167.8 2604.94  5178.5 2605.36  5195.6 2610.75
  5208.4 2612.25  5222.3 2611.67  5238.3 2614.86  5251.5 2625.24  5272.9 2634.93
#Mann= 9 ,-1 , 0
  4751.5     .05       0  4923.3     .03       0  4943.8     .05       0
  4946.8     .09       0  4985.3     .05       0  5025.6     .09       0
    5026     .06       0  5086.9     .03       0  5106.9     .06       0
Bank Sta=4985.3,5025.6
Exp/Cntr=0.5,0.3

Type RM Length L Ch R = 1 ,10377   ,155,155,155
BEGIN DESCRIPTION:
bear_crk_xs_35
END DESCRIPTION:
XS GIS Cut Line= 3
      1080626.45       815075.82      1080490.87       814875.17
      1080189.89       814796.53
#Sta/Elev= 30
  4661.3 2616.93  4682.6 2613.15  4699.3 2608.27  4717.5 2604.22  4734.7 2599.19
  4737.9 2597.54  4754.3 2593.53  4777.7 2582.25    4787  2579.8  4790.8 2577.73
  4835.2 2577.59  4858.1 2576.74  4934.3 2575.07  4944.7 2573.97  4952.7 2571.44
  4966.9 2567.63 4975.07 2561.42  4979.5 2555.66  5020.5 2555.66 5023.25 2561.42
  5028.2 2565.59  5030.5 2566.41  5062.1 2566.18  5082.2 2566.58  5127.8 2568.19
  5141.9 2572.35  5164.9    2586  5171.2 2588.93  5191.4 2594.47  5214.5 2603.18
#Mann= 8 ,-1 , 0
  4661.3     .05       0  4835.2     .03       0  4858.1     .05       0
  4952.7     .09       0 4975.07     .05       0 5023.25     .09       0
  5062.1     .03       0  5082.2     .06       0
#XS Ineff= 2 , 0
       0    4946    2573    5054       0    2573
Permanent Ineff=
       F       F
Bank Sta=4975.07,5023.25
Exp/Cntr=0.5,0.3

Type RM Length L Ch R = 2 ,10305   ,,,
BEGIN DESCRIPTION:
bear_crk_xs_37
Structure ID: State_Culvert_3_SR1242
Approximate Survey Structure
END DESCRIPTION:
Bridge Culvert--1,0,-1,-1, 0
Deck Dist Width WeirC Skew NumUp NumDn MinLoCord MaxHiCord MaxSubmerge Is_Ogee
50,45,3,0, 52, 52, , , , 0, 1,1,,
  4589.3  4591.7  4609.1  4617.9  4635.3  4641.7  4647.7  4651.7  4659.4    4663
  4678.1  4681.2    4684    4701  4705.8  4707.8  4715.2    4720  4739.5  4760.4
  4771.3  4789.9  4809.3  4827.8  4858.5  4863.1  4878.3  4892.7  4904.4  4920.1
  4924.1  4929.6  4936.1  4943.9  4949.3  4960.1  5120.7  5146.2  5155.6  5157.6
    5166    5177  5184.4  5188.7  5217.7  5223.1  5224.9  5227.7  5234.4  5246.3
  5256.9  5261.6
 2616.67 2615.64 2613.08 2611.65 2609.11 2608.34 2607.37 2606.51 2605.16 2604.09
 2602.16  2601.9 2601.17 2595.41 2593.89 2593.02 2590.51 2587.89 2577.72 2577.55
  2577.9 2577.91 2578.07 2577.68 2577.26 2577.03  2576.7 2575.93 2575.53 2575.12
  2574.9 2574.84 2574.53 2574.28 2574.26 2573.81 2572.55 2584.11 2590.96 2592.17
 2597.55 2601.15 2603.48 2604.93 2613.21 2614.51 2615.06 2615.71  2617.5 2622.16
 2624.54 2625.89
    2535    2535    2535    2535    2535    2535    2535    2535    2535    2535
    2535    2535    2535    2535    2535    2535    2535    2535    2535    2535
    2535    2535    2535    2535    2535    2535    2535    2535    2535    2535
    2535    2535    2535    2535    2535    2535    2535    2535    2535    2535
    2535    2535    2535    2535    2535    2535    2535    2535    2535    2535
    2535    2535
  4589.3  4591.7  4609.1  4617.9  4635.3  4641.7  4647.7  4651.7  4659.4    4663
  4678.1  4681.2    4684    4701  4705.8  4707.8  4715.2    4720  4739.5  4760.4
  4771.3  4789.9  4809.3  4827.8  4858.5  4863.1  4878.3  4892.7  4904.4  4920.1
  4924.1  4929.6  4936.1  4943.9  4949.3  4960.1  5120.7  5146.2  5155.6  5157.6
    5166    5177  5184.4  5188.7  5217.7  5223.1  5224.9  5227.7  5234.4  5246.3
  5256.9  5261.6
 2616.67 2615.64 2613.08 2611.65 2609.11 2608.34 2607.37 2606.51 2605.16 2604.09
 2602.16  2601.9 2601.17 2595.41 2593.89 2593.02 2590.51 2587.89 2577.72 2577.55
  2577.9 2577.91 2578.07 2577.68 2577.26 2577.03  2576.7 2575.93 2575.53 2575.12
  2574.9 2574.84 2574.53 2574.28 2574.26 2573.81 2572.55 2584.11 2590.96 2592.17
 2597.55 2601.15 2603.48 2604.93 2613.21 2614.51 2615.06 2615.71  2617.5 2622.16
 2624.54 2625.89
    2535    2535    2535    2535    2535    2535    2535    2535    2535    2535
    2535    2535    2535    2535    2535    2535    2535    2535    2535    2535
    2535    2535    2535    2535    2535    2535    2535    2535    2535    2535
    2535    2535    2535    2535    2535    2535    2535    2535    2535    2535
    2535    2535    2535    2535    2535    2535    2535    2535    2535    2535
    2535    2535
BR Coef= 0 , 1 , 0 ,, 0 ,,,0.8,0,,6,
WSPro=,,,, 1 ,,,, 0 ,,,, 0 ,,,,-1 ,-1 ,-1 , 0 , 0 , 0 , 0 , 0
Multiple Barrel Culv=2,10,10,68,0.015,0.4,1,8,1,2555.66,2554.66, 3,Culvert #1  , 0 ,38
    4989    4989    5000    5000    5011    5011
Culvert Bottom n=0.015
BC Design=,, 0 ,, 0 ,,,,,,
BC HTab HWMax=2616.93

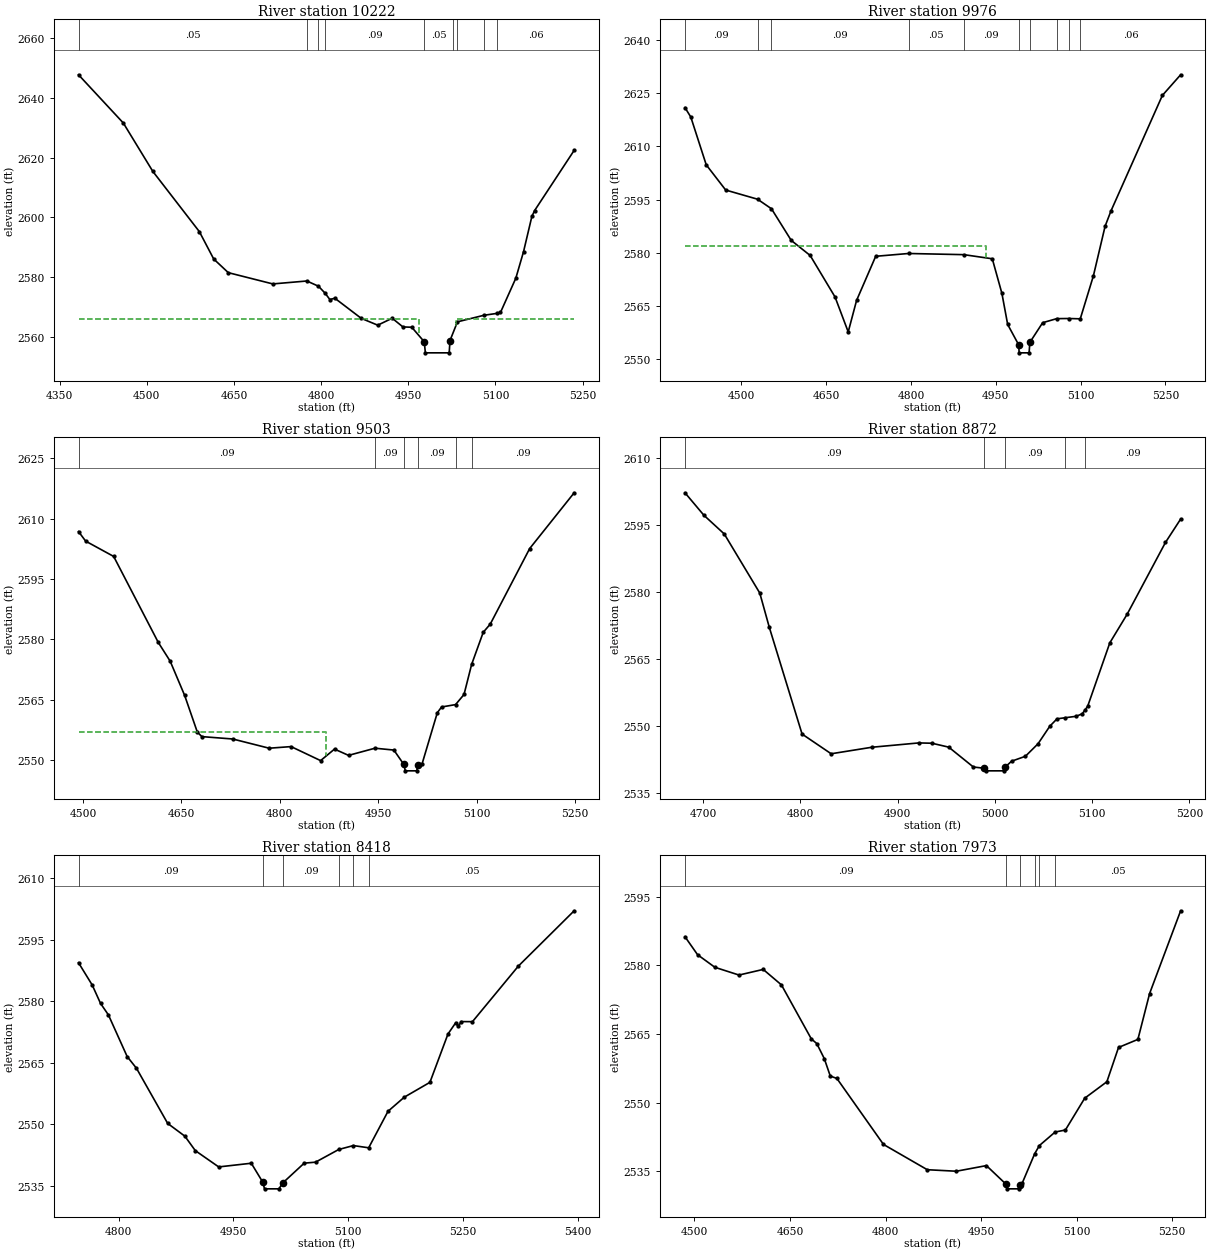
Type RM Length L Ch R = 1 ,10222   ,246,246,246
BEGIN DESCRIPTION:
bear_crk_xs_36
END DESCRIPTION:
XS GIS Cut Line= 3
      1080935.57       815014.54      1080344.45       814659.33
      1080181.75       814643.06
#Sta/Elev= 30
  4382.5 2647.74  4459.6  2631.6  4510.4  2615.4  4590.5 2595.23  4615.2 2586.07
  4640.3  2581.5  4716.9 2577.73  4775.5 2578.71  4795.5 2576.96  4807.1 2574.59
  4815.1  2572.5  4823.6 2572.95  4869.1 2566.21  4897.5 2563.92  4922.4 2566.24
  4940.9 2563.33  4956.1 2563.23 4977.59 2558.36  4979.5 2554.66  5020.5 2554.66
 5021.89 2558.77  5034.7 2565.04  5080.4 2567.24  5102.9 2567.87  5108.8 2568.19
  5135.2 2579.65  5148.4 2588.48  5162.8 2600.32  5167.5 2602.28  5235.6 2622.44
#Mann= 9 ,-1 , 0
  4382.5     .05       0  4775.5     .03       0  4795.5     .05       0
  4807.1     .09       0 4977.59     .05       0  5026.5     .09       0
  5034.7     .06       0  5080.4     .03       0  5102.9     .06       0
#XS Ineff= 2 , 0
       0    4968    2566    5032       0    2566
Permanent Ineff=
       F       F
Bank Sta=4977.59,5021.89
Exp/Cntr=0.5,0.3

Type RM Length L Ch R = 1 ,9976    ,473,473,473
BEGIN DESCRIPTION:
bear_crk_xs_38
END DESCRIPTION:
XS GIS Cut Line= 2
      1080967.85       814337.68      1080107.26        814504.3
#Sta/Elev= 30
  4400.2 2620.91  4410.5 2618.26  4437.8  2604.8  4472.2  2597.7  4528.5 2595.12
  4553.2 2592.42  4588.1 2583.52  4621.6 2579.27  4665.6 2567.58  4688.9 2557.74
  4703.7 2566.62  4737.5 2579.04  4795.6 2579.83  4893.4  2579.5  4943.7 2578.34
  4960.7  2568.6  4970.9 2559.84  4990.4  2554.1  4991.2 2551.85  5008.8 2551.85
  5010.1 2554.78  5032.8 2560.34  5057.7 2561.48    5079 2561.52  5099.3 2561.43
  5122.5 2573.52  5143.2  2587.5  5153.6 2591.81  5244.5 2624.35  5276.8 2630.16
#Mann= 10 ,-1 , 0
  4400.2     .09       0  4528.5     .03       0  4553.2     .09       0
  4795.6     .05       0  4893.4     .09       0  4990.4     .05       0
  5010.1     .09       0  5057.7     .06       0    5079     .03       0
  5099.3     .06       0
#XS Ineff= 2 , 0
       0    4933    2582               0
Permanent Ineff=
       F       F
Bank Sta=4990.4,5010.1
Exp/Cntr=0.3,0.1

Type RM Length L Ch R = 1 ,9503    ,631,631,631
BEGIN DESCRIPTION:
bear_crk_xs_39, ineff due to upstream constriction
END DESCRIPTION:
XS GIS Cut Line= 2
      1080893.04       813915.03      1080144.98         814021.
#Sta/Elev= 30
  4493.1 2606.76    4504 2604.38  4546.7 2600.58  4614.7 2579.22  4632.8 2574.57
  4654.9 2566.05  4674.2 2556.95  4681.1 2555.83  4728.1 2555.24  4783.7 2552.95
  4817.1 2553.35  4862.1 2549.87  4883.3 2552.73  4904.7 2551.17    4945 2552.95
  4973.8 2552.49 4989.01 2548.91  4991.2 2547.33  5008.8 2547.33    5010 2548.75
  5016.6 2548.96    5040 2561.76  5046.5 2563.19  5067.8 2563.78  5080.7 2566.29
  5092.3 2573.76    5110 2581.74  5120.7 2583.77  5180.8 2602.54  5248.6 2616.39
#Mann= 6 ,-1 , 0
  4493.1     .09       0    4945     .09       0 4989.01     .04       0
    5010     .09       0  5067.8     .03       0  5092.3     .09       0
#XS Ineff= 2 , 0
       0    4870    2557               0
Permanent Ineff=
       F       F
Bank Sta=4989.01,5010
Exp/Cntr=0.3,0.1

Type RM Length L Ch R = 1 ,8872    ,454,454,454
BEGIN DESCRIPTION:
bear_crk_xs_40
END DESCRIPTION:
XS GIS Cut Line= 2
      1080559.53       813350.24      1080116.93       813602.71
#Sta/Elev= 30
  4681.3 2602.24  4700.7 2597.22  4721.7 2593.02  4758.2  2579.8    4768 2572.12
  4801.7 2548.23  4831.6 2543.82  4873.4 2545.28  4921.7 2546.25  4935.2 2546.18
  4952.5  2545.3 4977.84 2540.85  4988.4  2540.6  4990.6    2540  5009.4    2540
  5010.1 2540.76 5017.04 2542.15  5031.3 2543.26  5044.3 2546.06  5056.4 2549.99
  5063.8 2551.64  5071.6 2551.87  5083.5 2552.21  5089.8 2552.78  5092.8 2553.69
  5095.3 2554.44  5118.1 2568.65  5135.9 2575.05  5175.3 2591.12  5190.9 2596.35
#Mann= 5 ,-1 , 0
  4681.3     .09       0  4988.4     .04       0  5010.1     .09       0
  5071.6     .03       0  5092.8     .09       0
Bank Sta=4988.4,5010.1
Exp/Cntr=0.3,0.1

Type RM Length L Ch R = 1 ,8418    ,445,445,445
BEGIN DESCRIPTION:
bear_crk_xs_41
END DESCRIPTION:
XS GIS Cut Line= 2
      1080341.35       812976.52      1079892.51       813444.06
#Sta/Elev= 30
  4747.4 2589.43  4765.3 2583.99  4776.2  2579.5  4786.5 2576.69    4811 2566.53
  4823.2 2563.66    4864  2550.2  4886.5 2547.08  4900.1 2543.56  4930.7 2539.58
  4973.3 2540.48 4988.55 2535.79  4990.6 2534.23  5009.4 2534.23  5014.7 2535.71
  5042.5  2540.5  5057.3 2540.74  5087.7 2543.84  5106.8 2544.79  5126.8 2544.25
  5152.1 2553.16  5173.4 2556.61  5206.9 2560.23  5230.5 2572.03  5240.8 2574.83
    5244 2573.88  5247.8 2575.06  5262.5 2575.04  5322.6 2588.62  5395.5 2602.11
#Mann= 6 ,-1 , 0
  4747.4     .09       0 4988.55     .05       0  5014.7     .09       0
  5087.7     .05       0  5106.8     .03       0  5126.8     .05       0
Bank Sta=4988.55,5014.7
Exp/Cntr=0.3,0.1

Type RM Length L Ch R = 1 ,7973    ,562,562,562
BEGIN DESCRIPTION:
bear_crk_xs_42
END DESCRIPTION:
XS GIS Cut Line= 2
      1080260.31       812850.91      1079509.13       813053.51
#Sta/Elev= 30
  4485.2 2586.26    4505 2582.32  4532.2 2579.57    4570 2577.88    4608 2579.11
  4636.6 2575.73  4683.5 2563.93  4692.1  2562.9  4703.9 2559.61  4713.3  2555.8
  4723.7 2555.27  4796.8 2540.85  4865.6 2535.32  4911.2 2534.99  4958.4 2536.22
 4989.66 2532.09  4990.6 2531.14  5009.4 2531.14  5010.9 2532.06  5014.5 2532.35
  5034.2 2538.82  5041.6 2540.61  5066.3 2543.56  5082.4    2544  5112.7 2550.95
  5147.5 2554.55  5165.8 2562.05  5196.2 2563.81  5214.6 2573.84  5263.3 2591.93
#Mann= 6 ,-1 , 0
  4485.2     .09       0 4989.66     .05       0  5010.9     .09       0
  5034.2     .05       0  5041.6     .03       0  5066.3     .05       0
Bank Sta=4989.66,5010.9
Exp/Cntr=0.3,0.1

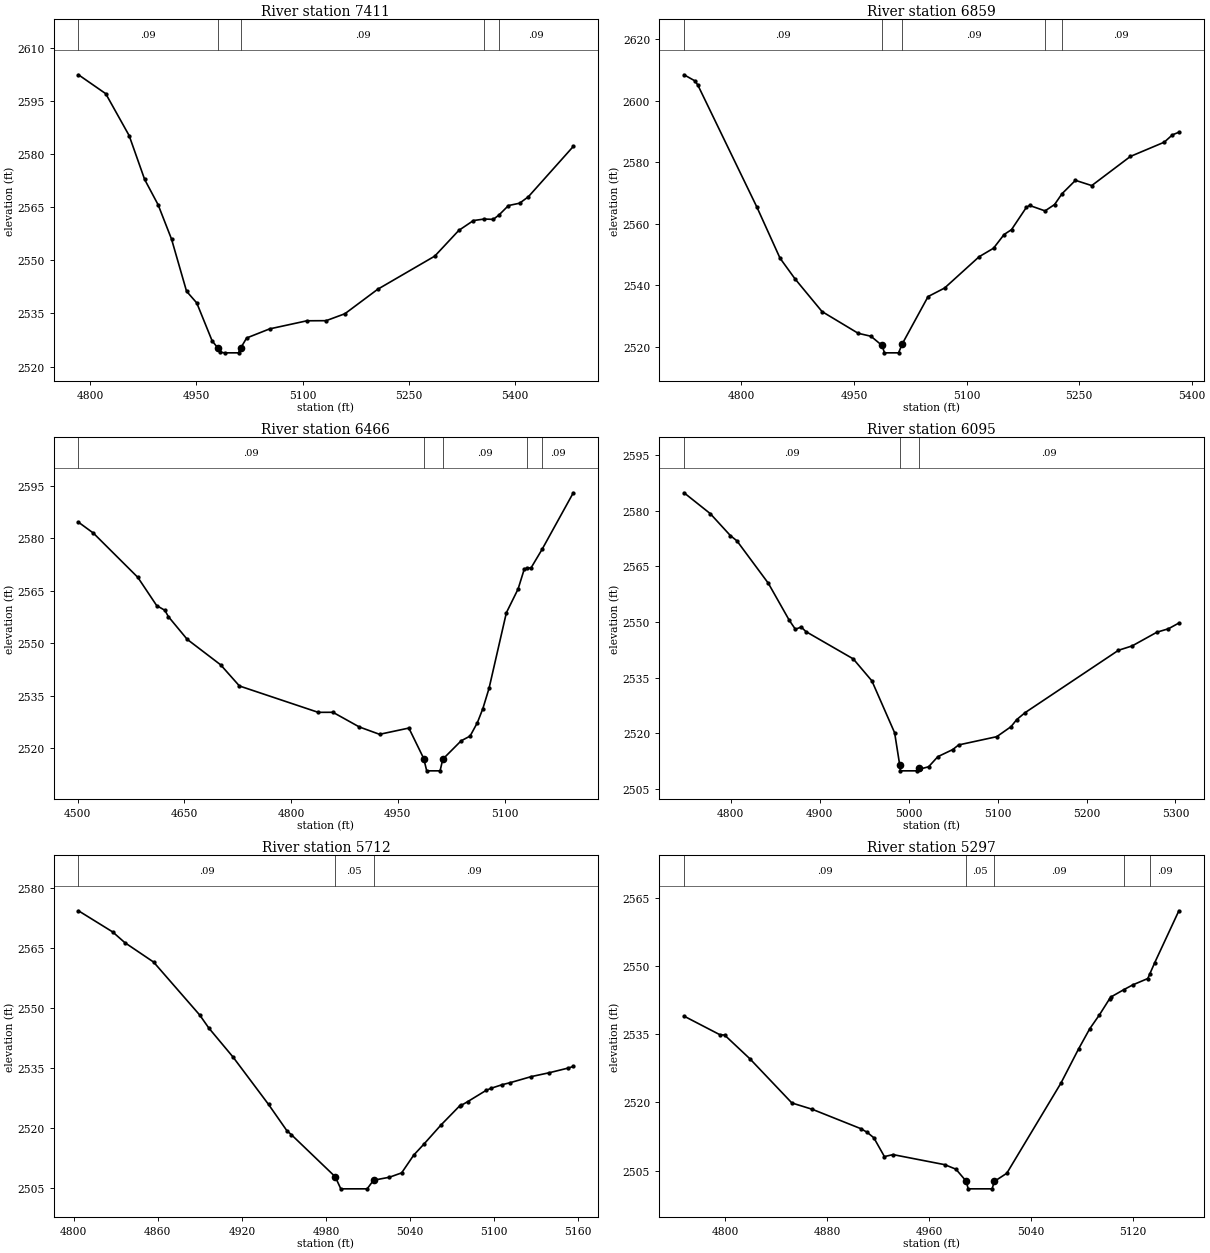
Type RM Length L Ch R = 1 ,7411    ,552,552,552
BEGIN DESCRIPTION:
bear_crk_xs_43
END DESCRIPTION:
XS GIS Cut Line= 2
      1080288.36       812754.29       1079649.4       812470.65
#Sta/Elev= 30
  4783.3 2602.46  4821.8 2597.12  4854.9 2585.27  4876.8 2572.87  4895.8 2565.73
  4914.8    2556    4936 2541.27  4950.4 2537.98 4972.14 2527.25 4980.27 2525.23
  4983.8    2524  4990.6 2523.87  5009.4 2523.87  5012.3 2525.17  5020.9 2528.07
  5053.4 2530.64  5106.1 2532.93  5133.2 2532.96  5159.7 2534.92    5206 2541.83
  5286.7 2551.21  5320.6 2558.47  5341.3 2561.26  5356.7 2561.69  5369.3 2561.59
  5377.4 2562.83  5390.8  2565.5  5406.5 2566.16  5418.9 2567.98  5482.4 2582.21
#Mann= 5 ,-1 , 0
  4783.3     .09       0 4980.27     .05       0  5012.3     .09       0
  5356.7     .03       0  5377.4     .09       0
Bank Sta=4980.27,5012.3
Exp/Cntr=0.3,0.1

Type RM Length L Ch R = 1 ,6859    ,393,393,393
BEGIN DESCRIPTION:
bear_crk_xs_44
END DESCRIPTION:
XS GIS Cut Line= 2
      1080328.88        812122.8      1079721.08       812378.39
#Sta/Elev= 30
  4723.5 2608.51  4737.9 2606.54  4741.8  2605.2  4820.8 2565.31  4851.4  2548.8
  4871.5 2542.02  4907.4 2531.41  4955.6 2524.33  4972.6 2523.37  4987.4 2520.36
  4990.6 2517.97  5009.4 2517.97  5014.5 2520.98  5048.7 2536.29  5070.7 2539.07
  5116.7 2549.26  5135.9 2552.03    5150  2556.5  5159.9 2558.09  5179.8 2565.38
    5184 2565.96  5204.6 2564.19  5217.3 2566.27  5227.2 2569.78  5245.1 2574.14
  5266.8 2572.43  5318.3 2581.92  5363.4 2586.56  5374.3 2588.95  5382.9  2589.8
#Mann= 5 ,-1 , 0
  4723.5     .09       0  4987.4     .05       0  5014.5     .09       0
  5204.6     .03       0  5227.2     .09       0
Bank Sta=4987.4,5014.5
Exp/Cntr=0.3,0.1

Type RM Length L Ch R = 1 ,6466    ,371,371,371
BEGIN DESCRIPTION:
bear_crk_xs_45
END DESCRIPTION:
XS GIS Cut Line= 2
      1080319.53       811697.34      1079689.92       811993.45
#Sta/Elev= 30
    4501 2584.61  4521.9  2581.5  4584.4 2568.84    4611 2560.74  4622.5  2559.4
  4627.3 2557.62  4653.9 2551.09  4700.9  2543.8  4727.3 2537.75    4838 2530.21
  4858.8 2530.22  4895.8 2526.03  4924.3 2523.92  4965.5 2525.71  4986.4    2517
  4990.6 2513.47  5009.4 2513.47  5013.2  2516.8    5039 2522.06  5051.6 2523.42
  5061.8 2527.24  5069.5 2531.25  5078.2 2537.05  5102.6 2558.71  5119.1 2565.51
  5127.9 2571.29  5132.3 2571.44  5137.4 2571.58  5152.7 2576.81  5196.7 2593.03
#Mann= 5 ,-1 , 0
    4501     .09       0  4986.4     .05       0  5013.2     .09       0
  5132.3     .03       0  5152.7     .09       0
Bank Sta=4986.4,5013.2
Exp/Cntr=0.3,0.1

Type RM Length L Ch R = 1 ,6095    ,383,383,383
BEGIN DESCRIPTION:
bear_crk_xs_46
END DESCRIPTION:
XS GIS Cut Line= 3
      1080269.66        811578.9       1079870.7       811656.82
      1079764.72        811762.8
#Sta/Elev= 30
  4747.4  2584.9  4776.9 2579.27  4799.6 2573.32  4806.8 2571.94  4842.1  2560.5
  4865.7 2550.49  4872.6 2548.05  4879.2 2548.66  4884.4 2547.43  4937.7 2540.05
  4958.6 2534.13  4984.2  2520.1  4989.9 2511.43  4990.6 2509.83  5009.4 2509.83
  5011.3 2510.63  5012.6  2510.3  5022.4 2510.93  5032.8 2513.66  5049.6 2515.58
  5056.1 2516.82    5099 2519.05  5115.1 2521.76  5121.4 2523.65  5130.9 2525.54
  5235.9 2542.38  5251.3 2543.56  5279.1 2547.26    5292 2548.18  5303.8 2549.73
#Mann= 3 ,-1 , 0
  4747.4     .09       0  4989.9     .05       0  5011.3     .09       0
Bank Sta=4989.9,5011.3
Exp/Cntr=0.3,0.1

Type RM Length L Ch R = 1 ,5712    ,415,415,415
BEGIN DESCRIPTION:
bear_crk_xs_47
END DESCRIPTION:
XS GIS Cut Line= 2
      1079802.12       811397.18      1079677.45       811727.58
#Sta/Elev= 30
  4803.4 2574.39  4827.8 2569.09  4836.5  2566.4    4857 2561.54  4889.9 2548.27
  4896.4 2545.01  4913.7 2537.73    4939 2525.87  4952.1 2519.28  4955.3 2518.28
 4986.59 2507.74  4990.6  2504.7  5009.4  2504.7 5013.95 2506.86  5025.3 2507.61
    5034  2508.7  5042.6 2513.14  5049.9 2515.91    5062 2520.67  5075.4 2525.49
  5076.4 2525.59  5081.1 2526.55  5094.3 2529.38  5097.8  2529.9  5105.7  2530.8
  5111.5 2531.31  5126.5 2532.83  5139.5 2533.81  5152.5 2534.94  5156.5 2535.37
#Mann= 3 , 0 , 0
  4803.4     .09       0 4986.59     .05       0 5013.95     .09       0
Bank Sta=4986.59,5013.95
Exp/Cntr=0.3,0.1

Type RM Length L Ch R = 1 ,5297    ,343,343,343
BEGIN DESCRIPTION:
bear_crk_xs_48
END DESCRIPTION:
XS GIS Cut Line= 2
      1079530.95       811503.16      1079194.33       811696.41
#Sta/Elev= 30
  4767.7 2538.97    4796 2534.86  4799.5 2534.82  4819.4 2529.59  4852.3 2519.89
  4868.4 2518.49  4906.6 2514.22  4911.4 2513.43  4916.6 2512.24  4924.9 2508.11
  4931.7 2508.54 4972.22 2506.33    4981 2505.34 4989.11 2502.68  4990.6 2501.02
  5009.4 2501.02  5011.1 2502.65  5020.9 2504.44  5063.3 2524.21  5077.2 2531.75
  5085.9 2536.16  5093.6 2539.26  5101.5 2542.76    5103 2543.24  5112.8  2544.8
  5119.7 2545.83  5131.5 2547.23  5133.2 2548.31    5137 2550.74  5155.9 2562.12
#Mann= 5 ,-1 , 0
  4767.7     .09       0 4989.11     .05       0  5011.1     .09       0
  5112.8     .03       0  5133.2     .09       0
Bank Sta=4989.11,5011.1
Exp/Cntr=0.3,0.1

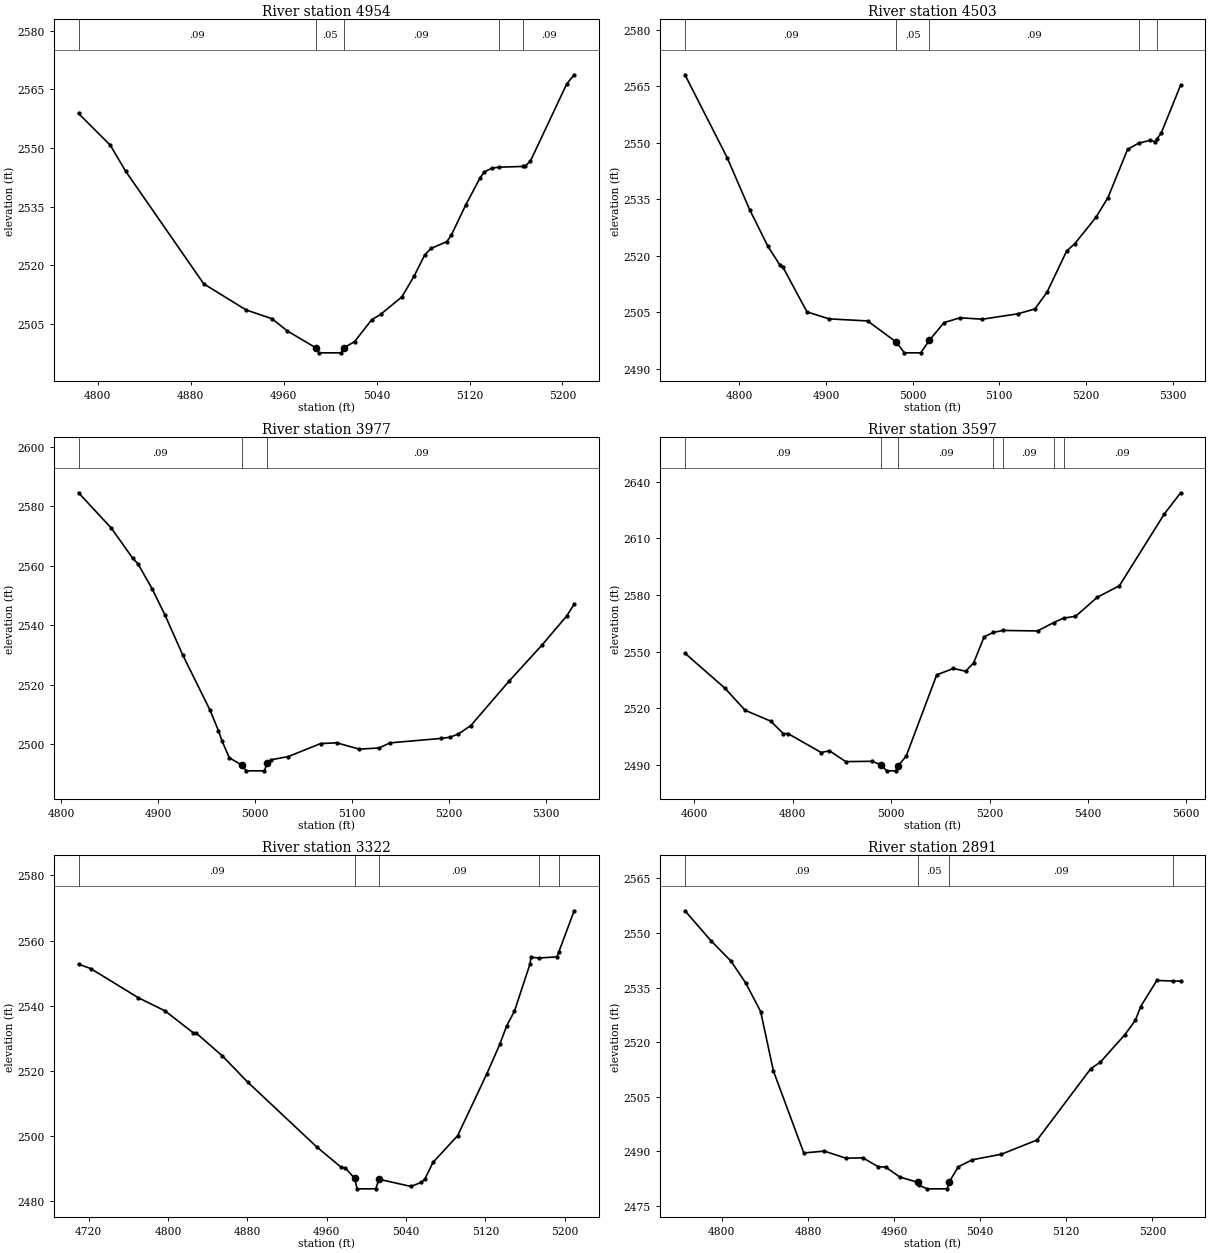
Type RM Length L Ch R = 1 ,4954    ,451,451,451
BEGIN DESCRIPTION:
bear_crk_xs_49
END DESCRIPTION:
XS GIS Cut Line= 2
      1079602.64       811331.73      1079184.98       811244.45
#Sta/Elev= 30
  4783.4 2558.82  4810.7 2550.71  4824.1    2544  4891.2 2515.26  4927.7 2508.58
    4950 2506.34  4963.1 2503.23 4987.63 2498.92  4990.6 2497.62  5009.4 2497.62
 5011.65 2498.86  5021.1  2500.5  5035.8 2506.09  5043.5 2507.45  5061.8 2511.93
  5072.5 2517.35  5081.4 2522.61  5086.9 2524.31  5100.4 2526.05  5104.2 2527.62
  5116.6 2535.33  5129.1 2542.35  5132.6 2543.84  5139.2 2544.81    5145 2545.07
    5166 2545.27  5167.8 2545.32  5172.5 2546.68  5203.8 2566.42  5210.1  2568.7
#Mann= 5 ,-1 , 0
  4783.4     .09       0 4987.63     .05       0 5011.65     .09       0
    5145     .03       0    5166     .09       0
Bank Sta=4987.63,5011.65
Exp/Cntr=0.3,0.1

Type RM Length L Ch R = 1 ,4503    ,526,526,526
BEGIN DESCRIPTION:
bear_crk_xs_50
END DESCRIPTION:
XS GIS Cut Line= 2
      1079789.66       810955.83      1079253.55       810756.35
#Sta/Elev= 30
  4737.3    2568    4786    2546  4811.9 2532.24    4833 2522.49  4846.8 2517.53
  4850.4 2516.93  4878.1  2505.1  4903.3 2503.25  4948.1 2502.69  4981.1 2497.09
  4990.6 2494.23  5009.4 2494.23  5019.2 2497.52  5036.3 2502.26  5054.8 2503.53
  5080.4 2503.15  5121.3 2504.58  5141.1 2505.87  5155.1 2510.31  5177.8 2521.25
  5187.3 2523.23  5211.8 2530.24  5225.4 2535.41  5248.1  2548.2  5260.7 2549.85
  5273.9  2550.6  5279.4 2550.23  5281.7 2550.92  5286.8 2552.48  5309.3 2565.26
#Mann= 5 ,-1 , 0
  4737.3     .09       0  4981.1     .05       0  5019.2     .09       0
  5260.7     .03       0  5281.7     .09       0
Bank Sta=4981.1,5019.2
Exp/Cntr=0.3,0.1

Type RM Length L Ch R = 1 ,3977    ,380,380,380
BEGIN DESCRIPTION:
bear_crk_xs_51
END DESCRIPTION:
XS GIS Cut Line= 2
      1079783.42        810248.6      1079362.64       810538.47
#Sta/Elev= 30
  4817.8 2584.46  4851.6 2572.61  4873.6  2562.5  4879.2 2560.53  4893.6 2552.25
  4907.1 2543.29  4925.1 2530.06  4953.3 2511.48  4962.1 2504.51  4965.7 2501.11
  4973.2 2495.44  4986.4 2492.92  4990.6 2491.03  5009.4 2491.03  5012.5 2493.81
  5016.2 2494.74    5034 2495.82  5067.3 2500.18  5083.9 2500.46  5107.4 2498.31
  5127.7 2498.73    5139 2500.43    5192 2501.93  5200.7 2502.32  5209.3 2503.38
  5222.2 2506.22  5261.7 2521.17  5295.7 2533.31  5321.3 2543.15  5328.8 2547.03
#Mann= 3 ,-1 , 0
  4817.8     .09       0  4986.4     .05       0  5012.5     .09       0
Bank Sta=4986.4,5012.5
Exp/Cntr=0.3,0.1

Type RM Length L Ch R = 1 ,3597    ,275,275,275
BEGIN DESCRIPTION:
bear_crk_xs_66
END DESCRIPTION:
XS GIS Cut Line= 2
       1079673.6       810183.77      1078755.58       810599.38
#Sta/Elev= 30
  4580.7 2549.18  4661.7 2530.72  4703.1 2518.95    4755 2513.23  4780.7 2506.59
    4790 2506.67  4857.7 2496.61  4874.4 2497.55  4907.6 2491.79    4961 2491.96
  4979.7 2490.07  4990.6 2486.91  5009.4 2486.91  5013.6 2489.55  5030.2 2494.54
  5092.5 2537.73  5126.6 2541.12  5151.3 2539.64  5167.5 2544.06  5188.9 2557.85
  5207.3 2560.17  5227.4 2561.24  5297.4 2560.98  5330.5 2565.41  5350.5  2567.8
  5374.6 2568.68  5418.9 2578.78    5464 2584.95  5555.1 2622.86  5588.4 2634.13
#Mann= 7 ,-1 , 0
  4580.7     .09       0  4979.7     .05       0  5013.6     .09       0
  5207.3     .03       0  5227.4     .09       0  5330.5     .03       0
  5350.5     .09       0
Bank Sta=4979.7,5013.6
Exp/Cntr=0.3,0.1

Type RM Length L Ch R = 1 ,3322    ,431,431,431
BEGIN DESCRIPTION:
bear_crk_xs_52
END DESCRIPTION:
XS GIS Cut Line= 2
       1079668.1       810156.34      1079172.51         810094.
#Sta/Elev= 30
  4709.9 2552.75  4722.1 2551.41  4770.2 2542.43    4797 2538.42  4825.7 2531.62
  4828.7 2531.53    4855 2524.53  4880.2 2516.58  4950.1 2496.57  4974.8 2490.31
  4978.7 2490.15  4988.3 2486.91  4990.6 2483.73  5009.4 2483.73  5012.7 2486.67
  5044.9 2484.47  5055.3 2485.71  5058.8 2486.64  5067.1 2491.84    5092 2500.08
  5121.5 2519.14  5134.4 2528.08  5141.4 2533.82  5149.2 2538.29  5164.8 2552.72
    5166 2554.87  5173.7 2554.65  5192.1 2554.99  5194.1 2556.64  5209.4 2569.15
#Mann= 5 ,-1 , 0
  4709.9     .09       0  4988.3     .05       0  5012.7     .09       0
  5173.7     .03       0  5194.1     .09       0
Bank Sta=4988.3,5012.7
Exp/Cntr=0.3,0.1

Type RM Length L Ch R = 1 ,2891    ,377,377,377
BEGIN DESCRIPTION:
bear_crk_xs_53
END DESCRIPTION:
XS GIS Cut Line= 2
      1079730.44       809714.98      1079272.25       809761.74
#Sta/Elev= 30
  4765.8  2556.1  4789.9 2547.88  4808.5 2542.28  4822.3 2536.21  4836.1  2528.4
    4848 2512.02  4876.2 2489.52  4895.2 2490.02  4915.4 2488.07    4931 2488.18
  4945.1 2485.78  4952.4 2485.61  4965.4 2482.89  4982.3 2481.43  4982.9 2480.76
  4990.6 2479.65  5009.4 2479.65  5011.2 2481.47  5019.8 2485.74  5032.8 2487.64
  5059.8 2489.17    5093 2493.09  5142.9 2512.72  5151.7 2514.48  5174.6 2522.07
  5184.3 2526.01  5189.1 2529.73  5204.2 2536.94  5219.4 2536.79  5226.3 2536.76
#Mann= 4 ,-1 , 0
  4765.8     .09       0  4982.3     .05       0  5011.2     .09       0
  5219.4     .03       0
Bank Sta=4982.3,5011.2
Exp/Cntr=0.3,0.1

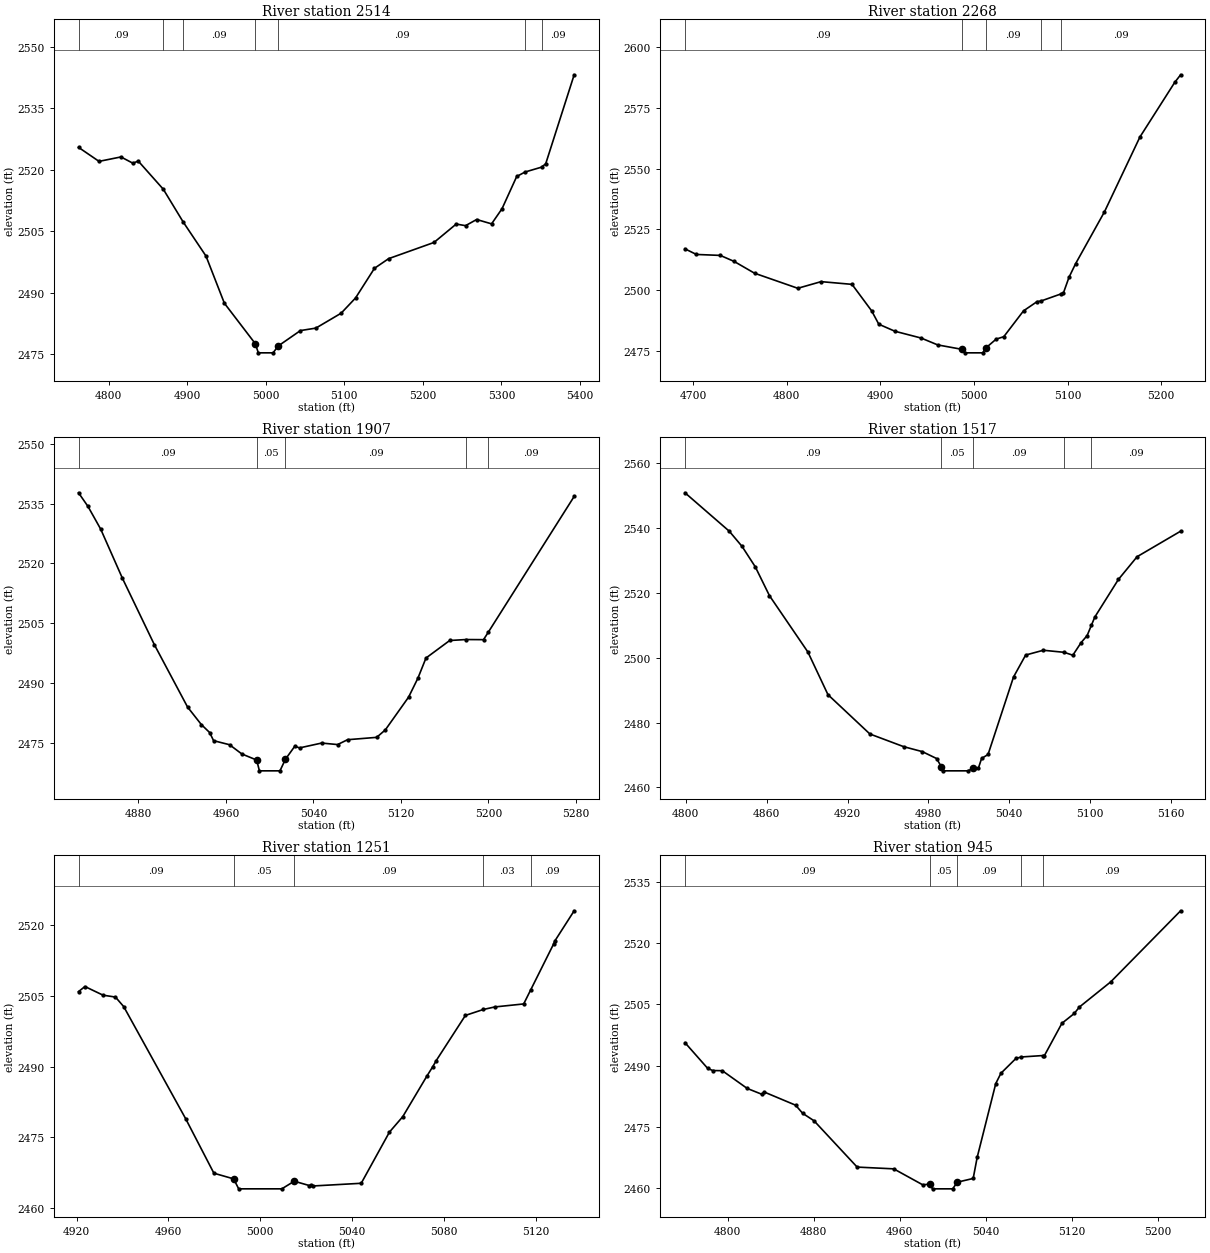
Type RM Length L Ch R = 1 ,2514    ,246,246,246
BEGIN DESCRIPTION:
bear_crk_xs_54
END DESCRIPTION:
XS GIS Cut Line= 2
      1079618.23       809283.29        1079079.       809610.57
#Sta/Elev= 30
  4761.8 2525.43  4787.9 2522.01  4815.8 2523.09    4831 2521.56  4837.8 2522.09
  4869.7 2515.21  4894.9 2507.25    4924 2498.92  4947.4 2487.41  4986.8 2477.53
  4990.6 2475.31  5009.4 2475.31  5015.9 2476.98  5044.2 2480.74  5063.8 2481.34
    5096 2484.98  5114.3 2488.69  5138.4 2495.93  5156.4 2498.28  5214.1 2502.23
  5242.4 2506.72  5254.3 2506.33  5268.4 2507.83  5287.4 2506.77  5300.7 2510.46
  5319.4 2518.33  5330.1 2519.42    5351  2520.6  5356.3 2521.43  5392.5 2543.13
#Mann= 7 ,-1 , 0
  4761.8     .09       0  4869.7     .03       0  4894.9     .09       0
  4986.8     .05       0  5015.9     .09       0  5330.1     .03       0
    5351     .09       0
Bank Sta=4986.8,5015.9
Exp/Cntr=0.3,0.1

Type RM Length L Ch R = 1 ,2268    ,361,361,361
BEGIN DESCRIPTION:
bear_crk_xs_67
END DESCRIPTION:
XS GIS Cut Line= 2
      1079559.41       809286.31      1079038.75        809190.4
#Sta/Elev= 30
  4691.3 2516.94  4703.5 2514.63    4729 2514.24  4743.8 2511.76  4765.6  2506.9
  4811.8 2500.69  4836.7 2503.43  4869.7 2502.31  4890.7 2491.38  4898.3 2485.89
  4915.5 2482.99  4943.5 2480.19  4961.2 2477.36  4986.9 2475.55  4990.6 2474.09
  5009.4 2474.09  5012.4 2476.03  5023.7 2479.75  5031.8 2480.74  5052.9 2491.39
  5067.3 2495.18  5071.5 2495.44    5093 2498.38  5095.5 2498.76  5101.5 2505.25
  5108.5 2510.81  5139.3 2532.16  5177.2 2563.02  5214.4 2585.54  5220.7 2588.67
#Mann= 5 ,-1 , 0
  4691.3     .09       0  4986.9     .05       0  5012.4     .09       0
  5071.5     .03       0    5093     .09       0
Bank Sta=4986.9,5012.4
Exp/Cntr=0.3,0.1

Type RM Length L Ch R = 1 ,1907    ,390,390,390
BEGIN DESCRIPTION:
bear_crk_xs_55
END DESCRIPTION:
XS GIS Cut Line= 2
      1079746.02       809180.43      1079334.59        808990.3
#Sta/Elev= 30
  4825.2 2537.74  4833.8 2534.34  4845.5 2528.61  4865.4 2516.26  4894.6  2499.6
  4924.9 2483.99  4937.5 2479.59  4945.1 2477.59  4948.7 2475.55  4963.3 2474.53
  4974.5 2472.22  4988.1 2470.69  4990.6 2467.98  5009.4 2467.98  5014.4 2470.89
  5022.9 2474.13  5027.4 2473.74  5047.5 2474.95  5062.1 2474.57  5071.2 2475.79
  5097.8 2476.38  5105.7 2478.24    5127 2486.47  5135.5 2491.21  5142.9 2496.28
  5164.6 2500.68  5179.5 2500.92  5195.5 2500.89    5200 2502.81  5278.4 2536.82
#Mann= 5 ,-1 , 0
  4825.2     .09       0  4988.1     .05       0  5014.4     .09       0
  5179.5     .03       0    5200     .09       0
Bank Sta=4988.1,5014.4
Exp/Cntr=0.3,0.1

Type RM Length L Ch R = 1 ,1517    ,266,266,266
BEGIN DESCRIPTION:
bear_crk_xs_56
END DESCRIPTION:
XS GIS Cut Line= 2
      1079721.08       808767.13      1079368.87       808873.11
#Sta/Elev= 30
  4799.4 2550.91  4832.3 2539.04  4841.8 2534.34  4851.6 2528.04  4862.1 2519.16
  4890.6 2501.79  4905.5 2488.63  4936.6  2476.5  4961.8 2472.57  4975.5 2471.06
  4986.1 2468.93 4989.59 2466.43  4990.6 2465.13  5009.4 2465.13  5013.2 2465.91
  5017.1 2465.92  5019.5 2468.95  5024.3 2470.18  5043.2 2494.08  5052.2 2500.85
  5065.3 2502.33  5080.8 2501.69  5087.2  2500.8  5093.4 2504.72  5097.8 2506.84
    5101 2510.05  5103.5 2512.56    5121 2524.16  5134.9 2531.19  5167.2 2539.06
#Mann= 5 ,-1 , 0
  4799.4     .09       0 4989.59     .05       0  5013.2     .09       0
  5080.8     .03       0    5101     .09       0
Bank Sta=4989.59,5013.2
Exp/Cntr=0.3,0.1

Type RM Length L Ch R = 1 ,1251    ,306,306,306
BEGIN DESCRIPTION:
bear_crk_xs_57
END DESCRIPTION:
XS GIS Cut Line= 2
      1079396.93       808616.58       1079300.3       808809.83
#Sta/Elev= 28
  4920.8 2505.93  4923.6 2507.01  4931.5 2505.17  4936.9 2504.77  4940.5 2502.74
  4967.5 2478.91  4979.8 2467.33  4988.4 2466.13  4990.6 2464.01  5009.4 2464.01
  5014.8 2465.63  5021.4 2464.71  5022.1 2464.73    5023 2464.62    5044 2465.19
  5056.3 2476.07  5062.1 2479.35  5072.6 2487.96  5075.2 2489.99  5076.7 2491.28
  5089.4 2500.87  5097.2 2502.13  5102.2 2502.67  5114.8 2503.31  5117.8 2506.24
  5127.8 2516.01  5128.4 2516.71  5136.8 2523.11
#Mann= 5 ,-1 , 0
  4920.8     .09       0  4988.4     .05       0  5014.8     .09       0
  5097.2     .03       0  5117.8     .09       0
Bank Sta=4988.4,5014.8
Exp/Cntr=0.3,0.1

Type RM Length L Ch R = 1 ,945     ,271,271,271
BEGIN DESCRIPTION:
bear_crk_xs_58
END DESCRIPTION:
XS GIS Cut Line= 2
      1079340.82       808588.53      1078888.87       808498.14
#Sta/Elev= 30
  4760.4 2495.63  4781.5 2489.34  4786.2 2488.81  4795.1 2488.77  4818.2 2484.44
  4831.6 2483.03  4834.3 2483.53  4863.3 2480.33  4869.8 2478.35  4880.4 2476.52
  4920.5 2465.19  4954.5 2464.76  4981.5 2460.85  4988.1 2461.03  4990.6 2459.87
  5009.4 2459.87  5013.5 2461.49  5028.4 2462.41  5032.1 2467.56  5049.4 2485.63
  5054.2 2488.14  5068.2 2491.78  5073.3 2492.13  5093.4 2492.48  5094.6 2492.45
  5110.9 2500.36  5122.4 2502.77  5127.1 2504.33  5156.3  2510.5  5221.3 2527.89
#Mann= 5 ,-1 , 0
  4760.4     .09       0  4988.1     .05       0  5013.5     .09       0
  5073.3     .03       0  5093.4     .09       0
Bank Sta=4988.1,5013.5
Exp/Cntr=0.3,0.1