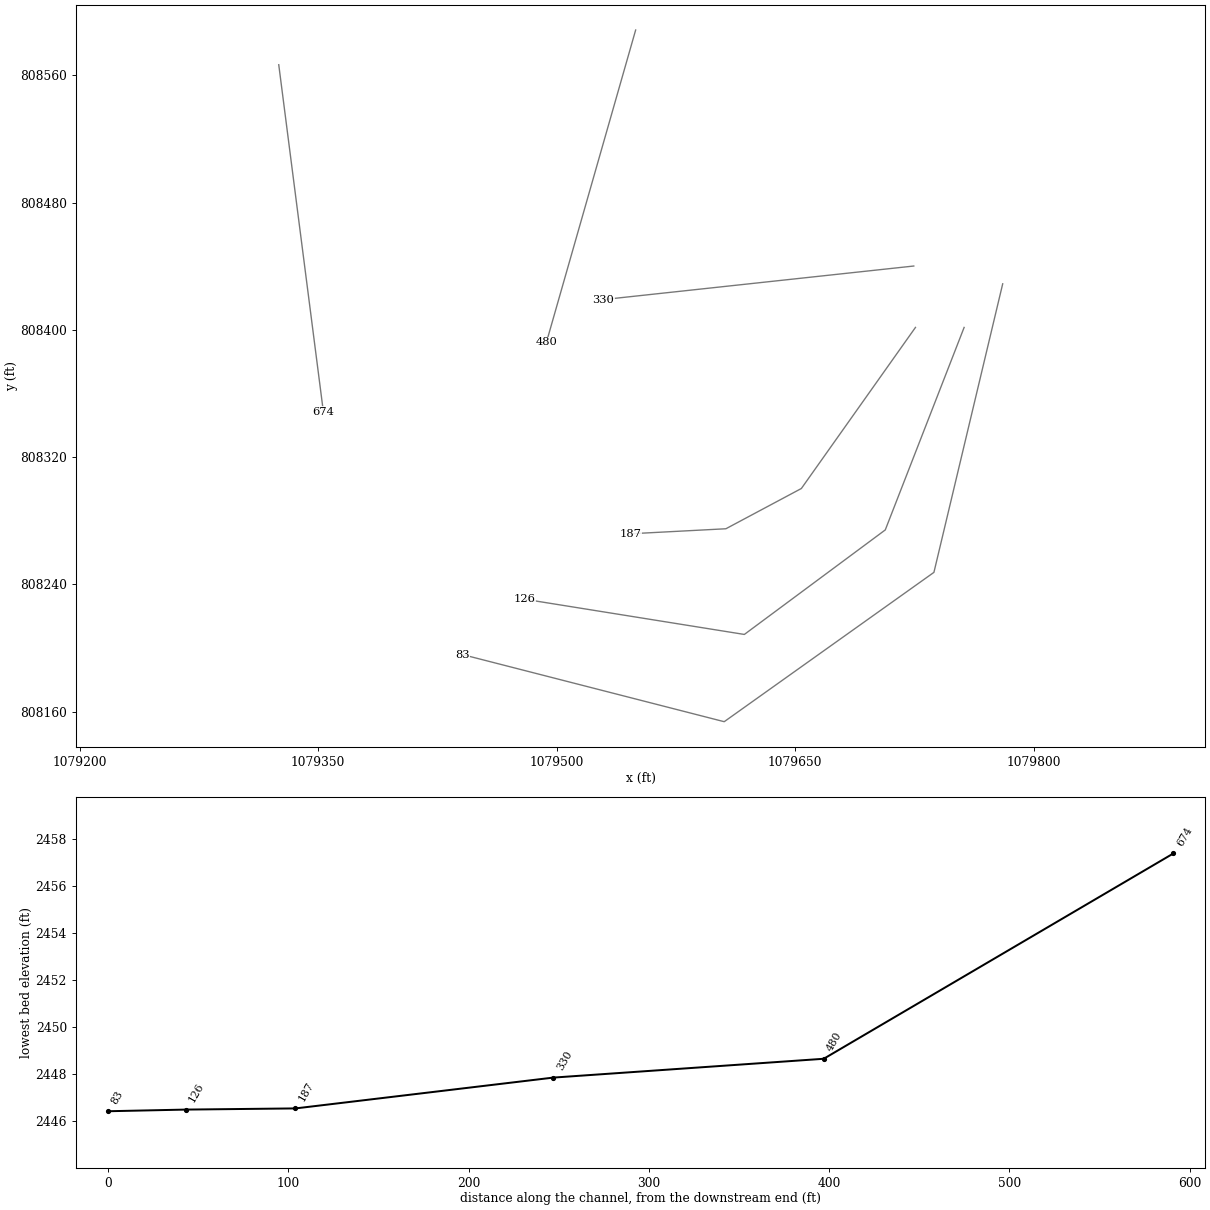
HEC-RAS study lds_bear_crk.prj: Bear Creek Limited Detail Study

--- lds_bear_crk.g01 (geometry) --- (continued)

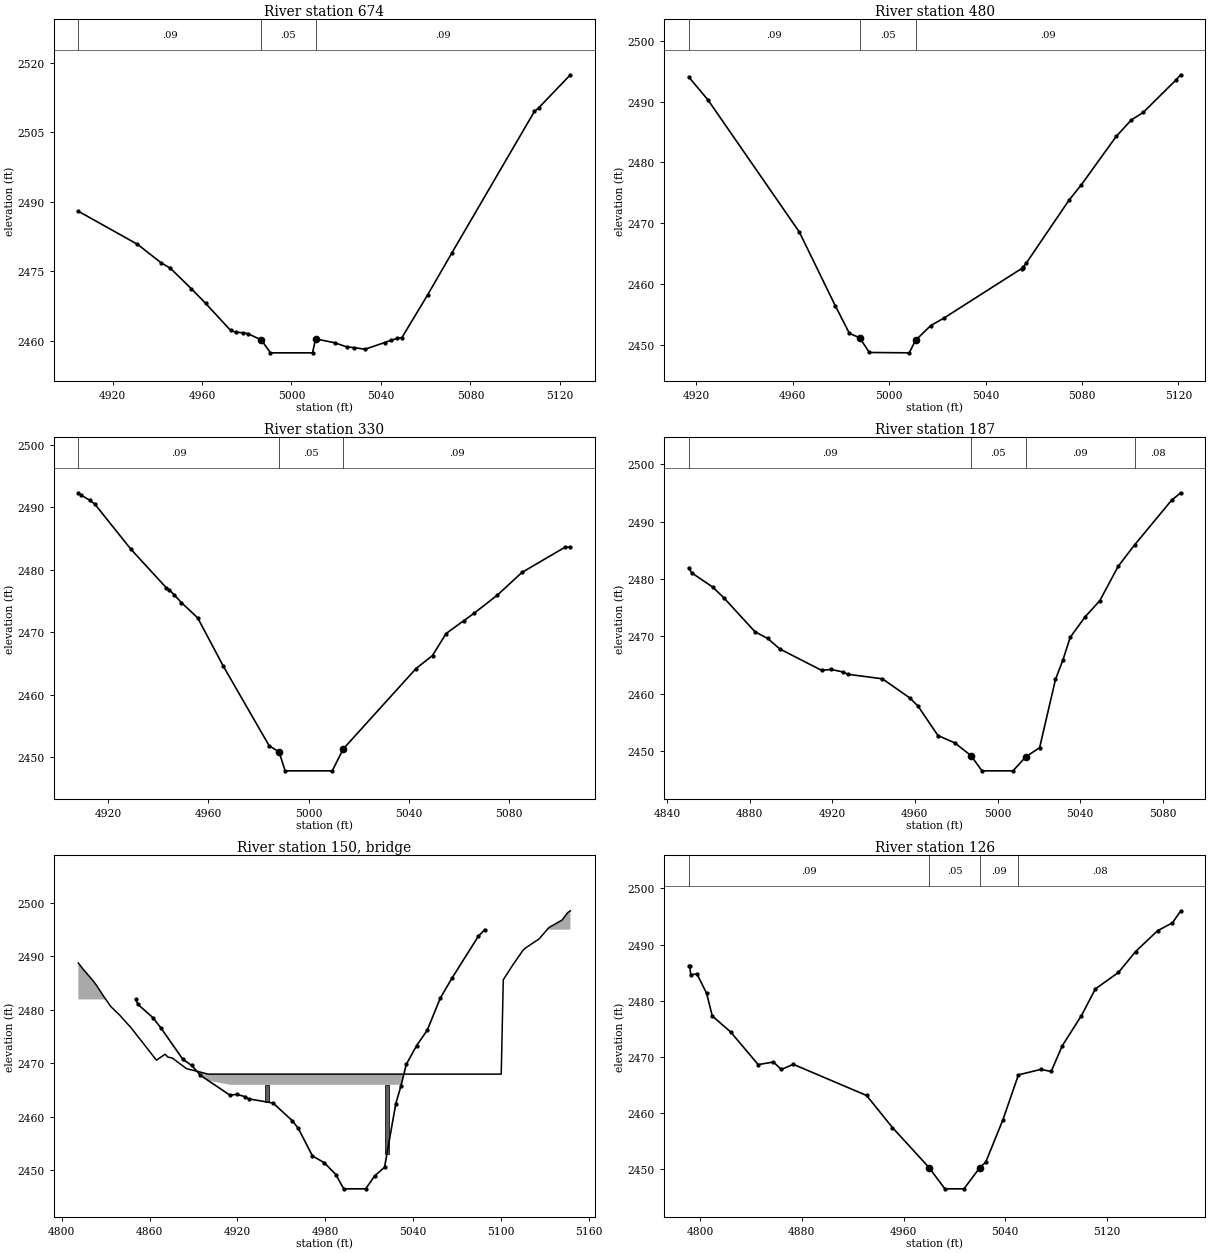
Type RM Length L Ch R = 1 ,674     ,194,194,194
BEGIN DESCRIPTION:
bear_crk_xs_59
END DESCRIPTION:
XS GIS Cut Line= 2
      1079325.24       808566.71      1079353.29       808348.53
#Sta/Elev= 28
  4904.7 2487.95  4931.1 2480.83  4941.8 2476.79  4945.8 2475.67  4955.2 2471.24
  4961.6 2468.08  4972.8 2462.22  4975.1 2461.87  4978.1 2461.72  4980.6 2461.52
  4985.8 2460.33  4986.4 2460.25  4990.6 2457.39  5009.4 2457.39  5010.8 2460.41
  5019.4 2459.55  5024.6 2458.69  5027.8 2458.52  5032.9 2458.17  5041.7 2459.62
  5044.3 2460.06  5047.3  2460.5  5049.4  2460.7  5060.9 2469.92  5071.8 2479.03
  5108.6 2509.48  5110.5 2510.25  5124.7  2517.4
#Mann= 3 ,-1 , 0
  4904.7     .09       0  4986.4     .05       0  5010.8     .09       0
Bank Sta=4986.4,5010.8
Exp/Cntr=0.3,0.1

Type RM Length L Ch R = 1 ,480     ,150,150,150
BEGIN DESCRIPTION:
bear_crk_xs_60
END DESCRIPTION:
XS GIS Cut Line= 2
      1079549.65       808588.53      1079493.55       808392.17
#Sta/Elev= 22
  4916.8 2494.06  4924.8 2490.28  4962.7 2468.54  4977.6 2456.42 4983.48 2451.86
  4987.7 2451.15 4991.75 2448.72  5008.3 2448.66 5010.91 2450.71 5017.19 2453.14
  5022.7 2454.38  5054.9 2462.53  5055.4 2462.67  5055.6 2462.75  5056.9 2463.45
  5074.6 2473.79  5079.7 2476.31  5094.2 2484.29  5100.5 2487.01  5105.4 2488.23
    5119 2493.58    5121 2494.43
#Mann= 3 , 0 , 0
  4916.8     .09       0  4987.7     .05       0 5010.91     .09       0
Bank Sta=4987.7,5010.91
Exp/Cntr=0.3,0.1

Type RM Length L Ch R = 1 ,330     ,143,143,143
BEGIN DESCRIPTION:
bear_crk_xs_61
END DESCRIPTION:
XS GIS Cut Line= 2
      1079724.53       808440.14      1079529.38       808419.04
#Sta/Elev= 25
  4908.1 2492.32  4909.2 2491.96  4912.6 2491.14  4914.7  2490.5    4929 2483.33
  4943.1 2477.17  4944.4  2476.8  4946.3 2476.03  4949.2 2474.77  4955.7 2472.33
    4966 2464.55  4984.2 2451.89  4988.2 2450.86  4990.6 2447.86  5009.4 2447.86
  5013.8 2451.37  5042.8 2464.21  5049.4  2466.3  5054.8 2469.81  5061.9 2471.88
  5065.9 2473.03  5075.3 2475.97  5085.1 2479.59  5102.4 2483.65  5104.4 2483.61
#Mann= 3 ,-1 , 0
  4908.1     .09       0  4988.2     .05       0  5013.8     .09       0
Bank Sta=4988.2,5013.8
Exp/Cntr=0.5,0.3

Type RM Length L Ch R = 1 ,187     ,61,61,61
BEGIN DESCRIPTION:
bear_crk_xs_65
END DESCRIPTION:
XS GIS Cut Line= 4
      1079725.58       808401.53      1079653.85       808300.26
      1079606.38       808274.94      1079546.26       808271.78
#Sta/Elev= 30
  4850.6 2481.96    4852 2481.06  4862.2 2478.58  4867.7 2476.66  4882.7 2470.77
  4888.8 2469.62  4894.7 2467.78  4914.9 2464.06  4919.4 2464.22    4925  2463.8
  4927.6 2463.38  4944.3 2462.59  4957.5 2459.27  4961.5 2457.85  4971.2  2452.7
 4979.24 2451.44 4987.12 2449.22  4992.5 2446.55  5007.5 2446.55 5013.66 2448.98
 5020.38 2450.59 5028.05 2462.48 5031.57 2465.79  5035.2 2469.82  5042.3 2473.35
  5049.5  2476.2  5058.4  2482.2  5066.3 2485.91  5084.3 2493.74  5088.7 2495.01
#Mann= 4 ,-1 , 0
  4850.6     .09       0 4987.12     .05       0 5013.66     .09       0
  5066.3     .08       0
#XS Ineff= 2 , 0
       0    4890    2468    5050       0    2468
Permanent Ineff=
       F       F
Bank Sta=4987.12,5013.66
Exp/Cntr=0.5,0.3

Type RM Length L Ch R = 3 ,150     ,,,
BEGIN DESCRIPTION:
bear_crk_xs_62
Structure ID: RR_Bridge
Approximate Survey Structure
END DESCRIPTION:
Bridge Culvert--1,0,-1,-1, 0
Deck Dist Width WeirC Skew NumUp NumDn MinLoCord MaxHiCord MaxSubmerge Is_Ogee
20,20,3,0, 27, 27, , , , 0, 1,1,,
  4811.4  4814.3  4821.3  4823.9  4828.7  4833.5  4839.5  4847.4  4864.7  4870.6
  4872.5  4875.5  4885.3  4889.3    4900    4900    5100    5100  5101.4  5108.4
    5115  5117.1  5125.9  5132.5  5141.5  5145.4  5147.2
 2488.78 2487.74 2485.51 2484.57 2482.54 2480.65 2479.06 2476.66 2470.61 2471.72
 2471.19 2471.01 2469.01 2468.75    2468    2468    2468    2468 2485.65 2488.61
 2491.21 2491.68 2493.29  2495.4  2496.8 2498.21 2498.54
 2426.55 2426.55 2426.55 2426.55 2426.55 2426.55 2426.55 2426.55 2426.55 2426.55
 2426.55 2426.55 2426.55 2426.55 2426.55    2466    2466 2426.55 2426.55 2426.55
 2426.55 2426.55 2426.55 2426.55 2426.55 2426.55 2426.55
  4811.4  4814.3  4821.3  4823.9  4828.7  4833.5  4839.5  4847.4  4864.7  4870.6
  4872.5  4875.5  4885.3  4889.3    4900    4900    5100    5100  5101.4  5108.4
    5115  5117.1  5125.9  5132.5  5141.5  5145.4  5147.2
 2488.78 2487.74 2485.51 2484.57 2482.54 2480.65 2479.06 2476.66 2470.61 2471.72
 2471.19 2471.01 2469.01 2468.75    2468    2468    2468    2468 2485.65 2488.61
 2491.21 2491.68 2493.29  2495.4  2496.8 2498.21 2498.54
 2426.55 2426.55 2426.55 2426.55 2426.55 2426.55 2426.55 2426.55 2426.55 2426.55
 2426.55 2426.55 2426.55 2426.55 2426.55    2466    2466 2426.55 2426.55 2426.55
 2426.55 2426.55 2426.55 2426.55 2426.55 2426.55 2426.55
Pier Skew, UpSta & Num, DnSta & Num=  ,4940, 2 ,4940, 2 , 0 , 0 , 0 ,0,0
       3       3
 2461.16    2466
       3       3
 2458.29    2466
Pier Skew, UpSta & Num, DnSta & Num=  ,5022, 2 ,5022, 2 , 0 , 0 , 0 ,0,0
       3       3
    2440    2466
       3       3
    2440    2466
BR Coef= 0 , 1 , 0 ,1.25, 0 ,,,0.8,0,2,6,
WSPro=,,,, 1 ,,,, 0 ,,,, 0 ,,,,-1 ,-1 ,-1 , 0 , 0 , 0 , 0 , 0
BC Design=,, 0 ,, 0 ,,,,,,
BC HTab HWMax=2495.01

Type RM Length L Ch R = 1 ,126     ,43,43,43
BEGIN DESCRIPTION:
bear_crk_xs_64
END DESCRIPTION:
XS GIS Cut Line= 4
      1079756.18       808401.53       1079706.6       808274.21
      1079617.99       808208.49       1079479.8       808230.64
#Sta/Elev= 30
  4791.1 2486.22  4791.9 2486.12  4792.7 2484.64  4797.5 2484.79  4805.1 2481.35
  4809.6 2477.29    4824 2474.45  4845.7 2468.63  4857.7 2469.09  4863.9 2467.76
  4873.3 2468.68  4930.9 2463.13  4951.3 2457.41    4980  2450.3  4992.5  2446.5
  5007.5  2446.5    5020  2450.3  5024.5 2451.21  5038.1 2458.78  5050.3  2466.8
  5067.8 2467.77  5076.1 2467.41  5084.7 2471.95  5099.9 2477.37  5110.8 2482.11
    5129 2485.05  5142.4 2488.76  5159.8 2492.49  5171.4 2493.88    5178 2496.03
#Mann= 4 ,-1 , 0
  4791.1     .09       0    4980     .05       0    5020     .09       0
  5050.3     .08       0
#XS Ineff= 2 , 0
       0    4890    2467    5057       0    2467
Permanent Ineff=
       F       F
Bank Sta=4980,5020
Exp/Cntr=0.5,0.3

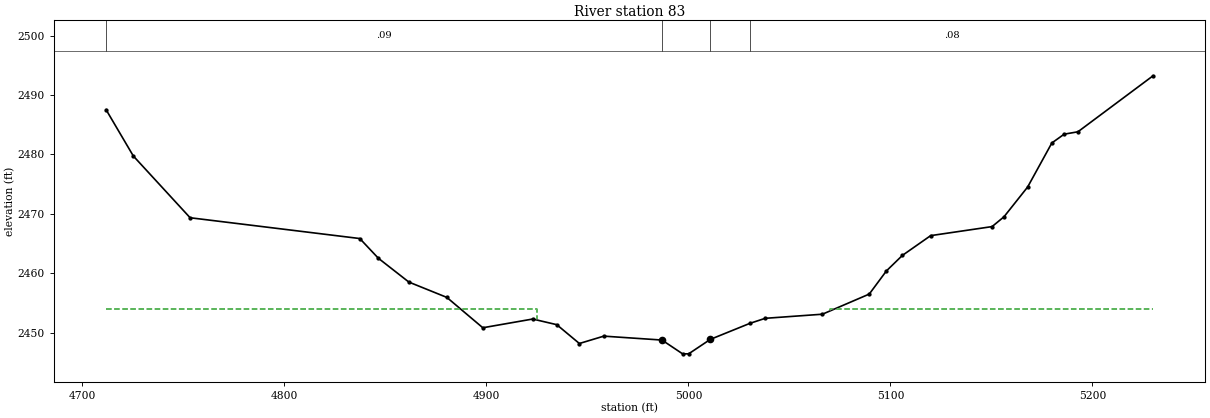
Type RM Length L Ch R = 1 ,83      ,0,0,0
BEGIN DESCRIPTION:
bear_crk_xs_63, ineff due to upstream restriction
END DESCRIPTION:
XS GIS Cut Line= 4
      1079780.44       808428.95      1079737.19       808247.52
      1079605.33       808153.63      1079440.77       808195.83
#Sta/Elev= 30
  4711.7 2487.53  4725.2 2479.73  4753.3 2469.34  4837.3 2465.84  4846.5 2462.52
  4861.6 2458.51  4880.4 2455.93  4898.2 2450.82  4922.9 2452.29  4934.8 2451.34
    4946 2448.17  4958.1 2449.41  4986.9 2448.75  4997.1 2446.43  5000.1 2446.43
  5010.8 2448.86  5030.4 2451.56    5038 2452.41  5066.3  2453.1  5089.5 2456.49
    5098 2460.39  5105.9    2463  5119.9 2466.33  5150.3 2467.85  5156.2  2469.5
  5167.9 2474.51  5179.9 2481.93    5186 2483.41  5192.8 2483.81    5230 2493.24
#Mann= 4 ,-1 , 0
  4711.7     .09       0  4986.9     .05       0  5010.8     .09       0
  5030.4     .08       0
#XS Ineff= 2 , 0
       0    4925    2454    5070       0    2454
Permanent Ineff=
       F       F
Bank Sta=4986.9,5010.8
Exp/Cntr=0.3,0.1

Chan Stop Cuts=-1
Use User Specified Reach Order=0
User Specified Reach Order=Bear Creek      ,Reach-1